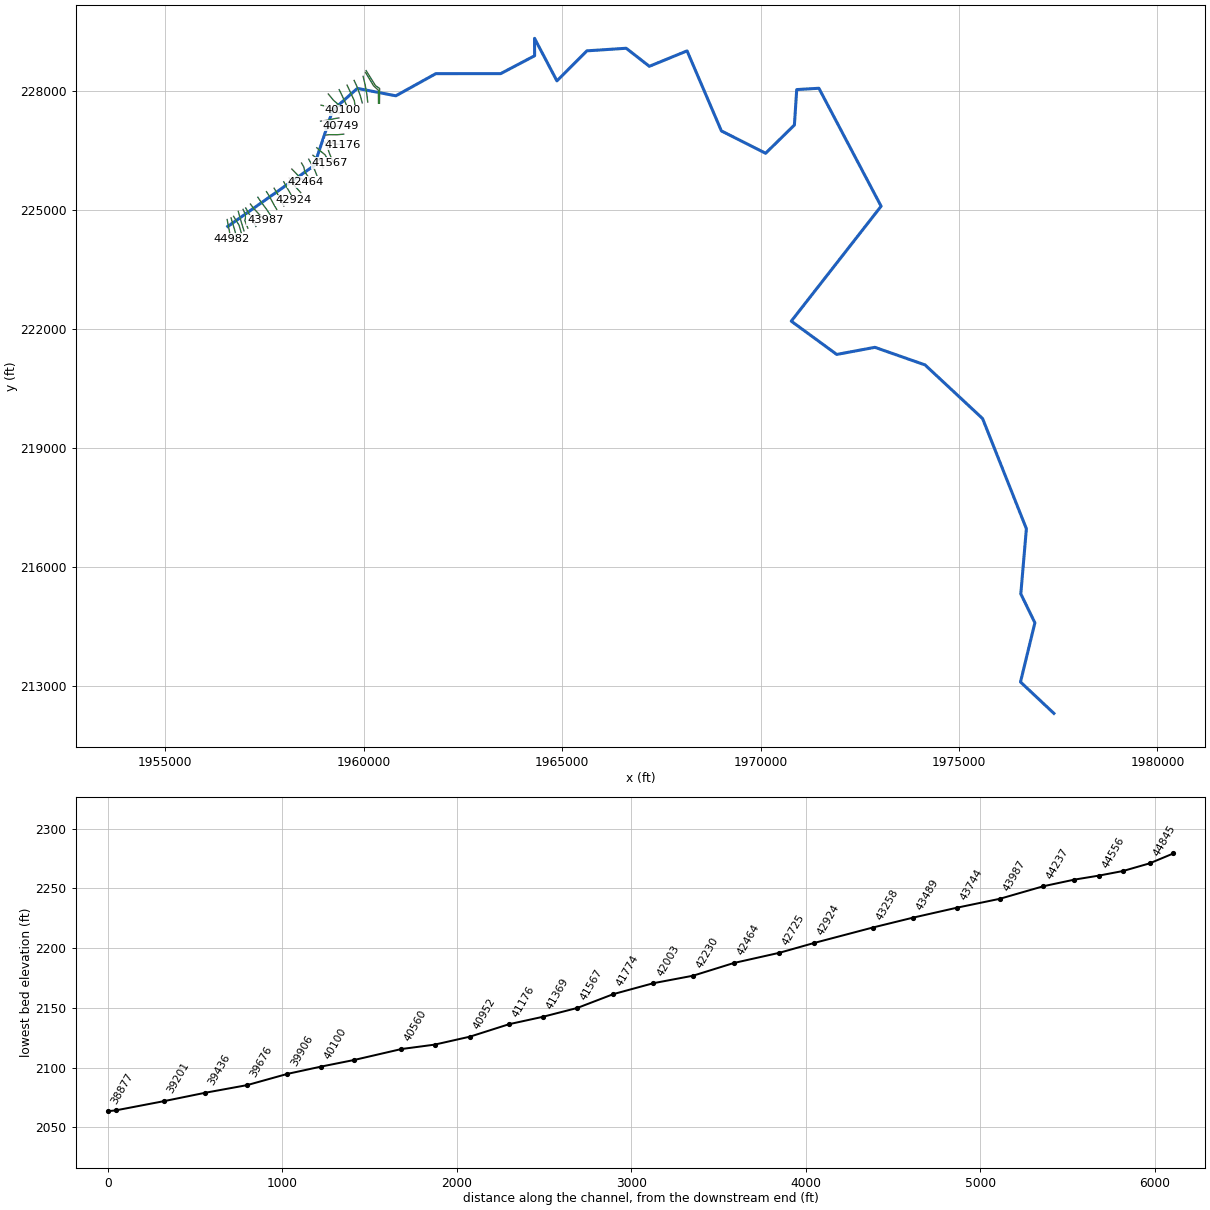
--- LTBLUESTRV.prj (project) ---

Proj Title=LTBLUESTRV
Current Plan=p01
Default Exp/Contr=0,0
English Units
Geom File=g01
Flow File=f01
Plan File=p01
BEGIN DESCRIPTION:
Stream Name: Little Bluestone River
Flood Zone: Approximate
Summers County, West Virginia
HEC-RAS Version: 5.0.7
Hydrology Method:
Regression.
Model Notes:
END DESCRIPTION:
DSS File=dss
DSS Export Rating Curves= 0
DSS Export Rating Curve Sorted= 0
DSS Export Volume Flow Curves= 0
DXF OffsetX= 0
DXF OffsetY= 0
DXF ScaleX= 0
DXF ScaleY= 0

--- LTBLUESTRV.p01 (plan) ---

Plan Title=Floodplain
Program Version=5.07
Short Identifier=Floodplain
Geom File=g01
Flow File=f01
Subcritical Flow
K Sum by GR= 0
Std Step Tol= 0.01
Critical Tol= 0.01
Num of Std Step Trials= 20
Max Error Tol= 0.3
Flow Tol Ratio= 0.001
Split Flow NTrial= 30
Split Flow Tol= 0.02
Split Flow Ratio= 0.02
Log Output Level= 0
Friction Slope Method= 1
Unsteady Friction Slope Method= 2
Unsteady Bridges Friction Slope Method= 1
Parabolic Critical Depth
Global Vel Dist= 0 , 0 , 0
Global Log Level= 0
CheckData=True
Encroach Param=-1 ,0,0, 0
Computation Interval=0.1SEC
Output Interval=1MIN
Instantaneous Interval=Max Profile
Mapping Interval=1HOUR
Computation Time Step Use Courant=        0
Computation Time Step Use Time Series=    0
Computation Time Step Count To Double=0
Computation Time Step Max Doubling=0
Computation Time Step Max Halving=0
Computation Time Step Residence Courant=0
Run HTab= 0
Run UNet= 0
Run Sediment= 0
Run PostProcess= 0
Run WQNet= 0
Run RASMapper= 0
UNET Theta= 0
UNET Theta Warmup= 0
UNET ZTol= 0
UNET ZSATol= 0
UNET MxIter= 0
UNET Max Iter WO Improvement= 0
UNET MaxInSteps= 0
UNET DtIC= 0
UNET DtMin= 0
UNET MaxCRTS= 0
UNET WFStab= 0
UNET SFStab= 0
UNET WFX= 1
UNET SFX= 1
UNET 1D Methodology=Finite Difference
UNET DSS MLevel= 1
UNET Pardiso=0
UNET DZMax Abort= 0
UNET Use Existing IB Tables= 0
UNET Froude Reduction=False
UNET Froude Limit= 0
UNET Froude Power= 0
UNET D1 Cores= 0
UNET D2 Coriolis=0
UNET D2 Cores= 0
UNET D2 Theta= 1
UNET D2 Theta Warmup= 1
UNET D2 Z Tol= 0.01
UNET D2 Volume Tol= 0.01
UNET D2 Max Iterations= 20
UNET D2 Equation= 0
UNET D2 RampUpFraction=0.1
UNET D2 TimeSlices= 1
UNET D2 BCVolumeCheck=0
UNET D1D2 MaxIter= 0
UNET D1D2 ZTol=0.01
UNET D1D2 QTol=0.1
UNET D1D2 MinQTol=1
DSS File=dss
Write IC File= 0
Write IC File at Fixed DateTime=0
Write IC File at Sim End=0
Echo Input=False
Echo Parameters=False
Echo Output=False
Write Detailed= 0
HDF Write Warmup=0
HDF Write Time Slices=0
HDF Flush=0
HDF Face Node Velocities=0
HDF Compression= 1
HDF Chunk Size= 1
HDF Spatial Parts= 1
HDF Use Max Rows=0
HDF Fixed Rows= 1
Calibration Method= 0
Calibration Iterations= 20
Calibration Max Change=0.05
Calibration Tolerance=0.2
Calibration Maximum=1.5
Calibration Minimum=0.5
Calibration Optimization Method= 1
WQ AD Non Conservative
WQ ULTIMATE=-1
WQ Max Comp Step=1HOUR
WQ Output Interval=15MIN
WQ Output Selected Increments= 0
WQ Output face flow=0
WQ Output face velocity=0
WQ Output face area=0
WQ Output face dispersion=0
WQ Output cell volume=0
WQ Output cell surface area=0
WQ Output cell continuity=0
WQ Output cumulative cell continuity=0
WQ Output face conc=0
WQ Output face dconc_dx=0
WQ Output face courant=0
WQ Output face peclet=0
WQ Output face adv mass=0
WQ Output face disp mass=0
WQ Output cell mass=0
WQ Output cell source sink temp=0
WQ Output nsm pathways=0
WQ Output nsm derived pathways=0
WQ Output MaxMinRange=-1
WQ Daily Max Min Mean=-1
WQ Daily Range=0
WQ Daily Time=0
WQ Create Restart=0
WQ Fixed Restart=0
WQ System Summary=0
WQ Write To DSS=0
WQ Use Fixed Temperature=0
Sorting and Armoring Iterations= 10
XS Update Threshold= 0.02
Bed Roughness Predictor= 0
Hydraulics Update Threshold= 0.02
Energy Slope Method= 1
Volume Change Method= 1
Sediment Retention Method= 0
XS Weighting Method= 0
Number of US Weighted Cross Sections= 1
Number of DS Weighted Cross Sections= 1
Upstream XS Weight=0
Main XS Weight=1
Downstream XS Weight=0
Number of DS XS's Weighted with US Boundary= 1
Upstream Boundary Weight= 1
Weight of XSs Associated with US Boundary= 0
Number of US XS's Weighted with DS Boundary= 1
Downstream Boundary Weight= 0.5
Weight of XSs Associated with DS Boundary= 0.5
Percentile Method= 0
Sediment Output Level= 3
Mass or Volume Output= 0
Output Increment Type= 1
Profile and TS Output Increment= 1
XS Output Flag= 0
XS Output Increment= 10
Write Gradation File= 0
Read Gradation Hotstart= 0
Write HDF5 File= 1
Write Binary Output= 1
Write DSS Sediment File= 0
SV Curve= 0
Specific Gage Flag= 0

--- LTBLUESTRV.f01 (steady flow) ---

Flow Title=Flows
Program Version=5.07
Number of Profiles= 6
Profile Names=01pct,10pct,04pct,02pct,0_2pct,01plus
River Rch & RM=LTBLUESTRV,Main            ,44982
     800     428     566     679    1110    1183
River Rch & RM=LTBLUESTRV,Main            ,42230
     892     480     633     758    1236    1320
River Rch & RM=LTBLUESTRV,Main            ,38823
    1394     763     998    1190    1916    2062
River Rch & RM=LTBLUESTRV,Main            ,33727
    1572     864    1127    1342    2154    2324
River Rch & RM=LTBLUESTRV,Main            ,26694
    2138    1189    1543    1831    2914    3162
River Rch & RM=LTBLUESTRV,Main            ,21244
    3673    2086    2679    3161    4955    5433
River Rch & RM=LTBLUESTRV,Main            ,18246
    4082    2328    2984    3516    5496    6037
River Rch & RM=LTBLUESTRV,Main            ,11551
    5096    2931    3741    4397    6832    7536
Boundary for River Rch & Prof#=LTBLUESTRV,Main            , 1
Up Type= 0
Dn Type= 3
Dn Slope=0.00707
Boundary for River Rch & Prof#=LTBLUESTRV,Main            , 2
Up Type= 0
Dn Type= 3
Dn Slope=0.00707
Boundary for River Rch & Prof#=LTBLUESTRV,Main            , 3
Up Type= 0
Dn Type= 3
Dn Slope=0.00707
Boundary for River Rch & Prof#=LTBLUESTRV,Main            , 4
Up Type= 0
Dn Type= 3
Dn Slope=0.00707
Boundary for River Rch & Prof#=LTBLUESTRV,Main            , 5
Up Type= 0
Dn Type= 3
Dn Slope=0.00707
Boundary for River Rch & Prof#=LTBLUESTRV,Main            , 6
Up Type= 0
Dn Type= 3
Dn Slope=0.00707
DSS Import GetInterval= 0
DSS Import GetPeak= 0
DSS Import FillOption= 0

--- LTBLUESTRV.g01 (geometry) ---

Geom Title=Geometry
Program Version=5.07

River Reach=LTBLUESTRV      ,Main
Reach XY= 30
     1956579.179224583.692000012     1958756.996226117.493999992
1959221.40600001227510.724000001     1959843.801228061.070999971
1960813.41900001227874.4389999851961820.36400003228432.599000009
1963454.91299999228433.4670000331964309.07900001228883.118999976
     1964307.343229322.3550000311964870.91000004228250.432000033
1965625.91900001229007.251000032     1966616.371229072.356000007
1967199.70400001228617.4939999771968149.35700004229006.383000004
1969014.80800002226989.8900000021970128.52400002226427.390000001
     1970853.784227138.1110000141970912.25900004 228031.32600002
     1971471.189228064.7600000341973038.02900002225092.755000031
1970775.13700001222197.2689999891971920.54600001221359.081999987
     1972881.779221538.067000024       1974144.8221095.358999991
     1975594.139219744.0330000141976697.94763543216968.628138538
1976557.50287434215326.4113907371976912.38224985214599.413616656
 1976549.5499412213107.1540588911977391.57135143212316.573378143

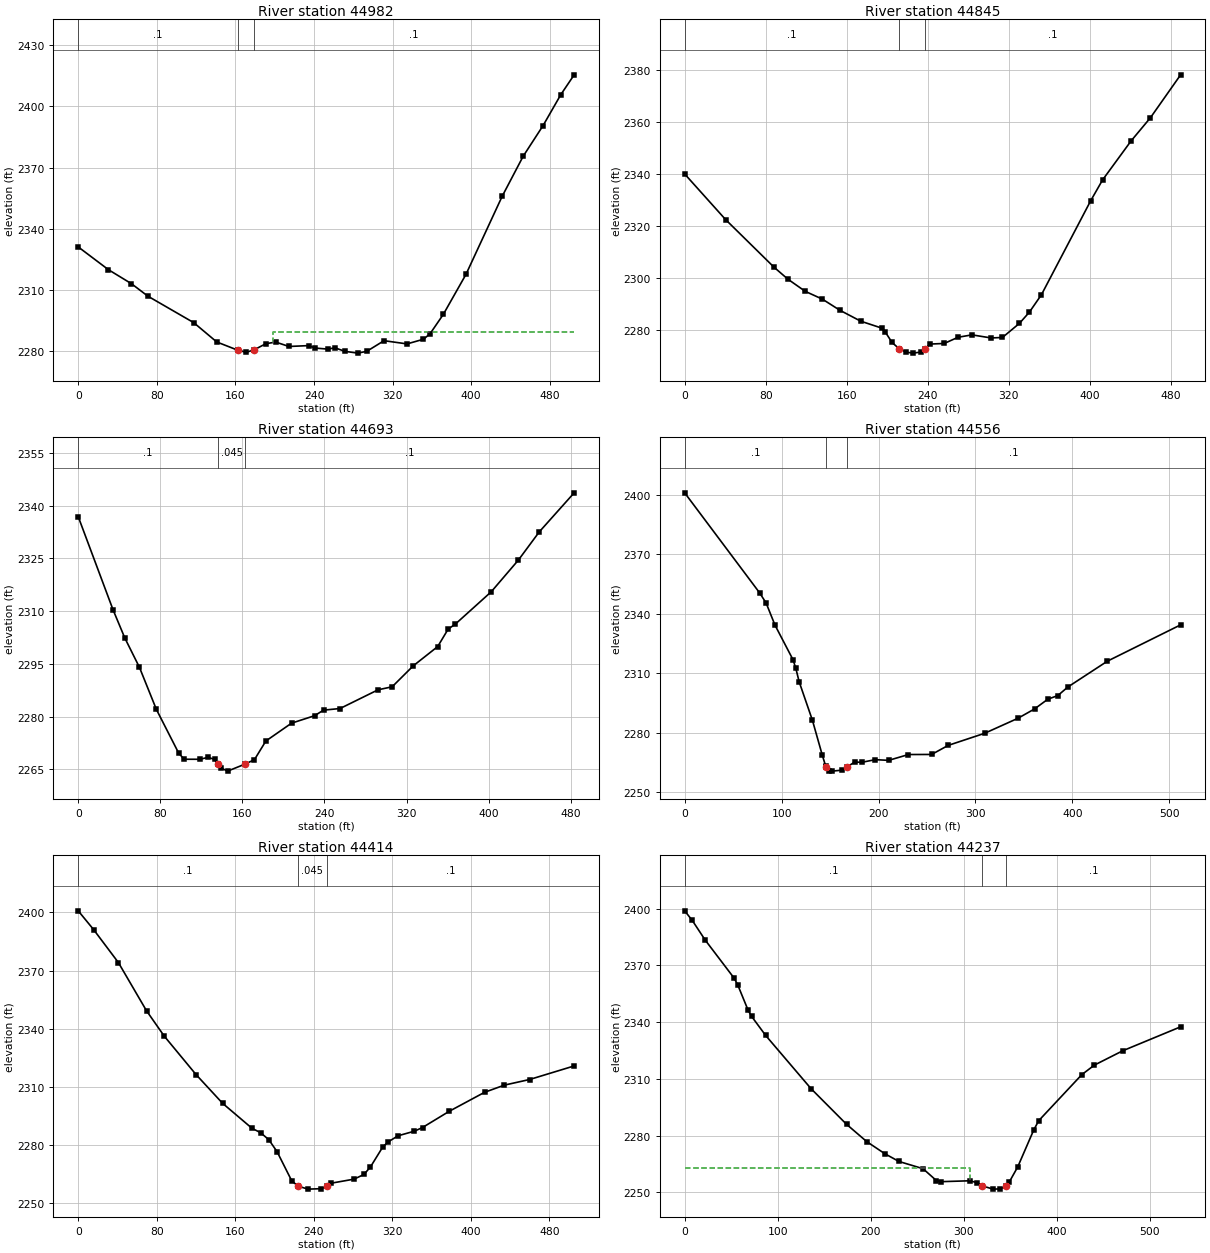
Type RM Length L Ch R = 1 ,44982   ,130.9,136.2,138.8
XS GIS Cut Line= 4
 1956563.9359791224757.7533833631956587.59735682224631.559368873
1956632.94833077224394.9455917041956682.24286768224268.751577214
#Sta/Elev= 30
       0 2331.22    30.8 2320.05    54.2  2313.2    70.9  2307.1   117.6 2294.12
     141 2284.67  162.162280.687     171 2279.61   178.7 2280.74   191.1 2283.84
   201.1  2284.6   214.5 2282.46   234.5 2282.88   241.2 2281.68   254.4 2281.16
   261.2 2281.84   271.3 2280.09   284.6  2279.2   293.7 2280.08   311.3 2285.29
   334.7 2283.72   351.4    2286   358.1 2288.67   371.6 2298.15   394.7 2317.78
   431.5 2355.98   452.9 2375.61   473.2 2390.67   491.3 2405.86   504.8  2415.5
#Mann= 3 ,-1 , 0
       0      .1       0  162.16    .045       0   178.7      .1       0
#XS Ineff= 2 , 0
                           198.5         2289.77
Permanent Ineff=
       F       F
Bank Sta=162.16,178.7
XS Rating Curve= 0 ,0
Exp/Cntr(USF)=0,0
Exp/Cntr=0.3,0.1

Type RM Length L Ch R = 1 ,44845   ,146.5,152.1,156.4
XS GIS Cut Line= 4
1956662.52505292224799.1607943671956699.98890097224669.023216925
1956753.22700083224495.5064470011956794.63441184224327.905021506
#Sta/Elev= 30
       0 2340.03    40.4 2322.43    88.2 2304.05   101.9 2299.43     119 2294.74
     136 2291.71   153.2 2287.44   173.8 2283.22   194.4 2280.57   197.8 2279.18
   204.7 2275.01  211.492272.663   218.4 2271.29   225.3 2270.89   232.9 2271.28
  237.582272.664   242.4 2274.39   256.2 2274.62   269.9 2277.01   283.6 2277.94
   302.5 2276.75   313.7 2276.93   330.5 2282.39   340.3 2286.71   352.2 2293.43
   400.9 2329.76   412.5 2337.71   440.7 2352.79   459.8 2361.74   489.6  2378.3
#Mann= 3 ,-1 , 0
       0      .1       0  211.49    .045       0  237.58      .1       0
Bank Sta=211.49,237.58
XS Rating Curve= 0 ,0
Exp/Cntr(USF)=0,0
Exp/Cntr=0.3,0.1

Type RM Length L Ch R = 1 ,44693   ,137.8,137.1,130.6
XS GIS Cut Line= 4
1956725.62206016224838.5964238961956749.28343788224799.160794367
1956863.64676351224613.8133355851956924.77198928 224402.83271761
#Sta/Elev= 30
       0 2336.86    33.9 2310.41    45.4 2302.37    59.7    2294    76.2 2282.04
    97.9 2269.64   103.2 2267.88   118.6 2267.87   126.5 2268.41   132.9 2267.85
  136.222266.529   139.1 2265.41   145.6  2264.5  162.91 2266.53   171.8 2267.77
   182.9 2273.06   207.9 2278.13   230.4 2280.26   239.1 2281.84   255.2  2282.3
   292.3 2287.63     306 2288.48   326.5 2294.42   350.4 2299.92   360.6 2304.89
   367.5 2306.28   402.6  2315.5   429.1 2324.53   449.4 2332.53   483.4 2343.63
#Mann= 3 ,-1 , 0
       0      .1       0  136.22    .045       0  162.91      .1       0
Bank Sta=136.22,162.91
XS Rating Curve= 0 ,0
Exp/Cntr(USF)=0,0
Exp/Cntr=0.3,0.1

Type RM Length L Ch R = 1 ,44556   ,150.7,142.2,130.7
XS GIS Cut Line= 4
1956843.92894875224962.8186569091956867.59032646224874.088490471
1956926.74377076224670.9949984011956987.86899653224471.845069284
#Sta/Elev= 30
       0 2400.87    77.2 2350.56      84 2345.39    93.2  2334.2   111.8 2316.78
   114.7  2312.4   118.1 2305.71   131.8 2286.29     142 2268.69   145.4 2263.32
  146.322262.653   148.8 2260.85   152.3 2260.67   162.5 2261.18  167.112262.655
   175.3 2265.21     183 2265.14   196.7 2266.45   210.4 2266.09   230.9 2269.03
   254.8 2269.07   271.9 2273.64   309.5 2279.73   343.8 2287.28     361    2292
   374.7 2296.91     385 2298.73   395.3 2303.03   436.2 2316.08   511.7 2334.36
#Mann= 3 ,-1 , 0
       0      .1       0  146.32    .045       0  167.11      .1       0
Bank Sta=146.32,167.11
XS Rating Curve= 0 ,0
Exp/Cntr(USF)=0,0
Exp/Cntr=0.3,0.1

Type RM Length L Ch R = 1 ,44414   ,159.9,177.6,192.4
XS GIS Cut Line= 4
1956964.20761881225014.0849752961957035.19175196224856.342457183
1957009.55859277224730.1484426931957084.48628887224540.857420958
#Sta/Elev= 30
       0 2400.86    15.7 2391.17    40.9 2374.19    69.6 2349.29    87.6 2336.25
     120  2316.4   147.1 2301.55   177.2  2288.6   185.8 2286.41   194.2 2282.77
   202.6 2276.61   217.4  2261.7  223.782258.835   234.2 2257.27   247.6  2257.5
  253.352258.836   257.6 2260.32     281 2262.42   291.1 2264.82   297.8 2268.75
   310.3 2279.02   315.8 2281.64   325.8 2284.78   342.6 2287.18   350.8 2289.06
   378.2 2297.48     414 2307.22   434.2 2310.93   459.9 2313.83   505.3 2320.83
#Mann= 3 ,-1 , 0
       0      .1       0  223.78    .045       0  253.35      .1       0
Bank Sta=223.78,253.35
XS Rating Curve= 0 ,0
Exp/Cntr(USF)=0,0
Exp/Cntr=0.3,0.1

Type RM Length L Ch R = 1 ,44237   ,245,250,250.6
XS GIS Cut Line= 4
1957031.24818901225049.577041871 1957157.4422035224822.822172084
1957236.31346255224684.7974687361957287.57978094224582.264831963
#Sta/Elev= 30
       0 2398.84     8.2 2393.74      22 2383.42    53.2 2363.22      57 2359.73
    68.2 2346.28      72    2343      87    2333   135.8 2304.86     174    2286
   195.7 2276.86     215  2270.5   230.3 2266.37   256.2 2262.54   270.5  2256.3
   275.3 2255.68   306.5 2256.15   313.8 2255.23  319.672253.506   331.5 2251.74
   339.1 2251.87  345.612253.508   348.8 2255.41     358 2263.48   375.2    2283
   380.6 2287.94   426.9 2312.26   440.4 2317.29   470.9 2324.87   533.1 2337.53
#Mann= 3 ,-1 , 0
       0      .1       0  319.67    .045       0  345.61      .1       0
#XS Ineff= 2 , 0
          307.19 2263.04
Permanent Ineff=
       F       F
Bank Sta=319.67,345.61
XS Rating Curve= 0 ,0
Exp/Cntr(USF)=0,0
Exp/Cntr=0.3,0.1

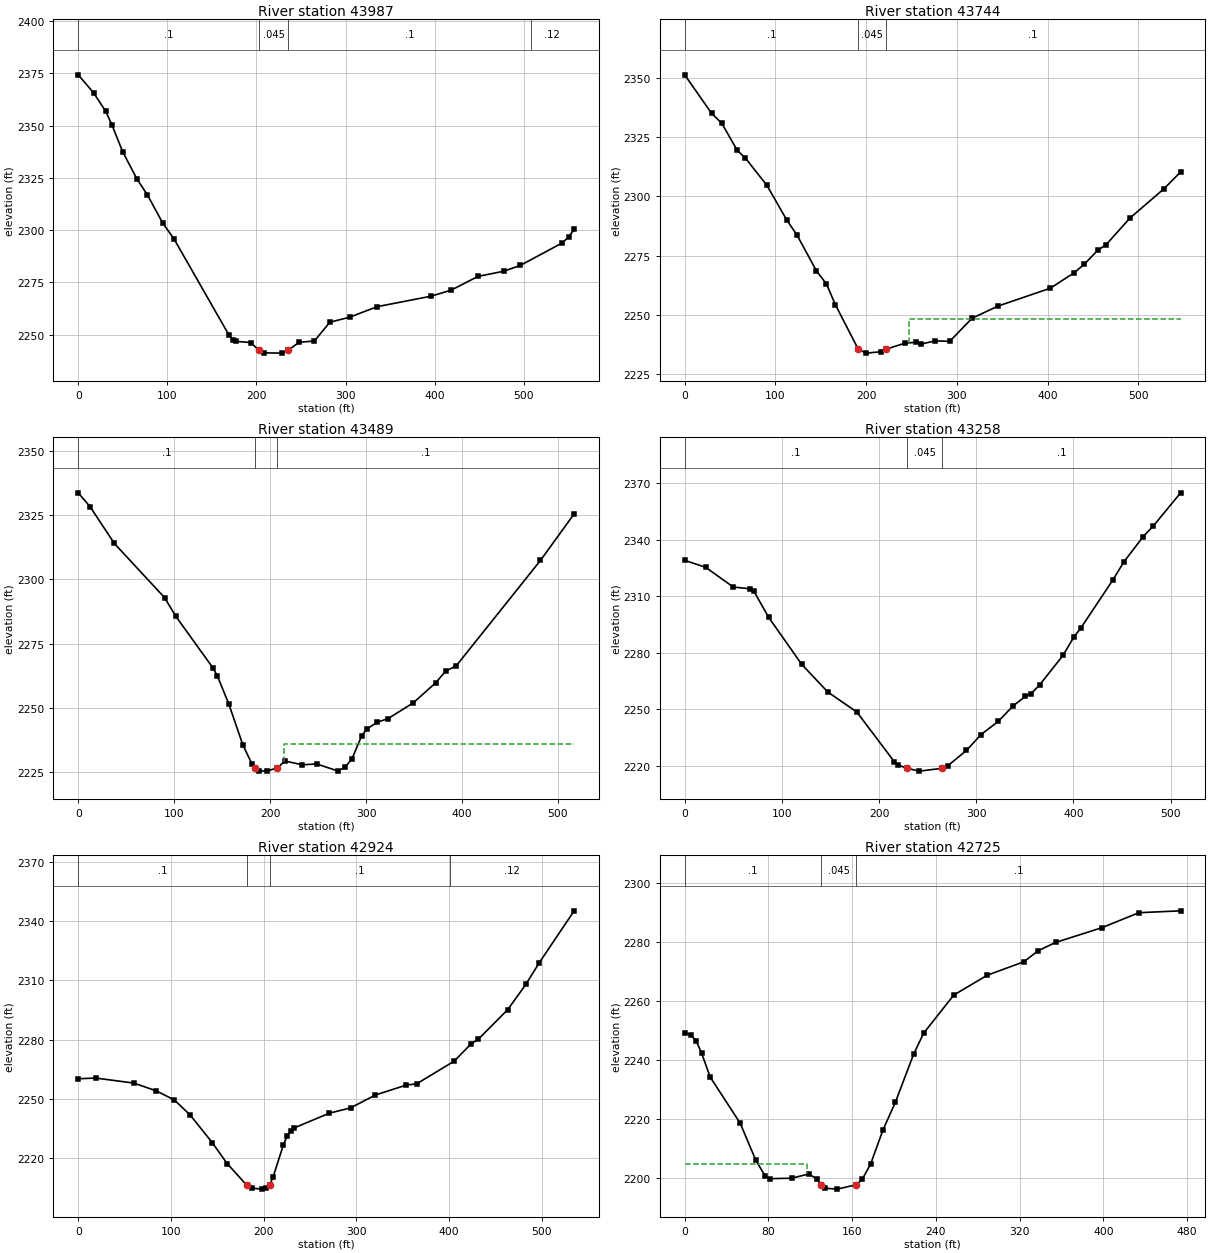
Type RM Length L Ch R = 1 ,43987   ,243.9,242.8,240.5
XS GIS Cut Line= 4
1957149.55507759225148.1661156921957218.56742927  225055.4923863
   1957366.45104224889.8627422821957524.19355811224738.035568599
#Sta/Elev= 30
       0 2374.25    17.3 2365.63    30.8 2356.86    37.9 2350.25      50 2337.41
      66 2324.39    77.7 2316.81      95 2303.26   107.3 2295.95   169.1 2249.88
     174 2247.33     177 2246.83   193.7 2246.27  202.762242.543   208.5 2241.34
   228.2 2241.21  235.492242.542   247.9 2246.41     265 2246.99   282.4 2255.99
   304.6 2258.39   335.4 2263.41   395.9 2268.42   418.6 2271.34   448.7  2277.9
   477.5 2280.36     496 2283.12   543.4 2293.95   550.7 2296.94   556.5 2300.41
#Mann= 4 ,-1 , 0
       0      .1       0  202.76    .045       0  235.49      .1       0
  507.59     .12       0
Bank Sta=202.76,235.49
XS Rating Curve= 0 ,0
Exp/Cntr(USF)=0,0
Exp/Cntr=0.3,0.1

Type RM Length L Ch R = 1 ,43744   ,255.4,254.4,249.3
XS GIS Cut Line= 4
1957336.87431785225319.711104139  1957407.858451225213.234904413
1957555.74206173225016.056756772 1957650.3875726224872.116708995
#Sta/Elev= 30
       0 2351.34    29.6 2335.12      41 2330.83      58  2319.4      67 2316.17
    90.7 2304.64   112.4 2290.13   123.8 2283.72   145.3 2268.55   156.3 2263.07
     166 2254.38  191.412235.455     200 2233.86   216.4 2234.44  221.512235.452
     243 2238.09   254.7  2238.4   260.2 2237.63   276.2 2239.04   292.2 2238.84
   316.8 2248.59   345.6 2253.75     403 2261.25   429.1 2267.72   440.7 2271.46
   455.1 2277.19   464.6 2279.65   490.7 2290.81   528.6 2303.33   546.7 2310.34
#Mann= 3 ,-1 , 0
       0      .1       0  191.41    .045       0  221.51      .1       0
#XS Ineff= 2 , 0
                          247.01         2248.32
Permanent Ineff=
       F       F
Bank Sta=191.41,221.51
XS Rating Curve= 0 ,0
Exp/Cntr(USF)=0,0
Exp/Cntr=0.3,0.1

Type RM Length L Ch R = 1 ,43489   ,227.4,231.1,231.8
XS GIS Cut Line= 4
1957553.77028025225459.7075889641957620.81085045225355.203170714
1957737.14595756225140.2789897861957812.07365366225012.113193819
#Sta/Elev= 30
       0 2333.64    12.4 2328.25    37.7 2313.94      90  2292.9   101.8  2285.6
   140.3 2265.65     145 2262.51   157.1 2251.42   171.6 2235.66   181.3 2228.05
  183.782226.816   188.8 2225.58   196.3 2225.44   207.5 2226.67   215.6 2229.37
   233.6 2227.89   248.5 2228.24   270.7  2225.5   278.1 2226.94   285.4 2230.22
   295.4  2239.1   300.7 2241.81   311.9 2244.46   323.1 2245.89   349.2 2251.97
   372.5 2259.72   383.1 2264.34     394 2266.35   481.9 2307.37     517 2325.46
#Mann= 3 ,-1 , 0
       0      .1       0  183.78    .045       0   207.5      .1       0
#XS Ineff= 2 , 0
                          214.67         2236.12
Permanent Ineff=
       F       F
Bank Sta=183.78,207.5
XS Rating Curve= 0 ,0
Exp/Cntr(USF)=0,0
Exp/Cntr=0.3,0.1

Type RM Length L Ch R = 1 ,43258   ,326.3,334.1,334.2
XS GIS Cut Line= 4
1957747.00486494225546.4659739261957814.04543514225434.074429771
1957910.66272748225256.6140968941957991.50576802225098.871578781
#Sta/Elev= 30
       0 2329.11    21.5 2325.43      50 2314.93    67.3 2314.01    71.2 2312.72
    86.4 2298.83   120.4 2273.87   147.3 2259.15   177.1 2248.55   215.7 2222.13
   219.7 2220.38   228.92218.653   241.5 2217.16  264.772218.653   270.5 2219.93
   289.9 2228.14   304.9  2236.6   322.8 2243.65   337.6 2251.69   350.5 2256.87
   356.1 2258.12   365.1 2262.91   389.3 2278.69   400.3 2288.35   407.7 2293.26
   440.3 2318.53   451.9 2328.35   471.7 2341.73   482.1 2347.35   510.2 2364.97
#Mann= 3 ,-1 , 0
       0      .1       0   228.9    .045       0  264.77      .1       0
Bank Sta=228.9,264.77
XS Rating Curve= 0 ,0
Exp/Cntr(USF)=0,0
Exp/Cntr=0.3,0.1

Type RM Length L Ch R = 1 ,42924   ,198.6,199.4,198.8
XS GIS Cut Line= 4
1957989.53398654225708.1520549911958046.71564936225601.675855265
1958153.19184908225420.2719594361958245.86557847225238.868063606
#Sta/Elev= 30
       0 2260.23    18.9 2260.57    60.1 2258.03    84.3 2254.06   103.7 2249.47
   120.9 2241.78   144.6 2227.84   160.6 2217.28  181.932206.211   187.3 2204.81
   198.7 2204.31   202.5 2204.63  206.392206.212   210.1 2210.35   221.3 2226.73
   225.3 2231.24   229.1 2233.87   232.9 2235.31   270.9 2242.79   293.8 2245.47
   320.4 2251.97   353.9 2257.03     365 2257.64   405.5 2269.14   423.9 2277.96
   431.6 2280.28   463.3 2295.27   482.8 2308.02   497.4 2319.09   534.9 2345.29
#Mann= 4 ,-1 , 0
       0      .1       0  181.93    .045       0  206.39      .1       0
   401.2     .12       0
Bank Sta=181.93,206.39
XS Rating Curve= 0 ,0
Exp/Cntr(USF)=0,0
Exp/Cntr=0.3,0.1

Type RM Length L Ch R = 1 ,42725   ,251.5,261,259.6
XS GIS Cut Line= 4
1958123.61512694225806.7411288121958192.62747861 225714.06739942
1958269.52695619225599.7040737891958417.41056692225436.046211247
#Sta/Elev= 30
       0 2249.27     5.6 2248.55    11.1 2246.38    16.2 2242.27    24.4 2234.15
      53 2218.51    67.9 2205.95      77 2200.48      82 2199.64   102.1 2199.79
   118.4  2201.2   126.3 2199.61  130.212197.577   134.2  2196.4   145.5 2196.08
  164.152197.577   169.8 2199.49   177.7 2204.63   189.5 2216.21   201.4 2225.66
   218.8 2241.98   228.3 2249.05   257.1 2262.03   289.1 2268.78     324 2273.34
   337.9 2277.13   354.4 2279.92   398.6 2284.93     434 2290.03   473.9 2290.67
#Mann= 3 ,-1 , 0
       0      .1       0  130.21    .045       0  164.15      .1       0
#XS Ineff= 2 , 0
          116.76 2204.78
Permanent Ineff=
       F       F
Bank Sta=130.21,164.15
XS Rating Curve= 0 ,0
Exp/Cntr(USF)=0,0
Exp/Cntr=0.3,0.1

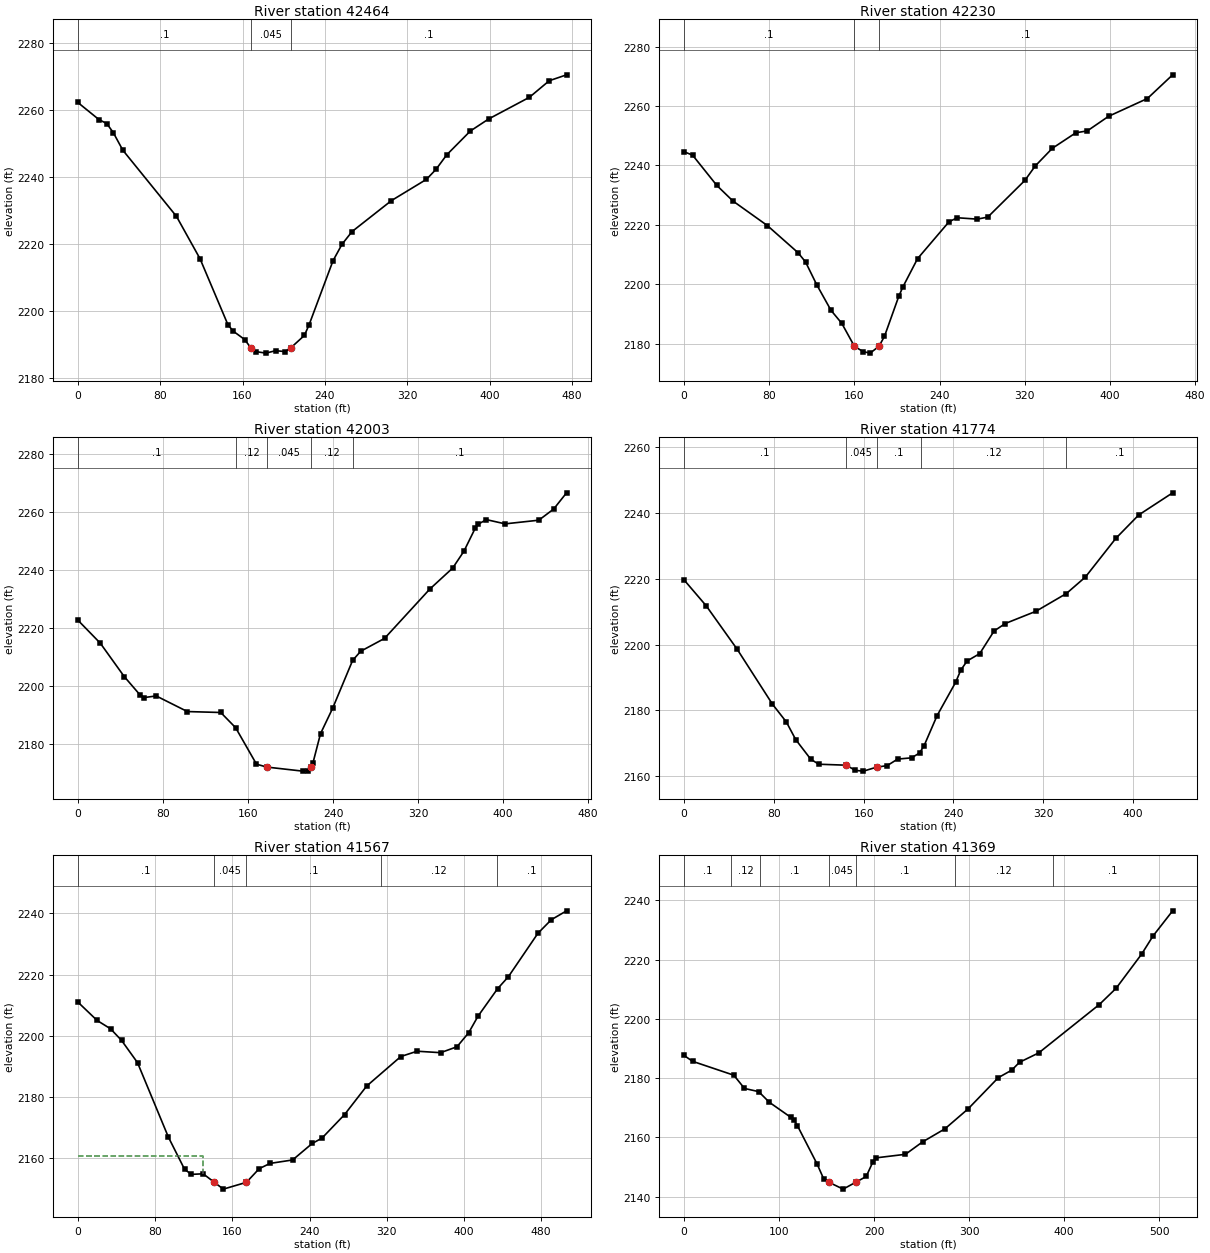
Type RM Length L Ch R = 1 ,42464   ,246.5,234,219.8
XS GIS Cut Line= 4
1958192.62747861226029.5524356461958279.38586357225940.822269207
1958391.77740773225826.4589435761958537.68923698225704.208492038
#Sta/Elev= 30
       0 2262.36    20.5 2257.26    28.1 2256.07    34.4 2253.38    43.7 2248.12
    95.8 2228.37   118.7 2215.72   145.8 2196.03   150.9 2194.11   162.1 2191.59
  168.072189.106   173.4 2187.97   182.8 2187.54   192.1 2188.27   201.5    2188
  206.842189.106   220.1 2192.83   224.7 2196.03   247.9 2215.12   256.7 2220.06
   266.4 2223.83   304.7 2233.08   338.6  2239.4   347.9 2242.37   358.4 2246.74
   381.3 2253.84   399.1 2257.44   438.7 2263.91     458 2268.86   474.8 2270.62
#Mann= 3 ,-1 , 0
       0      .1       0  168.07    .045       0  206.84      .1       0
Bank Sta=168.07,206.84
XS Rating Curve= 0 ,0
Exp/Cntr(USF)=0,0
Exp/Cntr=0.3,0.1

Type RM Length L Ch R = 1 ,42230   ,216.8,226.5,232.9
XS GIS Cut Line= 4
1958437.12838168226181.3796093291958496.28182598226078.846972556
1958521.91498517225952.6529580661958646.13721818225781.107969618
#Sta/Elev= 30
       0 2244.64     8.1 2243.49    30.9 2233.29      46 2228.06    78.3 2219.81
   107.1 2210.69   114.2 2207.56   124.7  2199.9   138.1 2191.29   148.2 2186.93
  160.042179.218   168.2 2177.41   174.9  2176.9  183.172179.219   188.3 2182.53
   201.7 2195.96   205.5 2199.09   219.4 2208.68   248.9 2221.06   256.6 2222.43
   275.4 2221.96   285.3 2222.64   320.1 2234.96   329.9 2239.84   345.9 2245.77
     368    2251   378.8 2251.64   398.8 2256.55   435.2 2262.52   458.9 2270.49
#Mann= 3 ,-1 , 0
       0      .1       0  160.04    .045       0  183.17      .1       0
Bank Sta=160.04,183.17
XS Rating Curve= 0 ,0
Exp/Cntr(USF)=0,0
Exp/Cntr=0.3,0.1

Type RM Length L Ch R = 1 ,42003   ,212,229.4,238.4
XS GIS Cut Line= 4
1958618.53227751226277.9969016731958681.62928476226165.605357518
1958764.44410677226019.6935282631958823.59755106 225867.86635458
#Sta/Elev= 30
       0 2222.68    21.1 2214.74    43.6 2203.25    58.7 2196.82    62.4 2196.01
    73.7 2196.56     103 2191.18   134.4 2190.86   148.4 2185.61     168 2173.05
   177.82172.052   211.4 2170.66   216.9 2170.82  219.192172.052     221 2173.35
   228.2 2183.55   239.6  2192.3   258.4  2208.8     266 2211.96   288.4 2216.38
     331 2233.38   352.5 2240.62   363.1 2246.43   373.7 2254.34   376.6 2255.75
   384.2 2257.31   401.8 2255.85   433.5 2257.11   447.5 2260.96   459.6 2266.54
#Mann= 5 ,-1 , 0
       0      .1       0  148.89     .12       0   177.8    .045       0
  219.19     .12       0  258.89      .1       0
Bank Sta=177.8,219.19
XS Rating Curve= 0 ,0
Exp/Cntr(USF)=0,0
Exp/Cntr=0.3,0.1

Type RM Length L Ch R = 1 ,41774   ,205.2,207.1,201.9
XS GIS Cut Line= 4
1958725.00847724226376.5859754931958795.99261039226319.404312677
1958939.93265817226212.9281129511958981.34006917226053.213813362
#Sta/Elev= 30
       0 2219.71    19.8 2211.81    47.5 2198.54    78.8  2181.9    91.2 2176.48
    99.6 2171.09   112.9 2165.17     120 2163.63  144.482163.334   152.7 2161.75
   159.9 2161.53   171.6 2162.74     181  2163.2   190.3 2165.19   202.7 2165.57
   209.8 2167.04   213.9 2169.29   225.5 2178.44     242 2188.56   246.6 2192.29
   252.3 2195.05   263.4 2197.25   276.2 2204.14   286.2 2206.41   313.5 2210.13
   340.6 2215.53   357.5 2220.53   384.6 2232.29     405 2239.41   435.2 2246.14
#Mann= 5 ,-1 , 0
       0      .1       0  144.48    .045       0   171.6      .1       0
  211.15     .12       0  340.19      .1       0
Bank Sta=144.48,171.6
XS Rating Curve= 0 ,0
Exp/Cntr(USF)=0,0
Exp/Cntr=0.3,0.1

Type RM Length L Ch R = 1 ,41567   ,211.1,197.9,182.1
XS GIS Cut Line= 4
1958821.62576958226565.8769972281958894.58168421 226498.83642703
1959030.63460608226388.4166643521959139.08258729226183.351390805
#Sta/Elev= 30
       0 2211.05      20 2205.03    33.9 2202.31    45.3 2198.51    61.8 2191.26
    93.8 2166.92   110.6 2156.39   117.6 2154.75   129.8 2154.94  141.432152.151
   150.7 2149.93  174.63 2152.15   187.9 2156.62   199.2 2158.34   222.5 2159.46
   242.8 2164.85   252.9 2166.59   276.3 2174.28   299.2  2183.6   334.6 2193.26
   351.5 2194.99   375.8 2194.51   392.8 2196.45   404.9 2201.03   414.6 2206.45
   434.8  2215.4     446 2219.32   476.7 2233.55   490.5 2237.95   506.3 2240.86
#Mann= 5 ,-1 , 0
       0      .1       0  141.43    .045       0  174.63      .1       0
   314.3     .12       0   434.3      .1       0
#XS Ineff= 2 , 0
           129.8 2160.61
Permanent Ineff=
       F       F
Bank Sta=141.43,174.63
XS Rating Curve= 0 ,0
Exp/Cntr(USF)=0,0
Exp/Cntr=0.3,0.1

Type RM Length L Ch R = 1 ,41369   ,164.1,192.8,208.9
XS GIS Cut Line= 4
1959026.69104313226705.8734820531959081.90092447226605.312626756
1959135.13902433226439.6829827381959219.92562782226230.674146239
#Sta/Elev= 30
       0 2187.67     9.1 2185.66    52.5 2180.97    63.7  2176.5    78.6 2175.43
    89.9 2171.82   112.3 2166.78     116 2165.73   119.4 2163.93   140.1 2150.99
     147 2145.99  152.372144.845   167.5  2142.5  180.942144.845   191.8 2146.77
   198.7 2151.62   202.1 2153.06   233.1 2154.26   251.1 2158.45   274.6 2162.86
   298.9 2169.57   330.8 2180.15   344.9 2182.68   353.1 2185.34   373.3  2188.5
     437 2204.82   454.7 2210.31   481.6 2221.87   493.6    2228   514.2 2236.48
#Mann= 7 ,-1 , 0
       0      .1       0      50     .12       0      80      .1       0
  152.37    .045       0  180.94      .1       0  284.72     .12       0
   388.7      .1       0
Bank Sta=152.37,180.94
XS Rating Curve= 0 ,0
Exp/Cntr(USF)=0,0
Exp/Cntr=0.3,0.1

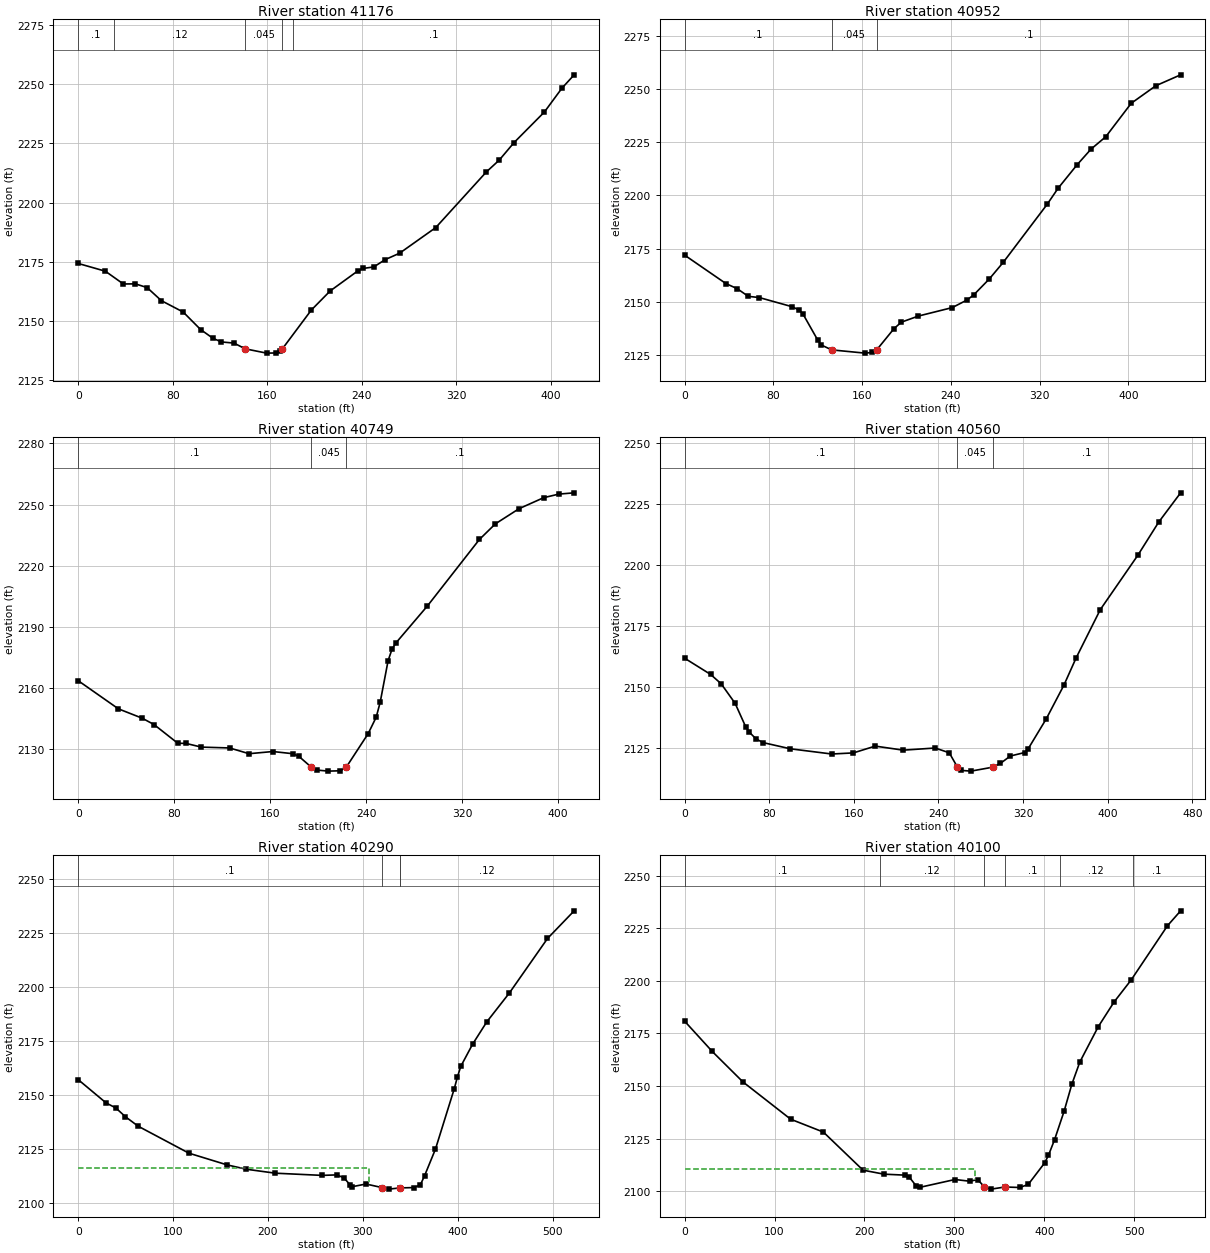
Type RM Length L Ch R = 1 ,41176   ,212.8,223.9,230.9
XS GIS Cut Line= 4
1959089.78805038226755.1680189631959156.82862057 226707.84526353
1959288.93797949226654.6071636671959484.14434566226644.748256285
#Sta/Elev= 30
       0 2174.26      23 2170.98    38.2 2165.59    48.4 2165.63    58.3 2164.07
    70.4 2158.54    88.9 2153.71   103.6 2146.33   114.2 2142.58   121.3 2141.08
   131.9 2140.59  141.422138.169   159.5 2136.35   167.3 2136.42   170.8 2137.07
  172.862138.169   197.4 2154.58   213.3 2162.63     237 2171.21   240.8 2172.13
   250.2 2172.78     260 2175.91   272.1 2178.59   302.7 2189.42   345.5 2212.92
   356.5 2217.97     369 2225.36   394.7 2238.29   409.6 2248.39   419.9 2254.01
#Mann= 5 ,-1 , 0
       0      .1       0      30     .12       0  141.42    .045       0
  172.86     .12       0  182.06      .1       0
Bank Sta=141.42,172.86
XS Rating Curve= 0 ,0
Exp/Cntr(USF)=0,0
Exp/Cntr=0.3,0.1

Type RM Length L Ch R = 1 ,40952   ,199.8,203.2,205.8
XS GIS Cut Line= 4
 1959054.2959838226885.3055964061959135.13902433226895.164503788
1959334.28895345226893.1927223121959499.91859747226908.966974123
#Sta/Elev= 30
       0 2171.91    37.2 2158.57    47.4 2156.17    57.3 2152.59    67.2 2152.02
    96.9 2147.71   103.4 2146.07   106.7 2144.23   119.8 2132.17   123.1 2129.76
   132.52127.454   162.5 2125.93     169 2126.25  173.072127.456   188.7 2137.45
   195.3 2140.46   210.6 2143.33   241.2 2147.31   254.3 2150.82   260.4  2153.2
   274.5 2160.71   287.2 2168.59   326.7 2195.78   336.6 2203.35   353.8 2214.42
   366.3 2221.72   379.5 2227.49   402.5 2243.22   424.7 2251.46     447 2256.57
#Mann= 3 ,-1 , 0
       0      .1       0   132.5    .045       0  173.07      .1       0
Bank Sta=132.5,173.07
XS Rating Curve= 0 ,0
Exp/Cntr(USF)=0,0
Exp/Cntr=0.3,0.1

Type RM Length L Ch R = 1 ,40749   ,186.3,189.5,192.2
XS GIS Cut Line= 4
1959018.80391722227070.6530551881959137.11080581227082.483744047
1959310.62757573227106.1451217641959428.93446432227121.919373575
#Sta/Elev= 30
       0  2163.6    33.5 2149.79    53.3 2145.21    63.2 2142.08      83 2132.91
    89.8 2132.83   102.7 2131.01   126.2  2130.6   142.4 2127.78   162.3 2128.85
   178.8 2127.78   183.9  2126.5  194.262121.195   198.7 2119.76   208.6 2119.23
   218.6 2119.41  223.472121.195   241.7 2137.63   248.4 2145.71   251.7 2152.99
   258.3 2173.39   261.6 2179.12   264.9 2182.18   291.1 2200.29   334.4 2232.89
   347.7 2240.55   367.5 2248.02     388 2253.41   400.6 2255.16   413.4 2255.79
#Mann= 3 ,-1 , 0
       0      .1       0  194.26    .045       0  223.47      .1       0
Bank Sta=194.26,223.47
XS Rating Curve= 0 ,0
Exp/Cntr(USF)=0,0
Exp/Cntr=0.3,0.1

Type RM Length L Ch R = 1 ,40560   ,286.6,270,249.3
XS GIS Cut Line= 4
1958916.27128045227236.2826992071959133.16724286227265.859421353
1959255.41769439227297.4079249751959377.66814593227317.125739739
#Sta/Elev= 30
       0 2161.86    24.5 2155.23    34.5 2151.39    47.7 2143.37    57.7 2133.75
      61 2131.59    67.6 2128.74    74.2 2127.26     100 2124.72   139.1 2122.59
   159.5 2123.04   180.2 2125.83   206.7 2124.17   236.9 2125.05   250.2 2123.09
  257.992117.172   260.9 2115.89   270.7 2115.57  291.152117.172   298.6 2118.75
     308 2121.77   321.6  2123.2     325 2124.84   341.9 2136.98   358.6 2150.79
   370.1 2161.92     393 2181.77   428.4    2204   448.3  2217.7     469 2229.69
#Mann= 3 ,-1 , 0
       0      .1       0  257.99    .045       0  291.15      .1       0
Bank Sta=257.99,291.15
XS Rating Curve= 0 ,0
Exp/Cntr(USF)=0,0
Exp/Cntr=0.3,0.1

Type RM Length L Ch R = 1 ,40290   ,191,189.1,183.3
XS GIS Cut Line= 4
1958928.10196931227638.5261203941959133.16724286227595.146927913
1959324.43004607227476.8400393281959401.32952365227433.460846847
#Sta/Elev= 30
       0  2157.2    29.5 2146.37    39.6  2144.1    49.6 2140.07    63.1 2135.64
   116.7 2123.11     157 2117.67   177.4 2115.65   207.8 2113.83   257.1 2112.81
   272.4 2113.04   280.2  2111.7   286.7 2108.31   289.1 2107.59   303.4 2108.81
   320.1 2107.17   327.3 2106.44   339.2    2107   353.6 2107.16   360.6 2108.35
   365.1 2112.62   376.6    2125   396.4 2152.96   399.8 2158.52   403.3 2163.37
   415.8 2173.68   430.7 2183.98   454.6 2197.43   494.7 2222.64   522.8 2235.47
#Mann= 4 ,-1 , 0
       0      .1       0   320.1    .045       0   339.2      .1       0
   339.6     .12       0
#XS Ineff= 2 , 0
          306.02 2116.43
Permanent Ineff=
       F       F
Bank Sta=320.1,339.2
XS Rating Curve= 0 ,0
Exp/Cntr(USF)=0,0
Exp/Cntr=0.3,0.1

Type RM Length L Ch R = 1 ,40100   ,200.1,194.6,183.1
XS GIS Cut Line= 4
1959111.47764662 227920.490871521959243.58700553227760.776571931
1959411.18843103227616.8365241531959466.39831237227506.416761474
#Sta/Elev= 30
       0  2180.8    30.6 2166.45    64.8 2151.93   117.9 2134.19   154.3 2128.06
   198.4 2109.94   221.7 2108.04   245.3 2107.57   249.6 2106.78   257.6  2102.4
     262 2101.81   300.7  2105.5   317.1 2104.68   325.9 2105.46   333.4 2102.03
     341 2100.92   356.1 2101.93   372.9  2101.7   382.2 2103.16   400.3 2113.31
   404.7 2117.01   411.5 2124.47     422 2137.87   430.7 2150.84   439.6 2161.41
     460 2178.15   477.7 2189.98   496.7 2200.45   537.1 2226.25   551.7 2233.33
#Mann= 6 ,-1 , 0
       0      .1       0  217.27     .12       0   333.4    .045       0
   356.1      .1       0  417.27     .12       0   498.2      .1       0
#XS Ineff= 2 , 0
          323.21 2110.35
Permanent Ineff=
       F       F
Bank Sta=333.4,356.1
XS Rating Curve= 0 ,0
Exp/Cntr(USF)=0,0
Exp/Cntr=0.3,0.1

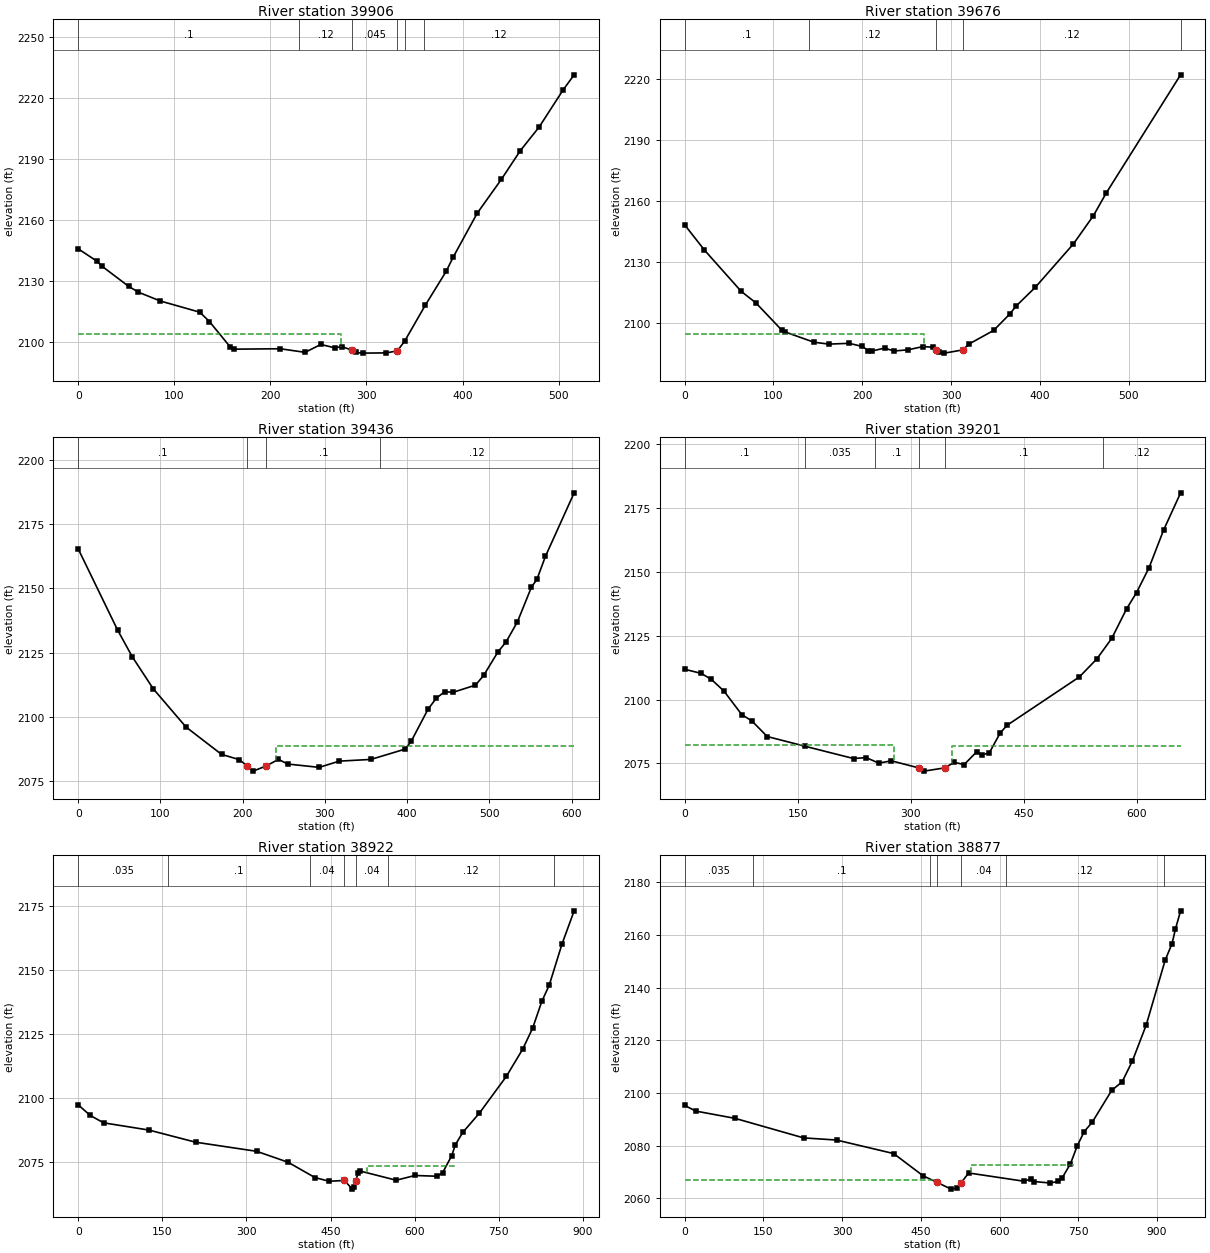
Type RM Length L Ch R = 1 ,39906   ,229.8,230.4,230.3
XS GIS Cut Line= 4
1959385.55527184228028.9388527221959434.84980875227930.349778902
 1959547.2413529227691.7642202571959604.42301572227561.626642814
#Sta/Elev= 30
       0 2146.06    19.4 2139.98    24.7 2137.52    52.4 2127.61    62.7 2124.71
    85.4  2120.4   126.5 2114.89   136.5 2110.31   158.2  2097.8   161.9 2096.71
   210.3 2096.91   236.1 2095.15   252.5 2099.02     267 2097.37   274.4    2098
   285.2  2096.1   288.8 2095.09     296 2094.76   320.8 2094.88  332.132095.886
   339.6 2100.56   361.3  2118.4   382.9 2134.96   390.1 2141.85   415.2 2163.55
   440.3 2180.17   460.1 2194.33   479.7 2205.96   504.9 2224.39   516.1 2231.61
#Mann= 6 ,-1 , 0
       0      .1       0  230.23     .12       0   285.2    .045       0
  332.13     .12       0  340.23      .1       0  360.23     .12       0
#XS Ineff= 2 , 0
          273.35 2104.35
Permanent Ineff=
       F       F
Bank Sta=285.2,332.13
XS Rating Curve= 0 ,0
Exp/Cntr(USF)=0,0
Exp/Cntr=0.3,0.1

Type RM Length L Ch R = 1 ,39676   ,238.1,240,238
XS GIS Cut Line= 4
1959584.70520095228143.302178354 1959647.8022082228009.221037958
1959766.10909678227752.8894460251959787.79869302227626.695431535
#Sta/Elev= 30
       0 2148.28    22.3  2135.9    63.6  2115.7    80.3 2109.98   109.3 2096.68
   112.9 2095.79   145.6 2090.73   162.3  2089.8   185.3 2090.19   199.8 2088.68
   206.8 2086.66   210.6  2086.4   225.1 2087.83   235.9 2086.43   251.3 2086.99
   268.4 2088.59   279.3 2088.28   282.9 2086.92   286.5 2085.73   292.6 2085.38
   313.1 2086.95   320.5 2089.91   347.9  2096.5     366 2104.49   373.2 2108.44
   394.9 2117.66   437.9 2138.99   460.4 2152.84   474.6 2163.78   558.5 2221.87
#Mann= 5 ,-1 , 0
       0      .1       0     140     .12       0   282.9    .045       0
   313.1     .12       0  558.55      .1       0
#XS Ineff= 2 , 0
          269.05 2094.96
Permanent Ineff=
       F       F
Bank Sta=282.9,313.1
XS Rating Curve= 0 ,0
Exp/Cntr(USF)=0,0
Exp/Cntr=0.3,0.1

Type RM Length L Ch R = 1 ,39436   ,234.3,235,230.9
XS GIS Cut Line= 4
1959762.16553383228261.6090669381959833.14966698228109.781893255
1959915.96448899227883.0270234681959967.23080738227695.707783209
#Sta/Elev= 30
       0 2165.31    47.8 2133.85    65.9 2123.33    91.3 2110.96   131.1 2096.12
   174.3  2085.5   195.8 2083.46   205.12081.135   212.7 2078.99  228.53 2080.98
   243.6 2083.56   254.7 2081.75   293.1 2080.45   317.5 2082.87     356 2083.54
   397.9 2087.57   404.9 2090.51   425.4 2102.99   435.6 2107.36   445.8 2109.82
     456 2109.62   483.2 2112.39   493.2 2116.19   510.4 2125.24   520.6 2129.28
   534.2 2136.97   551.2 2150.42     558 2153.53   568.2 2162.36   603.2 2187.09
#Mann= 4 ,-1 , 0
       0      .1       0   205.1    .045       0  228.53      .1       0
   367.6     .12       0
#XS Ineff= 2 , 0
                          240.69         2088.91
Permanent Ineff=
       F       F
Bank Sta=205.1,228.53
XS Rating Curve= 0 ,0
Exp/Cntr(USF)=0,0
Exp/Cntr=0.3,0.1

Type RM Length L Ch R = 1 ,39201   ,261.4,278.3,284.8
XS GIS Cut Line= 4
1959988.92040362228364.1417037111960038.21494053228157.104648689
1960081.59413301227918.5190900431960105.25551072 227717.39737945
#Sta/Elev= 30
       0 2111.89    21.8  2110.3    35.3 2107.97    52.1 2103.36    75.7 2094.15
    89.2 2091.64   109.5 2085.56     160 2081.72     224 2076.94   240.7 2077.31
   257.3 2075.16   274.3 2076.03     311 2073.24   317.4 2072.01   344.9 2073.28
   357.4 2075.45   370.7 2074.58   387.4  2079.6   394.1 2078.37   404.1 2079.18
   418.2 2086.81   427.4 2089.93   523.5  2108.9   546.6 2115.92   566.4 2123.97
   586.2  2135.6   599.4 2141.96     616 2151.73   635.2  2166.4   657.8    2181
#Mann= 6 ,-1 , 0
       0      .1       0     160    .035       0  252.82      .1       0
     311    .045       0   344.9      .1       0  555.32     .12       0
#XS Ineff= 2 , 0
          277.79 2082.22  354.01         2081.91
Permanent Ineff=
       F       F
Bank Sta=311,344.9
XS Rating Curve= 0 ,0
Exp/Cntr(USF)=0,0
Exp/Cntr=0.5,0.3

Type RM Length L Ch R = 1 ,38922   ,42.3,45.6,52.4
XS GIS Cut Line= 4
1960049.02491201 228463.08050504 1960252.1335868228126.722190105
1960373.74005451228014.1715231851960376.32742616227688.162694863
#Sta/Elev= 30
       0 2097.19    21.5 2093.03    45.4 2090.15   126.1 2087.33   209.3 2082.59
   318.3 2079.02   374.1 2074.77   422.3 2068.76   447.6 2067.31   474.9 2067.63
   488.9 2064.24   492.3 2065.16  494.912067.541   499.6 2070.68   502.8 2071.31
   567.3 2067.72   600.6 2069.57   639.9 2069.28   649.9 2070.62   666.2  2077.3
   672.7 2081.57   685.9 2086.41   715.4 2093.89   763.6 2108.29   792.9 2118.98
   810.5 2127.13     827 2137.68   840.1 2143.94     863 2160.09   884.6 2173.02
#Mann= 7 ,-1 , 0
       0    .035       0     160      .1       0  412.92     .04       0
   474.9    .045       0  494.91     .04       0  552.92     .12       0
  848.62      .1       0
#XS Ineff= 3 ,-1
       0     464 2066.83  503.88  509.92  2067.1  514.33  673.35  2073.3
Permanent Ineff=
       F       F       F
Bank Sta=474.9,494.91
XS Rating Curve= 0 ,0
Exp/Cntr(USF)=0,0
Exp/Cntr=0.5,0.3

Type RM Length L Ch R = 1 ,38877   ,75.8,53.8,42.3
XS GIS Cut Line= 4
1960064.54914193  228509.65319481960301.29364822228130.603247585
1960404.78851435228059.4505271181960400.90745687227686.869009037
#Sta/Elev= 30
       0 2095.29    21.1 2093.14      96 2090.38   226.7 2082.97   289.4 2082.16
   398.2 2077.03   454.3  2068.6  481.352066.073   507.6 2063.54   519.6 2063.94
     526 2065.71   541.1 2069.67   646.4 2066.54   659.7  2067.4   666.3 2066.41
   695.8 2065.87   712.2 2066.44   718.8 2067.59   735.2 2073.17   748.3 2080.04
   761.4 2085.36   776.7 2088.93   813.9 2101.04   833.6  2104.2   853.3 2112.18
   879.6 2125.82   915.6 2150.34   928.8 2156.68   935.3 2162.24   945.1 2169.09
#Mann= 7 ,-1 , 0
       0    .035       0     130      .1       0  466.91     .04       0
  481.35    .045       0     526     .04       0   612.5     .12       0
   912.5      .1       0
#XS Ineff= 3 ,-1
       0     480 2066.83  536.68  540.36 2066.66  545.85  746.42 2072.78
Permanent Ineff=
       F       F       F
Bank Sta=481.35,526
XS Rating Curve= 0 ,0
Exp/Cntr(USF)=0,0
Exp/Cntr=0.5,0.3