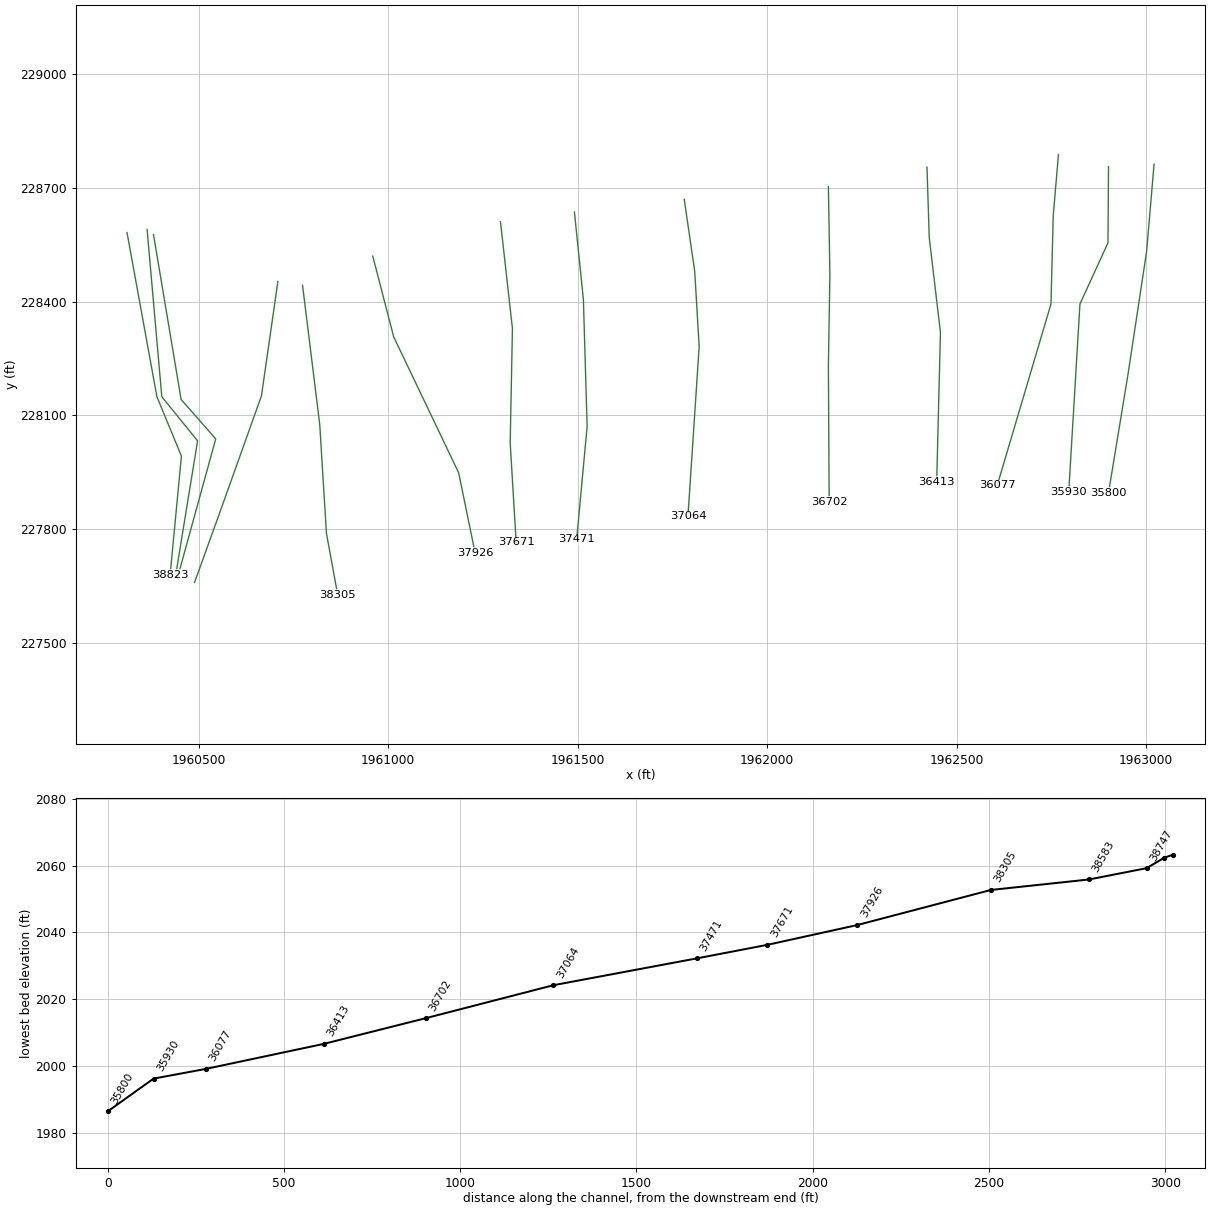
HEC-RAS study LTBLUESTRV.prj: LTBLUESTRV

--- LTBLUESTRV.g01 (geometry) --- (continued)

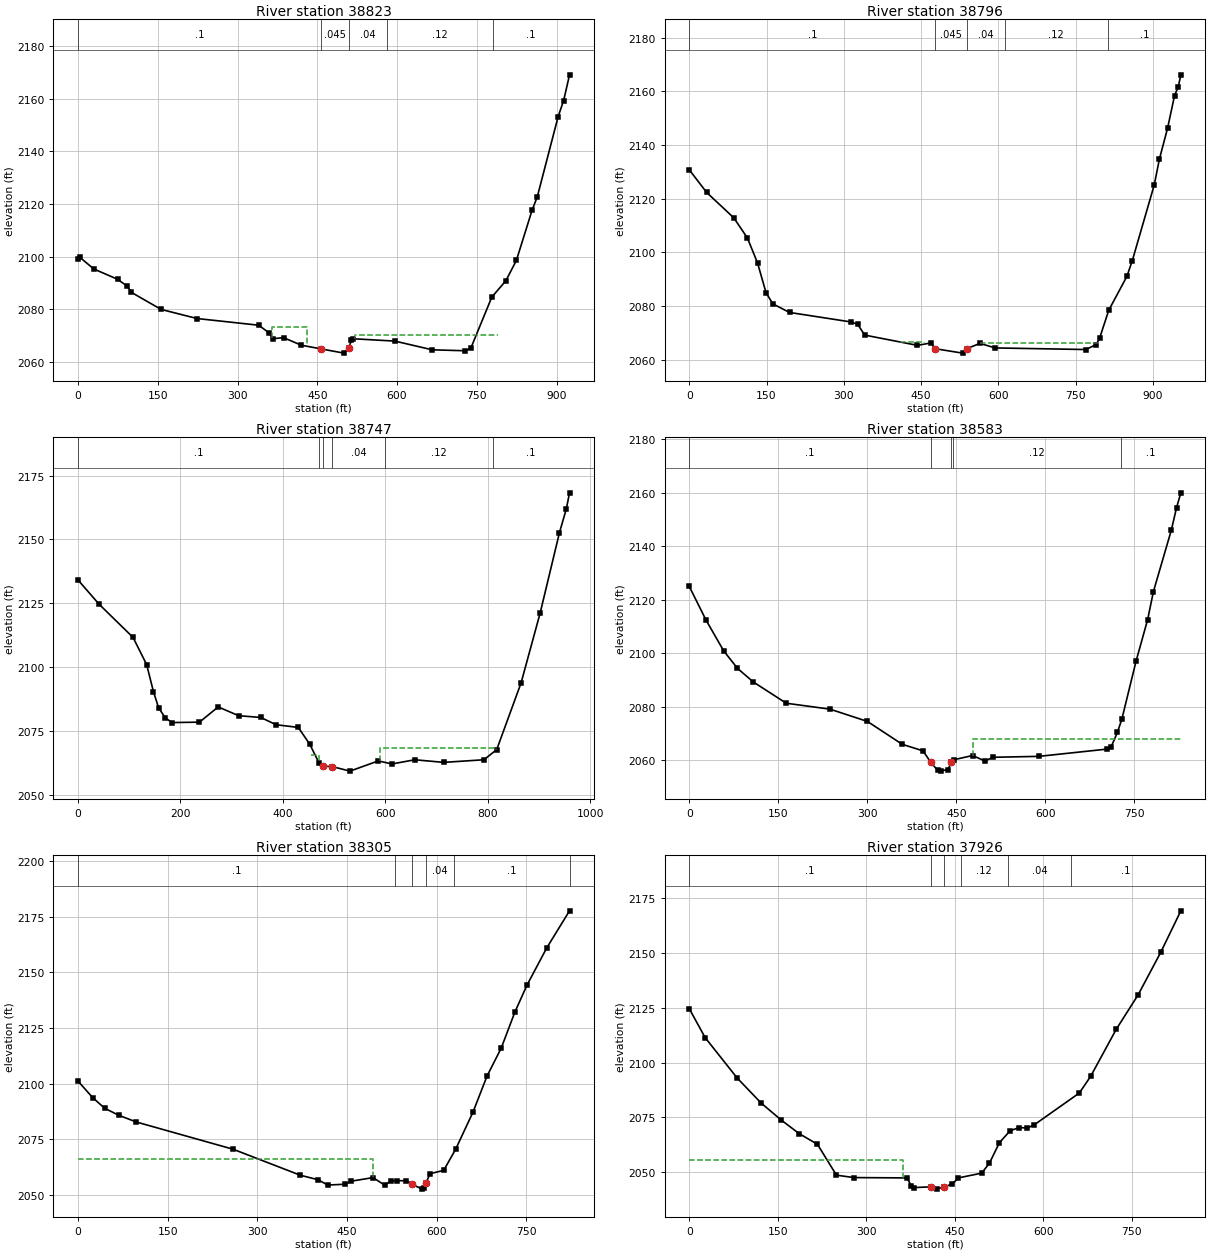
Type RM Length L Ch R = 1 ,38823   ,17,26.5,50.6
XS GIS Cut Line= 4
  1960310.349449228582.0996010941960389.26428443228148.714849158
1960453.94857576227992.1788641311960424.19380175227679.106894077
#Sta/Elev= 30
       0 2099.16       3 2099.85    29.6 2095.36    74.4 2091.43      93 2088.73
   100.6 2086.43   156.2 2079.98   223.9 2076.51   339.8 2073.97   359.4 2071.05
   366.5 2068.83   386.5 2069.25   419.8 2066.38   457.4 2064.96   500.1 2063.36
  508.89 2065.14   514.3  2068.3   517.9 2068.82     596 2067.93   666.2 2064.62
   728.3 2064.26   738.7 2065.21   778.2 2084.65   804.6 2090.86   824.4 2098.59
     854  2117.7   863.8 2122.82   902.9 2153.21   913.3 2159.36   924.4 2169.13
#Mann= 5 ,-1 , 0
       0      .1       0   457.4    .045       0  508.89     .04       0
  580.51     .12       0  779.89      .1       0
#XS Ineff= 2 ,-1
  365.33   429.8 2073.16  520.06   789.4 2070.43
Permanent Ineff=
       F       F
Bank Sta=457.4,508.89
XS Rating Curve= 0 ,0
Exp/Cntr(USF)=0,0
Exp/Cntr=0.5,0.3

Type RM Length L Ch R = 1 ,38796   ,58.9,49.7,70.7
XS GIS Cut Line= 4
 1960363.3905679228589.861716054 1960402.2011427228148.714849158
1960496.64020804228032.2831247581960438.42434584227675.225836596
#Sta/Elev= 30
       0 2130.75    33.8  2122.3    86.5 2112.83   112.8 2105.35   132.6 2095.98
     149 2084.93   162.2 2080.75   194.7 2077.55   313.9 2074.01   326.9 2073.11
   340.8  2069.1   442.9 2065.28   469.2 2066.18  477.852064.013   530.7 2062.38
   539.2 2064.07   564.5 2066.02   593.8 2064.32     770 2063.72   789.9 2065.55
   796.6 2067.85   814.5 2078.36   849.7 2090.98   860.3 2096.91   902.9 2125.15
   912.9 2134.76   928.9 2146.42   942.3 2158.44   949.5 2161.73   954.5 2166.18
#Mann= 5 ,-1 , 0
       0      .1       0  477.85    .045       0   539.2     .04       0
  612.77     .12       0  812.77      .1       0
#XS Ineff= 4 ,-1
  408.61  455.16 2066.49  460.98  470.68 2063.61  552.14  559.26 2063.61
  565.08  799.77 2066.21
Permanent Ineff=
       F       F       F       F
Bank Sta=477.85,539.2
XS Rating Curve= 0 ,0
Exp/Cntr(USF)=0,0
Exp/Cntr=0.5,0.3

Type RM Length L Ch R = 1 ,38747   ,181.9,163.6,106.4
XS GIS Cut Line= 4
1960380.20848364228576.9248577871960453.18466722228141.605541003
1960544.50658363228037.4578680651960443.59908915227671.049133095
#Sta/Elev= 30
       0 2134.14    41.3 2124.62   107.5 2111.65   134.1 2100.98   147.4 2090.38
   157.4 2084.09   170.7 2080.07     184 2078.29   237.2 2078.45   273.8 2084.42
   313.7 2080.98     357 2080.29   386.9 2077.44   430.2 2076.39   452.9 2069.73
   470.3 2062.61  478.182061.175   496.2 2061.07   531.1 2059.27   586.3 2063.26
   613.5 2062.09   657.8 2063.72   714.3  2062.7   792.7 2063.72   817.7 2067.67
   865.4 2093.86   902.8 2121.36   940.2  2152.6   953.8 2162.05     960 2168.27
#Mann= 6 ,-1 , 0
       0      .1       0  471.39     .04       0  478.18    .045       0
   496.2     .04       0  599.91     .12       0  809.91      .1       0
#XS Ineff= 2 ,-1
  454.61  471.452065.769  589.84  816.232068.381
Permanent Ineff=
       F       F
Bank Sta=478.18,496.2
XS Rating Curve= 0 ,0
Exp/Cntr(USF)=0,0
Exp/Cntr=0.5,0.3

Type RM Length L Ch R = 1 ,38583   ,273.2,278,288
XS GIS Cut Line= 4
1960708.62064251 228452.871870151960665.24145002228151.189304259
1960556.79346882227847.5349568931960488.56982974227658.441113305
#Sta/Elev= 30
       0 2124.94    28.2 2112.37      58 2100.84    81.2 2094.32   107.7 2089.25
   163.4 2081.27     237 2079.06     300 2074.48   358.9  2065.9   393.8 2063.46
  406.882059.164   418.3 2056.21   423.3 2055.88   435.6 2056.48   441.52059.162
   446.5 2060.17   477.3 2061.72   497.9  2059.7   512.2 2061.06   588.9  2061.4
   703.9 2064.12   710.8 2064.97   721.4  2070.4   728.8 2075.31   752.8 2097.04
   772.3 2112.58     782 2123.04   812.1 2145.95     821 2154.44   828.2 2159.96
#Mann= 5 ,-1 , 0
       0      .1       0  406.88    .045       0   441.5     .04       0
  444.79     .12       0  727.22      .1       0
#XS Ineff= 2 , 0
                          478.51         2067.89
Permanent Ineff=
       F       F
Bank Sta=406.88,441.5
XS Rating Curve= 0 ,0
Exp/Cntr(USF)=0,0
Exp/Cntr=0.3,0.1

Type RM Length L Ch R = 1 ,38305   ,370.1,378.8,385.9
XS GIS Cut Line= 4
1960773.68943123228443.0129627681960819.04040518228076.261608156
1960836.78643847227788.3815126011960866.36316062227626.695431535
#Sta/Elev= 30
       0 2101.19    24.8 2093.71    44.6 2089.02    67.8 2085.91    97.5 2082.85
   259.5 2070.63   371.9 2058.98   401.5 2056.95   417.9 2054.57   447.5 2054.94
   457.3 2056.31   493.5 2057.91   513.2 2054.52   523.1 2056.34   532.9 2056.59
   549.4 2056.44   559.2 2054.89   575.7 2052.74     579 2053.32  582.022055.336
   588.8 2059.65   611.8 2061.14   631.6 2070.53   660.8 2087.26   684.5 2103.57
   707.9 2115.89   731.1 2132.28   751.2 2144.26   784.2 2160.92   822.3 2177.55
#Mann= 6 ,-1 , 0
       0      .1       0  529.54     .04       0   559.2    .045       0
  582.02     .04       0  629.54      .1       0  822.34     .12       0
#XS Ineff= 2 , 0
          494.27  2066.1
Permanent Ineff=
       F       F
Bank Sta=559.2,582.02
XS Rating Curve= 0 ,0
Exp/Cntr(USF)=0,0
Exp/Cntr=0.3,0.1

Type RM Length L Ch R = 1 ,37926   ,266.5,255.7,247.2
XS GIS Cut Line= 4
1960959.03689001228519.9124403481961014.24677135228306.960040896
 1961185.7917598 227948.095812191961229.17095228227737.115194214
#Sta/Elev= 30
       0 2124.59    26.9 2111.38    81.1 2092.97   121.8 2081.51   155.7 2073.79
   186.2 2067.57   217.2 2062.69   249.4 2048.61     279  2047.5   369.2 2047.35
   376.5  2043.5   380.1 2042.93   409.2 2043.27   419.2 2042.23     431 2043.19
   445.5 2044.52   456.1 2047.36   495.5 2049.52   508.7 2054.08   525.5 2063.37
   543.7 2068.88   559.4 2070.36   572.8 2070.11   584.7 2071.59   661.1 2086.11
   680.2  2093.7   723.7 2115.23   760.6 2130.87   799.2 2150.42   833.1 2169.27
#Mann= 6 ,-1 , 0
       0      .1       0   409.2    .045       0     431      .1       0
  459.99     .12       0  539.99     .04       0  647.75      .1       0
#XS Ineff= 2 , 0
          362.46 2055.66
Permanent Ineff=
       F       F
Bank Sta=409.2,431
XS Rating Curve= 0 ,0
Exp/Cntr(USF)=0,0
Exp/Cntr=0.3,0.1

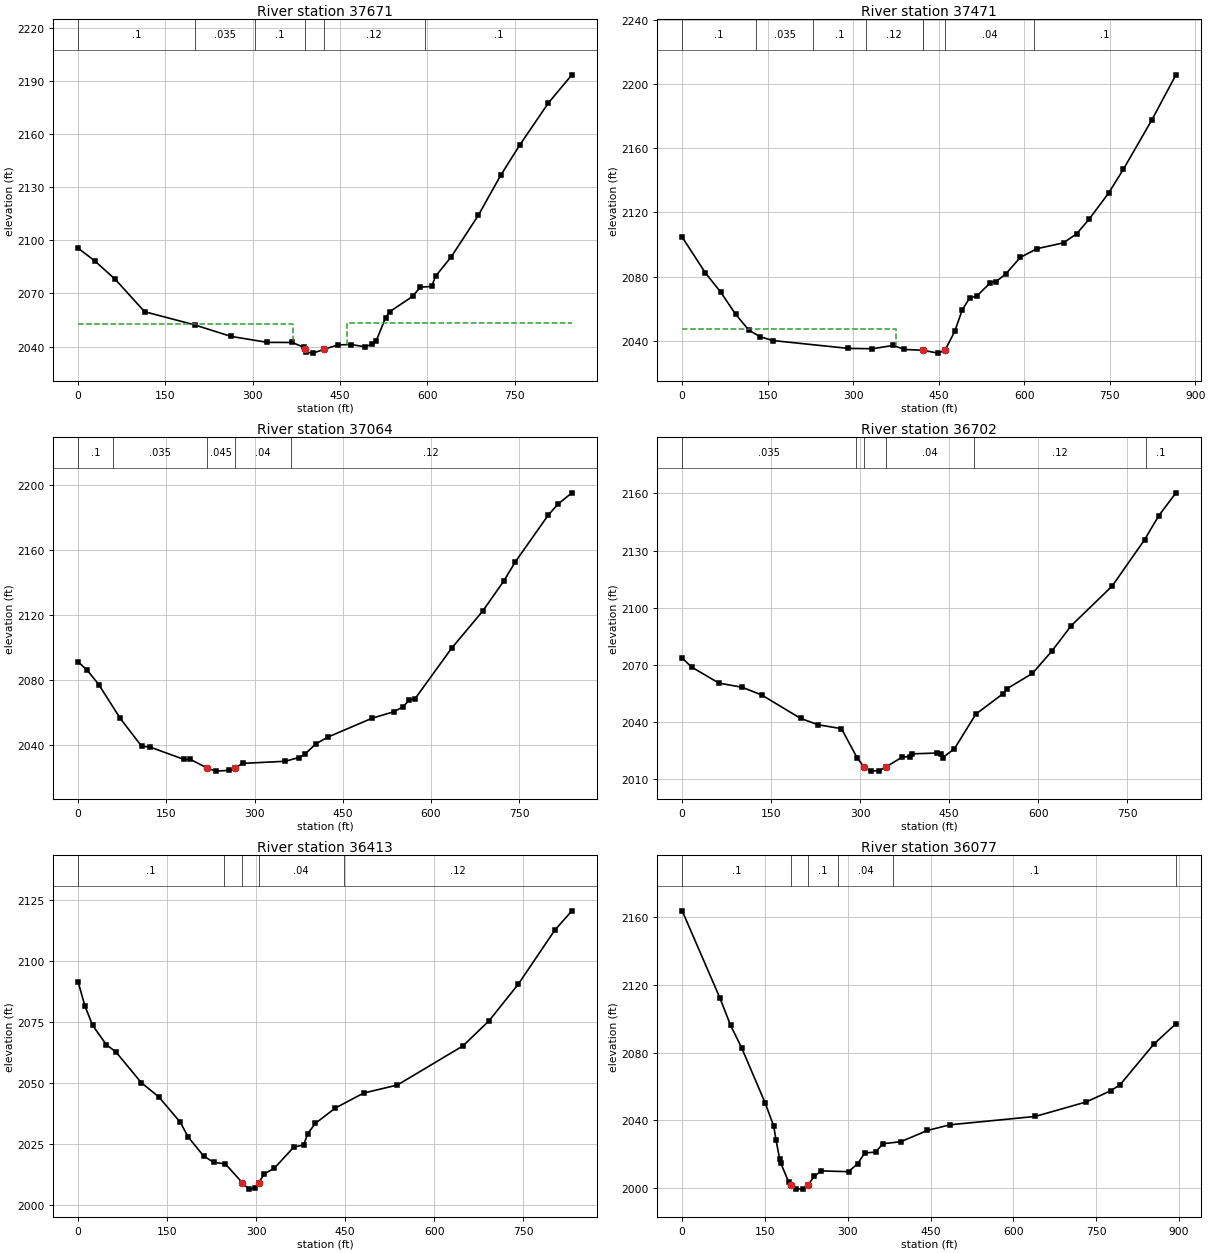
Type RM Length L Ch R = 1 ,37671   ,197.7,199.3,199.7
XS GIS Cut Line= 4
1961296.21152247228610.614388262 1961327.7600261228328.649637136
1961321.84468167228026.9670712461961337.61893348227764.720134884
#Sta/Elev= 30
       0 2095.53    28.3 2088.44    64.1 2077.85   114.2 2059.66     200 2052.24
   262.7 2045.72   325.2 2042.35   367.9  2042.3   387.5 2039.59  389.012038.383
   390.8 2036.89   403.9 2036.28  421.97 2038.38   446.6 2040.95   469.6 2041.12
   492.5 2039.85   505.7 2041.38   512.2 2043.34   528.1 2056.22   535.2 2059.64
   574.6 2068.33   587.7 2073.48   607.4 2073.97     614 2079.68   640.9 2090.61
   687.4 2113.99   725.8  2136.6   758.6 2153.73   807.9 2177.53   848.2 2193.39
#Mann= 6 ,-1 , 0
       0      .1       0     200    .035       0  303.72      .1       0
  389.01    .045       0  421.97     .12       0  595.46      .1       0
#XS Ineff= 2 , 0
          369.63 2052.76  461.32         2053.16
Permanent Ineff=
       F       F
Bank Sta=389.01,421.97
XS Rating Curve= 0 ,0
Exp/Cntr(USF)=0,0
Exp/Cntr=0.3,0.1

Type RM Length L Ch R = 1 ,37471   ,397.6,407.2,396.2
XS GIS Cut Line= 4
1961491.41788864228636.2475474561961515.07926636228405.549114716
1961524.93817374228070.3462637271961497.33323307227772.607260789
#Sta/Elev= 30
       0 2104.62    40.9 2082.21    67.3 2070.44    93.6 2056.58   116.7 2046.68
   136.5  2042.5   159.6 2040.07   291.2  2035.2   333.9 2034.99   370.2 2037.04
   389.7 2034.54   422.5 2034.01   448.8 2032.24   461.1    2034   478.3 2045.88
   491.3 2059.21   504.1 2066.51   516.9 2067.87   540.7 2076.15   550.5 2076.93
   567.3 2081.46   593.2 2091.94   622.4 2097.41   669.1 2101.06   692.2 2106.76
   713.9 2115.78   748.2 2132.12   774.2 2147.04   823.9 2177.69   866.3 2205.89
#Mann= 8 ,-1 , 0
       0      .1       0     130    .035       0     230      .1       0
  321.91     .12       0  421.91     .04       0   422.5    .045       0
   461.1     .04       0  617.26      .1       0
#XS Ineff= 2 , 0
          375.36 2047.19
Permanent Ineff=
       F       F
Bank Sta=422.5,461.1
XS Rating Curve= 0 ,0
Exp/Cntr(USF)=0,0
Exp/Cntr=0.3,0.1

Type RM Length L Ch R = 1 ,37064   ,365.3,362.3,358.1
XS GIS Cut Line= 4
1961781.26976567228669.7678325541961808.87470634228480.476810819
 1961820.7053952228281.3268817021961791.12867305227833.732486558
#Sta/Elev= 30
       0 2091.24    15.3 2086.16    35.2 2077.26    71.6 2056.56   108.1 2039.39
   121.4 2039.06   180.3 2031.34     191 2031.36  219.822026.006   233.8 2024.19
   256.7 2024.67  266.382026.007   279.7 2028.94   352.1 2030.23   375.1  2032.5
   384.9 2034.39   404.6 2041.03   424.4 2045.03     500 2056.69   536.2 2060.55
   552.6 2063.67   562.5 2067.67     573  2068.7   634.8 2099.51   687.8 2122.36
   723.6 2140.78   743.3 2152.57   799.2 2181.22   815.6 2187.91   839.4  2194.9
#Mann= 5 ,-1 , 0
       0      .1       0      60    .035       0  219.82    .045       0
  266.38     .04       0  361.29     .12       0
Bank Sta=219.82,266.38
XS Rating Curve= 0 ,0
Exp/Cntr(USF)=0,0
Exp/Cntr=0.3,0.1

Type RM Length L Ch R = 1 ,36702   ,285.2,289.1,294.1
XS GIS Cut Line= 4
1962161.82359062228703.2881176531962165.76715357228470.617903437
1962161.82359062228232.0323447921962163.79537209 227871.19633461
#Sta/Elev= 30
       0 2073.62    15.8 2068.92    61.8 2060.48   101.2 2058.28     134 2054.25
   199.6 2041.97   229.1 2038.63   268.5 2036.57   294.7 2021.37  306.742016.343
   317.7  2014.3   332.4 2014.59  342.732016.341   370.2 2021.54   383.3 2021.96
   386.6 2023.35   429.4  2023.8   435.8 2023.41   439.1 2021.38   458.8 2026.02
   494.9  2044.2   540.7 2054.89   547.4 2057.55   590.2 2065.53   622.9 2077.21
   655.7 2090.61   724.6 2111.35   779.2 2135.63   803.3 2148.31   832.2 2160.29
#Mann= 6 ,-1 , 0
       0    .035       0   292.7     .04       0  306.74    .045       0
  342.73     .04       0  491.32     .12       0  781.32      .1       0
Bank Sta=306.74,342.73
XS Rating Curve= 0 ,0
Exp/Cntr(USF)=0,0
Exp/Cntr=0.3,0.1

Type RM Length L Ch R = 1 ,36413   ,339.9,335.4,331.7
XS GIS Cut Line= 4
 1962422.0987455 228754.554436041962428.01408993228569.206977258
1962457.59081208228318.790729754 1962447.7319047227924.434434473
#Sta/Elev= 30
       0 2091.57    11.3  2081.8    24.5 2073.71    47.4 2065.88    63.9 2062.78
   106.5 2050.24   136.1 2044.38   172.2 2034.01   185.4 2027.99   211.4 2020.22
   228.3 2017.55   248.1 2016.97  276.672009.231   287.7  2006.6   297.7 2006.92
  304.142009.231   314.1  2012.9   330.7 2015.17   363.7 2023.89   380.2 2024.68
   386.8 2029.29     400 2033.59   433.6 2039.86   481.2 2045.97   538.1 2049.28
   648.5  2065.3   692.4 2075.57   741.6 2090.54   803.3 2112.74   832.1 2120.68
#Mann= 5 ,-1 , 0
       0      .1       0  245.44     .04       0  276.67    .045       0
  304.14     .04       0   447.6     .12       0
Bank Sta=276.67,304.14
XS Rating Curve= 0 ,0
Exp/Cntr(USF)=0,0
Exp/Cntr=0.3,0.1

Type RM Length L Ch R = 1 ,36077   ,157.8,147.4,137.3
XS GIS Cut Line= 4
1962769.13228535228788.0747211391962755.32981502228626.388640074
1962749.41447059228393.7184258571962607.44620428227914.575527091
#Sta/Elev= 30
       0 2163.92    68.1  2112.5    87.8 2096.07   107.6  2082.9   150.4  2050.1
   165.9 2036.41   170.1 2028.07   176.7 2016.82   178.7 2014.52   193.1 2003.11
  196.772001.332   206.2 1999.08   219.3 1999.32  227.762001.331     239 2006.62
   252.2 2009.87   301.4 2009.41   317.8 2014.08   330.9 2020.51   350.6 2021.02
   363.7 2025.97   396.1 2027.17   444.5 2033.84   485.2 2037.18   639.6 2042.12
     732  2050.7   776.2 2057.28   793.6 2060.92   854.7 2084.96   894.8 2097.04
#Mann= 6 ,-1 , 0
       0      .1       0  196.77    .045       0  227.76      .1       0
  282.27     .04       0  382.27      .1       0  894.75     .12       0
Bank Sta=196.77,227.76
XS Rating Curve= 0 ,0
Exp/Cntr(USF)=0,0
Exp/Cntr=0.3,0.1

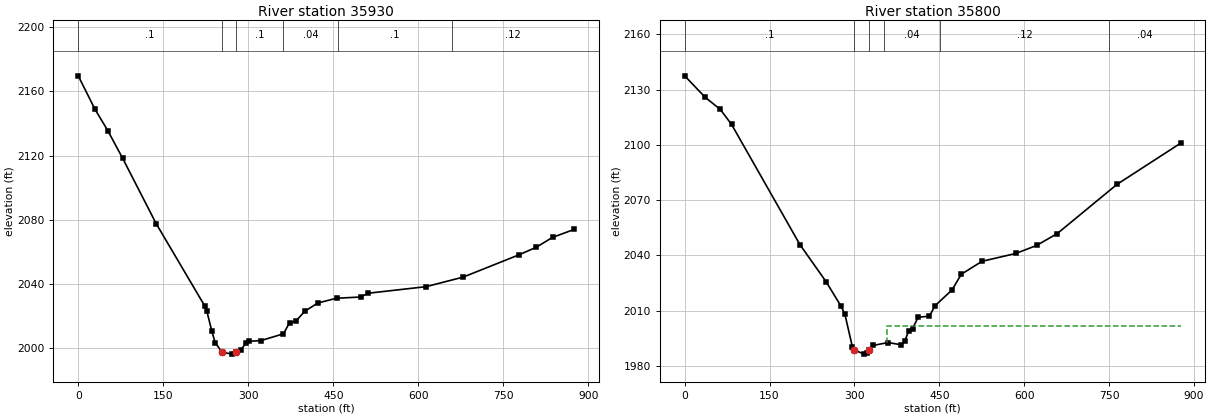
Type RM Length L Ch R = 1 ,35930   ,124.2,130.3,136.5
XS GIS Cut Line= 4
1962901.32520936228755.9817990441962899.84630419228554.850696863
1962825.90104604228393.6500340851962796.32294278227898.216804447
#Sta/Elev= 30
       0 2169.74    29.7 2148.81    52.1 2135.62    78.4 2118.29   137.4 2077.65
   223.1 2026.28   226.8 2023.12   235.7 2010.49   241.6 2003.34   253.8 1997.36
   271.8 1996.19     279 1997.38   286.3 1998.55   296.1 2003.22   300.7 2004.17
   322.4 2004.65   362.1 2008.87   372.8 2015.84   383.3 2016.57   399.7 2022.93
   422.7 2028.08   455.6 2031.04   498.3 2031.81   511.4 2034.17   613.4 2038.25
   679.1 2044.23   777.7 2058.15   807.2  2062.7   836.8    2069   874.8 2073.97
#Mann= 6 ,-1 , 0
       0      .1       0   253.8    .045       0     279      .1       0
  361.14     .04       0  458.49      .1       0  658.49     .12       0
Bank Sta=253.8,279
XS Rating Curve= 0 ,0
Exp/Cntr(USF)=0,0
Exp/Cntr=0.3,0.1

Type RM Length L Ch R = 1 ,35800   ,318.4,307.8,298.8
XS GIS Cut Line= 4
1963021.52031433228762.4415619461963001.80249957228531.743129206
1962952.50796266228206.3991855991962901.24164427227894.857712326
#Sta/Elev= 30
       0 2137.48      36 2125.87    62.9 2119.26    82.8  2111.1   203.7 2045.78
     250 2025.63   276.5 2012.26   283.1 2008.02   296.4 1990.14  299.441988.768
   316.3 1986.35   322.9 1986.91   326.31988.766   332.9 1991.06   359.4 1992.65
   382.7 1991.41   389.3 1993.65   395.9 1999.14   402.6 2000.13   412.5 2006.39
   432.4 2006.94   442.4 2012.65   472.2 2021.13   488.8 2029.73   525.3 2036.75
   585.1 2041.02   621.7 2045.34   658.3 2051.81   763.9 2078.54   876.3  2100.9
#Mann= 6 ,-1 , 0
       0      .1       0  299.44    .045       0   326.3      .1       0
  351.54     .04       0  451.54     .12       0   750.6     .04       0
#XS Ineff= 2 , 0
                          358.17          2001.4
Permanent Ineff=
       F       F
Bank Sta=299.44,326.3
XS Rating Curve= 0 ,0
Exp/Cntr(USF)=0,0
Exp/Cntr=0.5,0.3