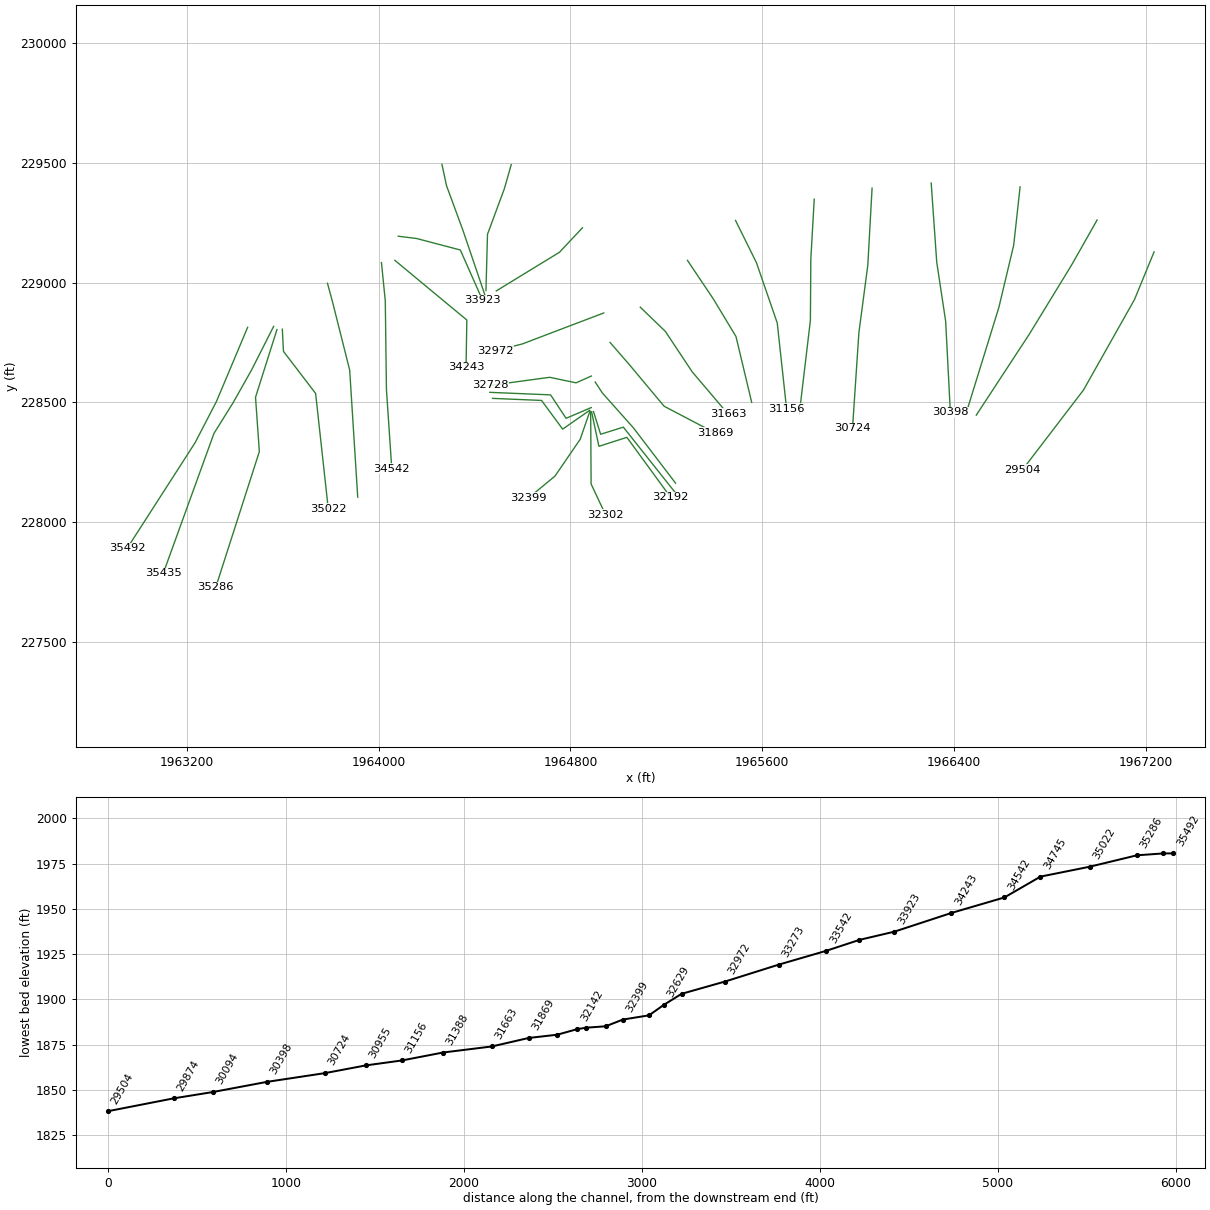
HEC-RAS study LTBLUESTRV.prj: LTBLUESTRV

--- LTBLUESTRV.g01 (geometry) --- (continued)

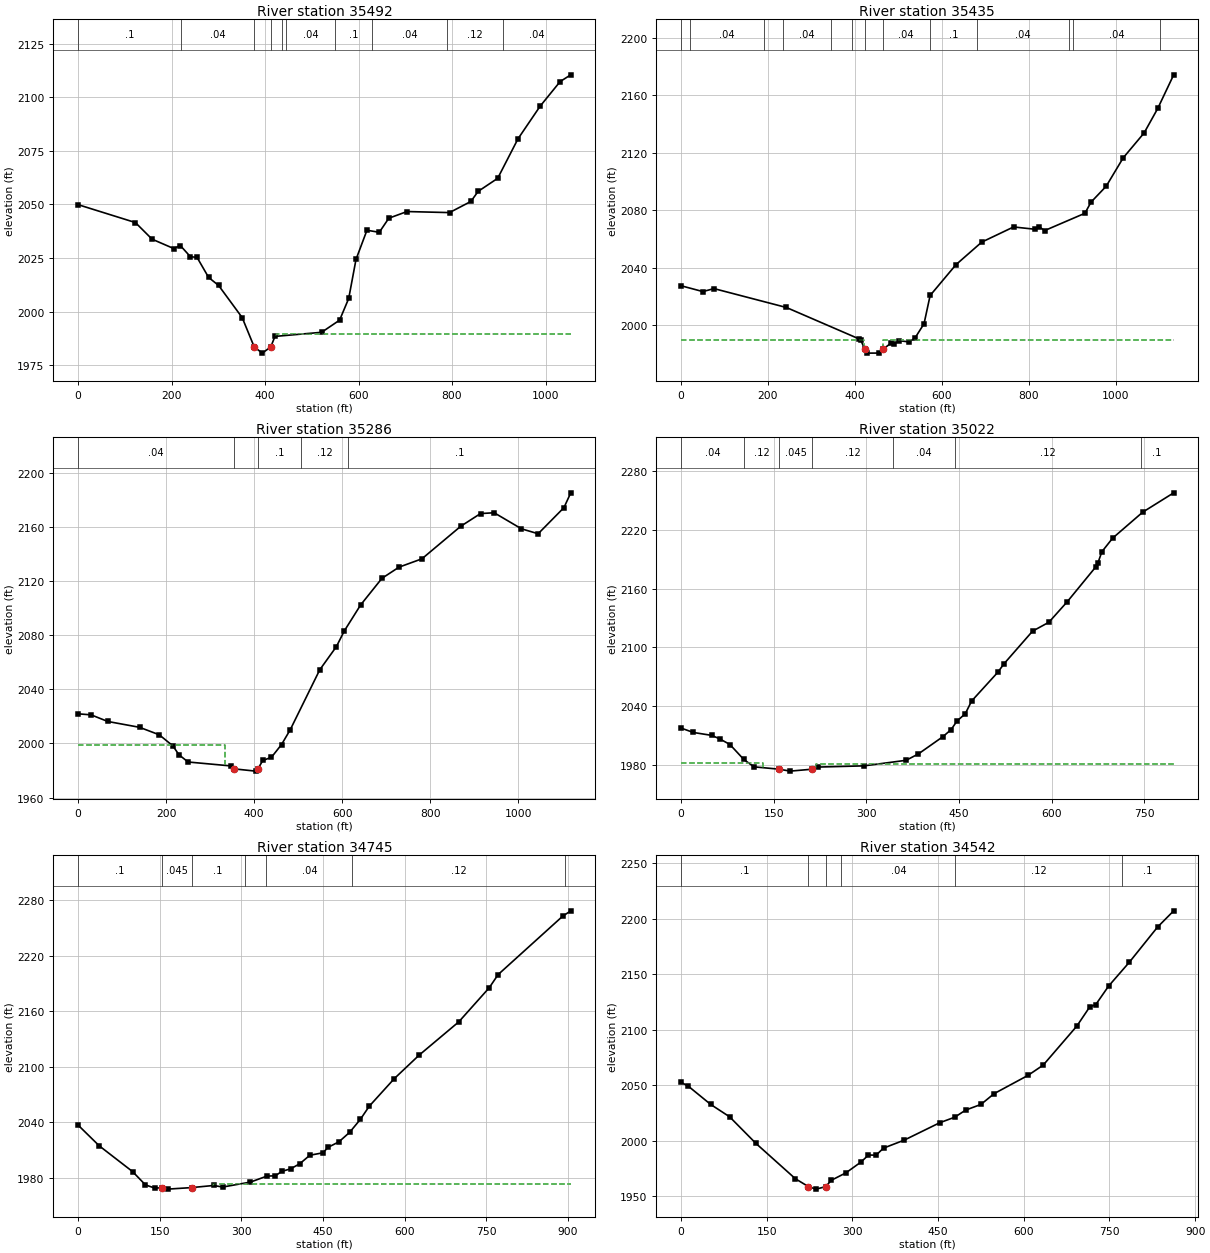
Type RM Length L Ch R = 1 ,35492   ,60.9,57.2,55.1
XS GIS Cut Line= 4
1963453.34045766228813.7078803321963323.20288022228504.138188536
1963234.47271378228332.5932000891962950.53618118227890.914149374
#Sta/Elev= 30
       0 2049.89   122.7 2041.53   158.3 2033.78   204.6 2029.41   218.8  2030.8
   240.5 2025.55   254.4 2025.33   279.3 2015.92   300.7 2012.17   351.1 1997.18
  376.821983.495   394.1 1980.59  412.261983.492   421.2 1988.39     521 1990.31
   559.5 1995.98     579 2006.12   594.6 2024.32     618 2037.94   644.4 2036.99
   664.8 2043.56   703.7 2046.67   794.6 2046.18   840.3 2051.38   855.9 2056.09
   897.7 2062.19   941.1 2080.61   988.6 2095.88  1031.3 2107.34    1054 2110.48
#Mann= 10 ,-1 , 0
       0      .1       0     220     .04       0  376.82    .045       0
  412.26     .04       0  435.81      .1       0  445.81     .04       0
  548.95      .1       0  628.95     .04       0  788.95     .12       0
  908.95     .04       0
#XS Ineff= 2 , 0
             364 1989.48     424         1989.48
Permanent Ineff=
       F       F
Bank Sta=376.82,412.26
XS Rating Curve= 0 ,0
Exp/Cntr(USF)=0,0
Exp/Cntr=0.5,0.3

Type RM Length L Ch R = 1 ,35435   ,125.9,148.2,163.2
XS GIS Cut Line= 5
1963561.78843887228817.6514432851963469.54918324228635.230301054
1963391.27213493 228496.595046811963312.99508661228371.163150114
1963101.27329116227786.907958501
#Sta/Elev= 30
       0 2027.48    50.3 2023.42      76 2025.48   242.4 2012.34   409.4 1990.49
   413.2 1989.67  422.951983.184   428.7 1980.58   455.8 1980.62  463.831983.184
   482.8 1987.46   490.6 1987.03   502.2 1989.22     524 1988.41     538 1991.05
   558.9 2001.05   572.9  2020.7   632.2  2042.1   691.5 2057.82   764.8 2068.39
   813.7 2066.79   824.1 2068.41   836.1 2065.85   928.8 2077.91   942.8 2085.64
   977.7 2096.72  1016.9 2116.51  1064.9 2133.81  1096.3 2150.88  1132.9 2174.25
#Mann= 13 ,-1 , 0
       0      .1       0      20     .04       0     190      .1       0
  234.42     .04       0  344.42     .12       0  393.62     .04       0
  422.95    .045       0  463.83     .04       0  571.48      .1       0
  681.48     .04       0  891.48      .1       0  901.48     .04       0
 1101.48      .1       0
#XS Ineff= 2 , 0
             4201989.482     465         1989.48
Permanent Ineff=
       F       F
Bank Sta=422.95,463.83
XS Rating Curve= 0 ,0
Exp/Cntr(USF)=0,0
Exp/Cntr=0.5,0.3

Type RM Length L Ch R = 1 ,35286   ,253.8,264.9,292.7
XS GIS Cut Line= 4
1963575.62476094228804.2880468831963486.18475317228521.593736611
1963502.15618313228294.799431194 1963320.0818816227727.813667653
#Sta/Elev= 30
       0 2021.96    29.6  2021.2    67.5  2016.3   139.8 2011.97   184.5 2006.44
   215.3 1998.26   229.2 1991.69   249.9  1986.3   347.3 1983.39  354.631981.212
   403.2 1979.54  408.631981.214   419.7 1987.41   439.4 1989.81   462.3 1999.22
   482.2 2010.26   549.1 2054.54     587 2071.74   604.8 2083.26   642.1  2102.6
   690.4 2122.25   729.1 2130.51   781.3  2136.7   869.5 2160.81   914.4 2170.19
   945.4 2170.79  1007.4  2158.9  1045.3 2155.25  1103.9 2174.58  1119.4 2185.54
#Mann= 5 ,-1 , 0
       0     .04       0  354.63    .045       0  408.63      .1       0
  506.51     .12       0  613.86      .1       0
#XS Ineff= 2 , 0
          333.52 1998.79
Permanent Ineff=
       F       F
Bank Sta=354.63,408.63
XS Rating Curve= 0 ,0
Exp/Cntr(USF)=0,0
Exp/Cntr=0.3,0.1

Type RM Length L Ch R = 1 ,35022   ,276.1,276.9,247.4
XS GIS Cut Line= 4
1963597.98476288228805.8851898791963602.77619187228713.250896118
1963736.93620353 228537.565166571963789.64192239228056.825124807
#Sta/Elev= 30
       0 2017.32      20 2012.79    49.6 2009.83    62.7 2006.27    79.2 2000.48
   101.7 1985.17   118.1 1977.65  158.991975.223   176.6 1973.25  212.311975.222
   221.1 1977.41     296 1978.63   364.4 1984.33   384.2 1990.83   423.8 2008.44
     437  2015.6   446.9 2024.57   460.1 2031.94   470.4 2044.95   512.9 2074.44
   522.8 2083.04     569 2116.41   595.4 2125.49   625.1 2146.46   671.3 2182.11
   674.9  2186.4   681.2 2197.65   698.6 2211.53   747.2 2238.07   797.4 2257.88
#Mann= 7 ,-1 , 0
       0     .04       0  102.76     .12       0  158.99    .045       0
  212.31     .12       0  343.81     .04       0  443.81     .12       0
  743.81      .1       0
#XS Ineff= 2 , 0
          132.72 1981.29  219.27         1980.84
Permanent Ineff=
       F       F
Bank Sta=158.99,212.31
XS Rating Curve= 0 ,0
Exp/Cntr(USF)=0,0
Exp/Cntr=0.3,0.1

Type RM Length L Ch R = 1 ,34745   ,206.4,202.6,191.5
XS GIS Cut Line= 4
 1963786.4476364228997.5423493861963808.80763834  228914.4909136
1963879.08193016228634.9908893191963912.62193308228104.739414683
#Sta/Elev= 30
       0 2036.98    39.1 2014.47   100.2 1986.72   123.9 1972.33   140.8 1968.96
   154.4 1969.18   164.5 1967.78   208.6 1969.43   249.1 1971.72     266 1970.05
   316.7 1975.36   347.2 1981.87   362.7 1982.16   374.2 1986.92   390.7  1989.7
   407.5 1995.21     426 2004.37   449.9 2007.01   459.7 2013.01   479.4 2018.86
   499.2 2029.18   518.8 2043.13   535.3 2057.44   581.3 2087.21     627 2112.61
   699.7 2148.47   755.6 2185.26     772 2199.53   890.4 2262.47   905.5 2268.39
#Mann= 7 ,-1 , 0
       0      .1       0   154.4    .045       0   208.6      .1       0
  306.01     .12       0  346.01     .04       0  504.21     .12       0
  894.21      .1       0
#XS Ineff= 2 , 0
                          247.61         1973.23
Permanent Ineff=
       F       F
Bank Sta=154.4,208.6
XS Rating Curve= 0 ,0
Exp/Cntr(USF)=0,0
Exp/Cntr=0.3,0.1

Type RM Length L Ch R = 1 ,34542   ,275.5,298.7,318.5
XS GIS Cut Line= 4
1964011.64479882229083.7880711641964027.61622878228924.073771575
1964032.40765777228553.5365965291964054.76765971228222.927996379
#Sta/Elev= 30
       0 2052.63    12.5 2049.26    52.1 2032.63    85.1 2021.52   131.2 1997.52
   200.3 1965.64   223.2 1958.53   236.4 1956.29  253.441958.529   262.8 1964.16
   288.9 1971.03   315.1 1980.72   328.2 1987.06   341.4 1986.88   354.5 1993.27
   390.6 2000.43   452.9 2016.15   479.2 2021.15   498.4 2027.59     525 2032.66
   548.1 2042.38   607.3 2058.83     634 2068.11   692.8 2103.26   715.8 2120.85
   725.7 2122.46   748.7 2139.52   784.9 2160.97   834.2 2192.61   862.4 2207.24
#Mann= 6 ,-1 , 0
       0      .1       0   223.2    .045       0  253.44      .1       0
  280.51     .04       0  480.51     .12       0  771.08      .1       0
Bank Sta=223.2,253.44
XS Rating Curve= 0 ,0
Exp/Cntr(USF)=0,0
Exp/Cntr=0.3,0.1

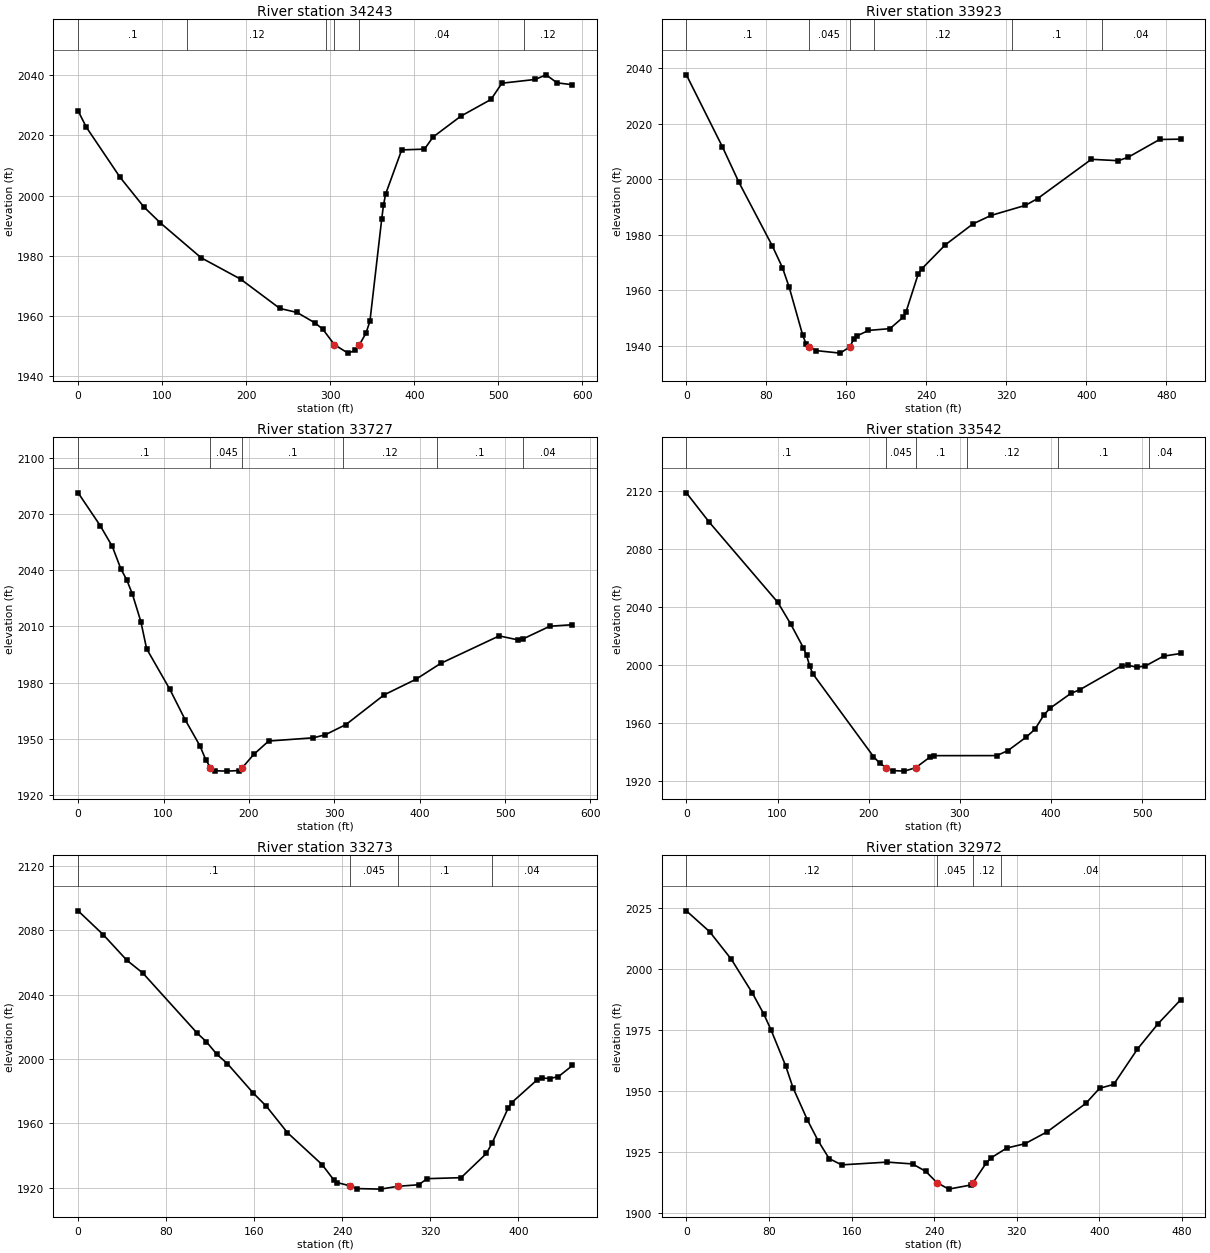
Type RM Length L Ch R = 1 ,34243   ,311.9,320.2,325.5
XS GIS Cut Line= 4
1964067.54480368229093.3709291391964209.69053031228975.182347444
 1964367.8076869228844.2166217811964364.61340091 228646.17089029
#Sta/Elev= 30
       0 2028.11     9.8 2022.69    49.9 2006.08    78.1 1996.28    97.9 1990.93
   146.3 1979.38   193.3 1972.28     240 1962.55   260.5 1961.21     282 1957.72
   291.3  1955.6  304.981950.494   321.1 1947.71   329.6 1948.59  334.711950.492
   342.4 1954.29   347.2 1958.28   361.2 1992.16   363.3 1996.79   365.9 2000.53
     385 2015.18   412.1 2015.43   422.3 2019.45   455.4 2026.38   491.2 2031.92
   504.3 2037.32   543.7 2038.56   556.8  2040.1   569.9 2037.44   588.2 2036.81
#Mann= 6 ,-1 , 0
       0      .1       0     130     .12       0  294.86     .04       0
  304.98    .045       0  334.71     .04       0  530.17     .12       0
Bank Sta=304.98,334.71
XS Rating Curve= 0 ,0
Exp/Cntr(USF)=0,0
Exp/Cntr=0.3,0.1

Type RM Length L Ch R = 1 ,33923   ,225.7,195.8,170.5
XS GIS Cut Line= 4
1964081.91909064229193.9909378811964158.58195444229184.408079905
1964340.65625597229136.4937900281964433.29054974228927.268057567
#Sta/Elev= 30
       0 2037.64      36 2011.74    52.6 1998.88    85.9 1976.05    96.1 1968.17
   102.9 1961.04   116.4 1943.79   119.8 1940.67  122.451939.632     130  1938.3
   153.8  1937.4  163.39 1939.63   167.3 1942.38   170.7 1943.62   182.1 1945.58
   203.6 1946.22     217 1950.41   219.7 1952.32   231.8 1965.86   235.2 1967.69
   258.9  1976.4   286.6 1983.95   304.5 1986.98   338.9 1990.61   351.2 1993.06
     405 2007.21     432 2006.71   441.9 2007.98   473.2 2014.35   494.3 2014.47
#Mann= 6 ,-1 , 0
       0      .1       0  122.45    .045       0  163.39      .1       0
  187.26     .12       0  325.53      .1       0  415.53     .04       0
Bank Sta=122.45,163.39
XS Rating Curve= 0 ,0
Exp/Cntr(USF)=0,0
Exp/Cntr=0.3,0.1

Type RM Length L Ch R = 1 ,33727   ,207.7,185.6,168
XS GIS Cut Line= 4
1964263.99339217229494.2538211081964283.15910812229404.813813338
1964351.83625695229217.9480828191964444.47055071228944.836630522
#Sta/Elev= 30
       0 2081.23    25.8 2063.78      40 2052.68      50 2040.73    56.8 2034.98
    63.5 2027.32    73.5 2012.54    80.2 1998.13   107.4  1976.5   125.5 1960.14
   142.7 1946.36   149.7 1938.71  154.951934.796   160.2 1933.08   174.1 1932.88
   188.1 1933.18  192.481934.795   205.6 1941.75   223.1 1948.91   275.5 1950.65
   289.5 1952.26   313.8 1957.73   358.4 1973.53   395.7 1981.85   424.6  1990.3
   493.2 2004.97   514.7 2002.88   521.6 2003.47   552.5 2010.11     579 2010.93
#Mann= 6 ,-1 , 0
       0      .1       0  154.95    .045       0  192.48      .1       0
  310.56     .12       0  420.56      .1       0  520.56     .04       0
Bank Sta=154.95,192.48
XS Rating Curve= 0 ,0
Exp/Cntr(USF)=0,0
Exp/Cntr=0.3,0.1

Type RM Length L Ch R = 1 ,33542   ,288,268.6,252.4
XS GIS Cut Line= 4
1964553.07627443229492.656678112 1964524.3277005229392.036669371
1964454.05340868 229201.97665286 1964447.6648367228967.196632464
#Sta/Elev= 30
       0 2118.77    25.3 2098.37   100.4 2043.16   114.3 2028.45   128.3 2011.93
   131.8 2006.78   135.3 1999.16   138.8 1993.88   205.2 1936.92   212.2 1932.17
  219.461929.275   226.2 1927.25   239.2 1926.88  251.571929.274   267.3 1936.65
   271.7 1937.55   340.3 1937.58   352.7 1941.05   372.5 1950.26   382.2  1955.7
     392 1965.51   398.6 1970.15   421.6 1980.45   431.4 1982.99   477.4  1999.5
   483.9 1999.95   493.8 1998.52   503.3 1999.35   523.3 2006.16   542.1    2008
#Mann= 6 ,-1 , 0
       0      .1       0  219.46    .045       0  251.57      .1       0
  307.28     .12       0  407.28      .1       0  507.28     .04       0
Bank Sta=219.46,251.57
XS Rating Curve= 0 ,0
Exp/Cntr(USF)=0,0
Exp/Cntr=0.3,0.1

Type RM Length L Ch R = 1 ,33273   ,305.5,301.4,291.4
XS GIS Cut Line= 4
1964850.14487166 229229.128083791964754.31629191229126.910932053
1964553.07627443 229003.930921371964490.78769759228965.599489468
#Sta/Elev= 30
       0 2092.02      23 2077.07    44.3 2061.29    58.7 2053.43   108.4 2015.89
   116.3 2010.87   126.1 2002.88   135.5 1997.19   159.1 1978.85   171.1 1970.61
   190.2 1954.23   221.6 1934.46   232.5 1924.71   235.5 1923.24  247.191921.215
     253 1919.55   274.8  1919.2   290.4 1920.96   309.4 1921.91   317.1  1925.7
   347.9 1926.31   370.9 1941.34     376 1947.69   390.6 1969.37     394 1972.98
   417.1 1987.12     421 1988.21   428.7 1987.89   436.4  1989.1   449.1 1995.98
#Mann= 4 ,-1 , 0
       0      .1       0  247.19    .045       0   290.4      .1       0
  375.95     .04       0
Bank Sta=247.19,290.4
XS Rating Curve= 0 ,0
Exp/Cntr(USF)=0,0
Exp/Cntr=0.3,0.1

Type RM Length L Ch R = 1 ,32972   ,254,243.6,228.7
XS GIS Cut Line= 4
1964939.25186745228873.6005475161964766.17327119228807.874498302
1964599.66727985228744.3393173961964487.93299618228715.858029403
#Sta/Elev= 30
       0  2023.8    22.5 2015.27    43.6 2003.93    63.9 1990.15    75.1 1981.46
    82.1 1974.94    96.1 1960.42   103.2 1951.47   117.3 1938.13   127.7  1929.6
   138.3 1922.38   150.4 1919.82   194.4 1920.95     219  1920.2   231.8 1917.17
   242.71912.521   254.1 1909.89   275.2 1911.56  277.611912.522   290.2 1920.46
   295.3 1922.75   310.3 1926.72   327.9 1928.47   349.5 1933.38   386.7 1944.94
   400.2 1951.18   413.8 1952.74   436.8 1967.21   456.7 1977.55   478.7  1987.4
#Mann= 4 ,-1 , 0
       0     .12       0   242.7    .045       0  277.61     .12       0
  305.14     .04       0
Bank Sta=242.7,277.61
XS Rating Curve= 0 ,0
Exp/Cntr(USF)=0,0
Exp/Cntr=0.3,0.1

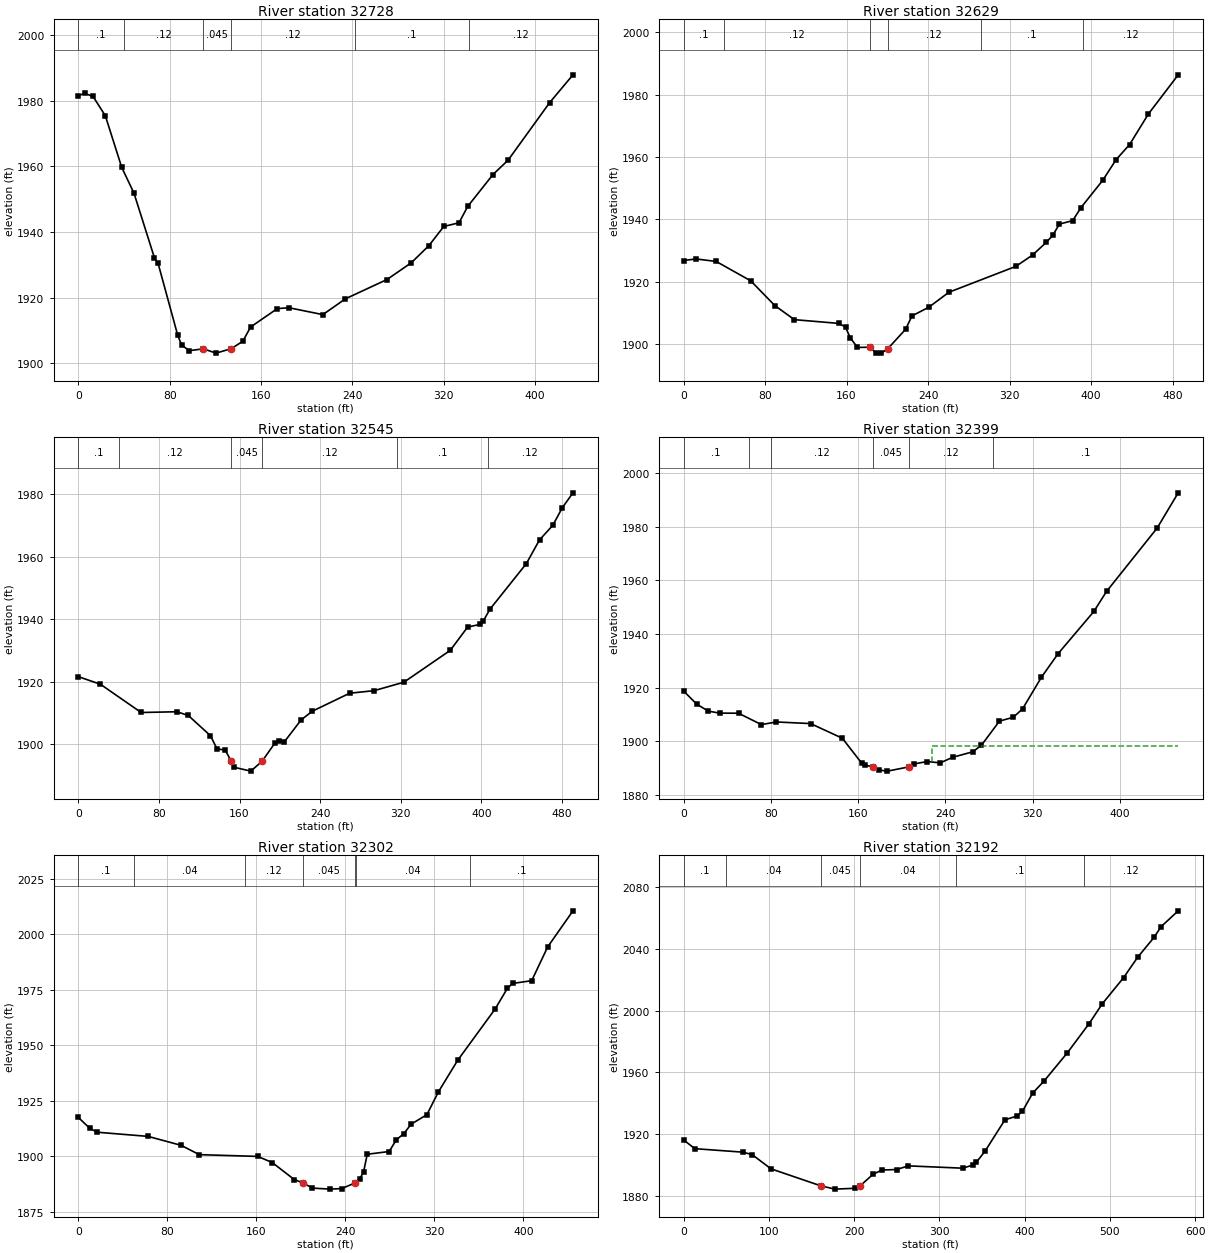
Type RM Length L Ch R = 1 ,32728   ,127.2,99.4,82.8
XS GIS Cut Line= 4
1964887.39401462228610.2800856831964823.50829478228581.886432423
 1964713.4828884228604.9562756971964465.03842237 228571.23881245
#Sta/Elev= 30
       0 1981.57     5.7 1982.25    12.9 1981.33    23.7 1975.43      38 1959.75
    48.8 1951.82    66.7 1932.13    69.8 1930.56    87.1 1908.51    90.4 1905.63
    97.1 1903.86   109.5 1904.43   120.6 1903.12     134 1904.49   144.1 1906.75
   150.8 1911.06   174.2 1916.67   184.3 1916.96   214.1 1914.85   233.9 1919.67
   270.3 1925.55   291.5 1930.64   306.8 1935.81     320 1941.71   333.3 1942.83
     341 1947.84     363 1957.51   376.3 1961.91   412.7 1979.45   433.1 1987.91
#Mann= 6 ,-1 , 0
       0      .1       0      40     .12       0   109.5    .045       0
     134     .12       0  242.33      .1       0  342.33     .12       0
Bank Sta=109.5,134
XS Rating Curve= 0 ,0
Exp/Cntr(USF)=0,0
Exp/Cntr=0.5,0.3

Type RM Length L Ch R = 1 ,32629   ,80.1,83.5,79.1
XS GIS Cut Line= 4
1964887.06529088228478.676841511 1964781.8343104 228433.73624831
  1964717.346179 228531.599875081964463.78094135 228542.22352331
#Sta/Elev= 30
       0 1926.77    12.5 1927.27    32.1 1926.46      66 1920.24    89.6 1912.31
   108.8 1907.79   152.7 1906.58     159 1905.36   163.6 1901.98   170.7 1898.87
   182.5 1898.96   188.5 1897.25   194.1 1897.05   200.4 1898.45   217.9  1904.7
   224.2    1909   240.7 1911.78   260.4 1916.58   326.1 1924.89   342.5 1928.52
   355.9 1932.59   362.2 1934.81   368.8 1938.44   381.9 1939.58     390 1943.75
   411.4 1952.52   424.4 1959.11   437.7 1963.98   456.2 1973.81   485.4 1986.35
#Mann= 6 ,-1 , 0
       0      .1       0      40     .12       0   182.5    .045       0
   200.4     .12       0  291.63      .1       0  391.63     .12       0
#XS Ineff= 2 , 0
           180.5 1898.63  202.67         1898.82
Permanent Ineff=
       F       F
Bank Sta=182.5,200.4
XS Rating Curve= 0 ,0
Exp/Cntr(USF)=0,0
Exp/Cntr=0.5,0.3

Type RM Length L Ch R = 1 ,32545   ,94.8,146.4,188.3
XS GIS Cut Line= 4
1964880.41335041228467.2653129951964767.67232163228388.595968509
1964679.50637713228508.4015464871964475.01535934228516.993912773
#Sta/Elev= 30
       0 1921.56    21.9 1919.13    62.4 1910.06    97.9  1910.3   109.2  1909.1
   131.2 1902.61   137.5  1898.5     146  1897.9   151.81894.414   154.6  1892.5
   171.2 1891.26  182.361894.411   194.9 1900.16   198.9 1901.07   204.5 1900.66
   221.1 1907.67   232.1 1910.45   269.3 1916.24   293.5 1917.06   323.1 1919.77
   369.1 1929.98   386.4 1937.47   398.6 1938.29   401.9  1939.4   408.4 1943.14
   444.6 1957.79   457.7 1965.41   470.9 1970.09   480.4 1975.77   490.9  1980.5
#Mann= 6 ,-1 , 0
       0      .1       0      40     .12       0   151.8    .045       0
  182.36     .12       0  316.23      .1       0  406.23     .12       0
#XS Ineff= 2 , 0
          149.79  1894.4  184.21         1894.45
Permanent Ineff=
       F       F
Bank Sta=151.8,182.36
XS Rating Curve= 0 ,0
Exp/Cntr(USF)=0,0
Exp/Cntr=0.5,0.3

Type RM Length L Ch R = 1 ,32399   ,85.2,97.1,123.4
XS GIS Cut Line= 4
1964881.19256802228462.7873490521964840.59590685228345.911289337
1964735.55235119 228192.47310684 1964624.8204502 228100.99345389
#Sta/Elev= 30
       0 1918.83    12.2 1913.88    22.7 1911.31    33.1 1910.56    50.4 1910.53
    71.3 1906.29    85.2 1907.26   116.4 1906.67   145.5 1901.21   163.1    1892
   166.3 1891.11   173.8 1890.62     179 1889.35   186.9 1888.94   206.6 1890.53
   211.6 1891.65   223.4 1892.52   235.2 1892.01   246.6 1894.09     265 1896.14
     273 1898.57   289.5 1907.59   302.2 1909.01   310.7 1912.16     328 1923.96
   343.3 1932.76     376 1948.45   387.6 1955.91     434 1979.55   453.3 1992.68
#Mann= 6 ,-1 , 0
       0      .1       0      60     .04       0      80     .12       0
   173.8    .045       0   206.6     .12       0  283.73      .1       0
#XS Ineff= 2 , 0
                          227.79         1898.42
Permanent Ineff=
       F       F
Bank Sta=173.8,206.6
XS Rating Curve= 0 ,0
Exp/Cntr(USF)=0,0
Exp/Cntr=0.3,0.1

Type RM Length L Ch R = 1 ,32302   ,64.9,109.2,185.1
XS GIS Cut Line= 4
1964884.52583479228461.5664758371964885.17901677228351.845360183
1964886.34333401228159.733014922 1964946.8878307228030.493800837
#Sta/Elev= 30
       0  1917.5    10.3 1912.62    16.9 1910.83    62.8 1908.95    92.4 1904.93
   108.8 1900.74   161.3 1899.94   174.3 1897.19   194.1 1889.53  201.931888.013
   210.5 1885.68   226.4 1885.22   236.7 1885.47  248.841888.011   253.1 1889.98
   256.4 1892.97   259.7 1900.91   279.4 1902.15   285.9 1907.46   292.5 1910.13
   299.1 1914.44   313.3 1918.72   323.7 1929.02     341 1943.21   374.8  1966.4
   385.7 1975.65   390.4 1977.79   407.5 1979.02   421.9 1994.26   444.6 2010.46
#Mann= 7 ,-1 , 0
       0      .1       0      50     .04       0  149.72     .12       0
  201.93    .045       0  248.84     .12       0  249.72     .04       0
  351.84      .1       0
Bank Sta=201.93,248.84
XS Rating Curve= 0 ,0
Exp/Cntr(USF)=0,0
Exp/Cntr=0.5,0.3

Type RM Length L Ch R = 1 ,32192   ,51.3,50.2,51.5
XS GIS Cut Line= 4
  1964888.325955228460.9795194581964918.94421684228316.915842863
1965035.58621694228354.2791325181965218.50033954 228103.47110992
#Sta/Elev= 30
       0 1916.33    13.3 1910.64    69.4 1908.39    80.4 1906.82   102.6 1897.59
  160.861886.599   177.6 1884.44   201.7    1885  207.211886.599   222.4 1894.11
   232.7 1896.78   249.9 1897.14   263.7  1899.5   327.7 1897.99   339.5 1900.11
   343.5 1901.86   353.6 1908.97     377 1929.33   391.1 1931.76   397.5 1934.84
   409.6 1946.69   422.9 1954.45   450.3  1972.8   475.7 1991.61   490.9 2004.27
   516.1 2021.35   532.8 2034.69   551.8 2047.42   560.2 2054.44   580.2 2064.65
#Mann= 6 ,-1 , 0
       0      .1       0      50     .04       0  160.86    .045       0
  207.21     .04       0  319.76      .1       0  469.76     .12       0
#XS Ineff= 2 , 0
          156.29 1886.62  211.41         1886.72
Permanent Ineff=
       F       F
Bank Sta=160.86,207.21
XS Rating Curve= 0 ,0
Exp/Cntr(USF)=0,0
Exp/Cntr=0.5,0.3

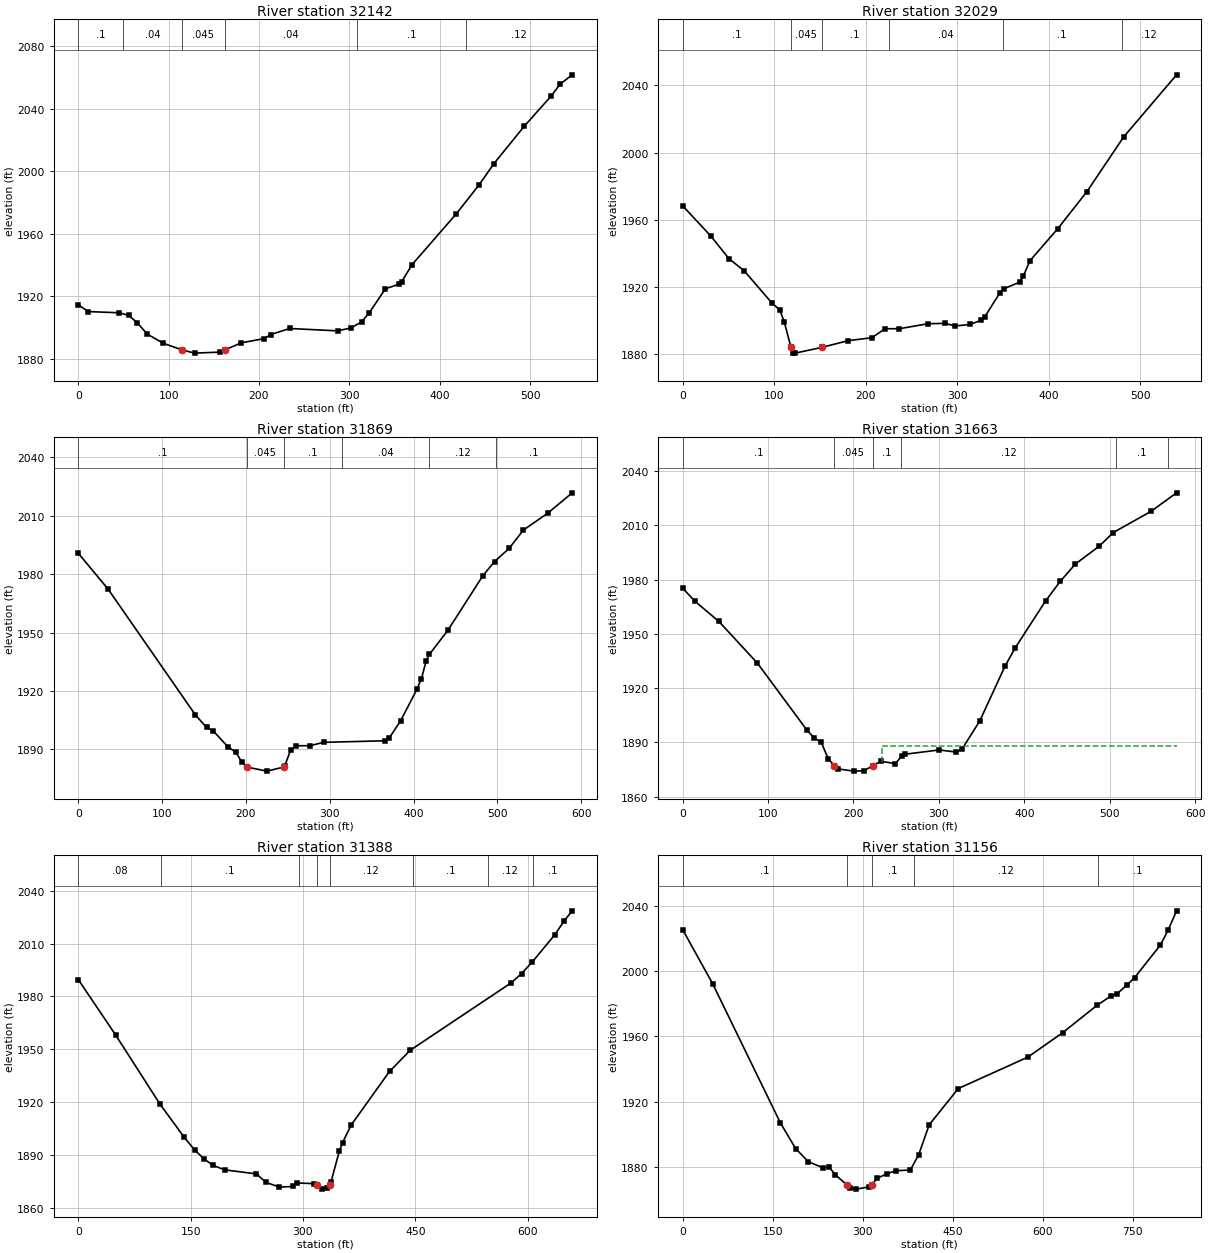
Type RM Length L Ch R = 1 ,32142   ,138.3,113,69.5
XS GIS Cut Line= 4
1964896.27877014228461.8570065791964926.07120335228367.132347149
1965020.79586278228396.9247803571965236.98198067228124.209430223
#Sta/Elev= 30
       0 1914.62    11.1 1910.24    45.5 1909.48    55.8 1907.82    65.3 1903.09
    76.5 1895.77      94 1889.99  114.691885.738   128.9 1883.65   156.5  1884.3
  162.271885.738   180.5 1890.26   206.1 1892.98     213 1895.55   234.1 1899.42
     287 1897.91   301.8 1899.78   313.5 1903.65   321.9 1909.36   339.9 1924.81
   355.4 1927.89   357.9 1929.38   369.5 1940.35   418.2 1972.71   443.3 1991.14
     460 2004.95   493.5 2028.84   523.7 2048.45     533  2055.7   546.6  2061.8
#Mann= 6 ,-1 , 0
       0      .1       0      50     .04       0  114.69    .045       0
  162.27     .04       0   308.6      .1       0   428.6     .12       0
#XS Ineff= 2 , 0
           111.5 1885.93  165.97         1886.02
Permanent Ineff=
       F       F
Bank Sta=114.69,162.27
XS Rating Curve= 0 ,0
Exp/Cntr(USF)=0,0
Exp/Cntr=0.5,0.3

Type RM Length L Ch R = 1 ,32029   ,160.7,160.4,159.6
XS GIS Cut Line= 4
1964903.36544458 228585.435639081964933.53370117228539.295952532
1965063.07974417228393.7784795731965238.76547372228163.080046834
#Sta/Elev= 30
       0 1968.34      31 1950.17    50.8 1936.72    67.2 1929.65    97.4 1910.54
   106.2 1906.26   111.1 1899.17  118.441883.985   120.6 1880.76     123 1880.56
  152.19 1883.98     181    1888   206.6 1889.71   221.4 1895.09   236.8  1895.1
   268.5 1898.09   287.1 1898.27   297.9 1896.72   313.8 1897.63   326.2 1900.09
   330.4 1902.31   346.8 1916.45   350.9 1918.88   368.3 1922.79   372.5 1926.63
   379.8 1935.69     410 1954.65   441.7 1976.58     482 2009.28   539.9 2046.32
#Mann= 6 ,-1 , 0
       0      .1       0  118.44    .045       0  152.19      .1       0
  225.13     .04       0  349.95      .1       0  479.95     .12       0
Bank Sta=118.44,152.19
XS Rating Curve= 0 ,0
Exp/Cntr(USF)=0,0
Exp/Cntr=0.3,0.1

Type RM Length L Ch R = 1 ,31869   ,210.4,206.1,202.8
XS GIS Cut Line= 4
1964965.47656109228750.4737486561965047.10831421228656.419772231
1965190.85118384228484.2832493411965403.80358329228372.483239628
#Sta/Elev= 30
       0 1990.76    35.7 1972.24   139.7 1907.69   153.1 1901.21     161 1899.46
   178.7 1891.22   188.1  1888.4     195 1883.59  201.281880.839   225.2 1878.77
  244.92 1880.84   246.5  1881.6   253.3 1889.47   259.4 1891.81   276.5 1891.84
   292.9 1893.57   365.8 1894.36   370.7 1895.56   384.6 1904.65   404.1 1920.82
   409.5 1926.36   415.2 1935.54   418.9 1938.71   441.2 1951.25   482.4 1978.96
   496.7 1986.48     514 1993.17     531  2002.6   560.2 2011.32   589.3 2021.77
#Mann= 6 ,-1 , 0
       0      .1       0  201.28    .045       0  244.92      .1       0
  314.54     .04       0   418.8     .12       0   498.8      .1       0
Bank Sta=201.28,244.92
XS Rating Curve= 0 ,0
Exp/Cntr(USF)=0,0
Exp/Cntr=0.3,0.1

Type RM Length L Ch R = 1 ,31663   ,279.2,274.6,268.5
XS GIS Cut Line= 4
1965091.47339743228897.7658249431965196.17499383228796.613435204
1965307.97500354228628.0261189711965457.04168315228452.340389423
#Sta/Elev= 30
       0 1975.23    14.6 1967.94    42.5 1956.82    87.6 1933.77   145.6 1896.71
     154 1892.49   162.4 1889.97   170.3 1881.07   177.41877.104   182.1 1875.29
   200.7 1874.09   212.6 1874.31  222.461877.104   232.1 1879.52     249 1878.26
   256.9 1882.59   260.8 1883.46   300.2 1885.79   319.9 1884.66   326.8 1886.05
   347.9 1901.84   377.5 1932.18   389.5 1942.33   424.9 1968.17     442 1978.94
   459.8 1988.59   487.8 1998.46   504.1 2005.97   548.3 2017.68   578.3 2027.96
#Mann= 6 ,-1 , 0
       0      .1       0   177.4    .045       0  222.46      .1       0
  255.58     .12       0  507.87      .1       0  567.87     .12       0
#XS Ineff= 2 , 0
                          233.81         1888.03
Permanent Ineff=
       F       F
Bank Sta=177.4,222.46
XS Rating Curve= 0 ,0
Exp/Cntr(USF)=0,0
Exp/Cntr=0.3,0.1

Type RM Length L Ch R = 1 ,31388   ,240.3,232.4,215.8
XS GIS Cut Line= 4
1965288.45436692229092.9721911081965396.70516998 228931.48328819
 1965490.7591464228775.3181952581965556.41946957228500.254679299
#Sta/Elev= 30
       0 1989.59    49.8 1958.23     109 1919.03   141.3 1900.25   155.5 1892.91
   168.3 1887.77   180.1 1884.16   195.7 1881.68     238 1879.38   250.7 1874.55
   268.6 1871.94   286.6 1872.26   291.6 1874.28   314.6 1873.84   318.4 1873.13
   326.1 1870.75     332 1871.38  335.831873.313   337.6 1875.04   348.7 1892.46
   352.9  1897.1   364.4 1907.09   415.6 1937.45   443.4 1949.53   578.4 1987.81
   591.9 1992.96   606.2 1999.53   636.2 2014.93   649.2 2023.05   659.5 2028.54
#Mann= 8 ,-1 , 0
       0     .08       0     110      .1       0  294.41     .12       0
   318.4    .045       0  335.83     .12       0  446.72      .1       0
  546.72     .12       0  606.72      .1       0
Bank Sta=318.4,335.83
XS Rating Curve= 0 ,0
Exp/Cntr(USF)=0,0
Exp/Cntr=0.3,0.1

Type RM Length L Ch R = 1 ,31156   ,207.9,200.9,187.7
XS GIS Cut Line= 4
1965488.98454307229259.7849040121965575.94010618229084.099174464
1965662.89566929228832.1055017791965701.93694252228473.635629368
#Sta/Elev= 30
       0 2025.37    50.2 1992.06   162.8 1907.04   188.3 1891.21   209.6 1883.12
   233.9 1879.43   244.3 1879.81   254.7 1875.05  273.431869.104   279.7 1866.88
   289.4 1866.35   310.7 1867.74   315.81869.109   324.1 1873.01   341.4 1875.89
   355.3  1877.6   379.6 1878.08   393.5 1887.48   410.9 1905.75   459.4 1927.96
   575.1 1947.17   633.2 1962.12   690.6 1978.94   713.7 1984.64   723.6 1985.94
   739.8 1991.11   753.3 1995.94   796.3 2015.89   809.4 2025.23   823.2 2036.83
#Mann= 5 ,-1 , 0
       0      .1       0  273.43    .045       0   315.8      .1       0
  386.03     .12       0   692.6      .1       0
Bank Sta=273.43,315.8
XS Rating Curve= 0 ,0
Exp/Cntr(USF)=0,0
Exp/Cntr=0.3,0.1

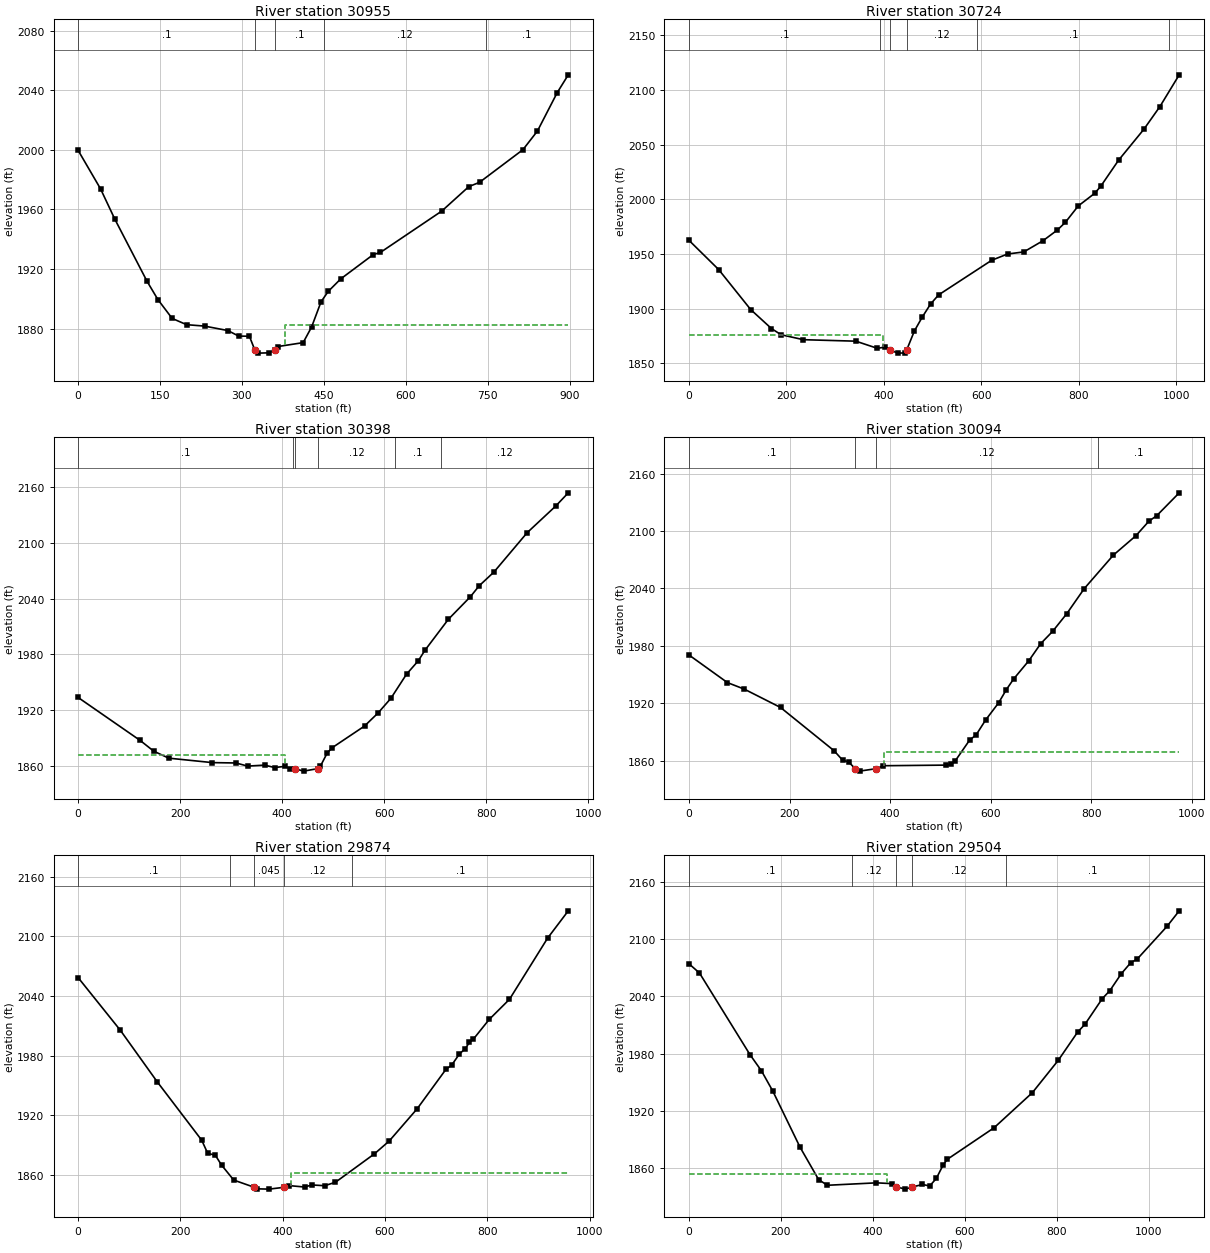
Type RM Length L Ch R = 1 ,30955   ,232.9,230.9,225.6
XS GIS Cut Line= 4
1965817.28615889 229348.515070451965803.08933226229098.296001094
1965801.31472894228842.7531217511965755.17504239228454.114992752
#Sta/Elev= 30
       0 1999.72    41.1 1973.88    67.3 1953.52   126.5 1911.69   146.2 1899.56
   172.3 1886.91   198.8 1882.73   231.6 1881.78   274.3 1878.79     294 1875.09
   313.7 1874.97   323.5 1865.88   330.1 1863.65   349.8 1863.85  359.691865.881
   366.2 1868.09   412.1 1870.69   427.5  1881.1   444.9 1898.11   458.1 1905.08
     481 1913.46   540.3 1929.69   553.5 1931.18   665.9 1958.93   715.4 1975.32
     735  1978.2   814.5  2000.1     841 2012.59   877.3 2038.39   897.5  2050.3
#Mann= 5 ,-1 , 0
       0      .1       0   323.5    .045       0  359.69      .1       0
  450.62     .12       0  746.17      .1       0
#XS Ineff= 2 , 0
                          378.22         1882.35
Permanent Ineff=
       F       F
Bank Sta=323.5,359.69
XS Rating Curve= 0 ,0
Exp/Cntr(USF)=0,0
Exp/Cntr=0.3,0.1

Type RM Length L Ch R = 1 ,30724   ,317.5,325.6,334.3
XS GIS Cut Line= 4
1966058.63221161229394.6547569981966040.88617832229073.451554491
1966003.61950841228791.2896252171965977.00045848228392.003876245
#Sta/Elev= 30
       0  1962.5      61 1935.76   126.7  1899.2   169.4 1881.81   189.1 1876.19
   235.1 1871.65   342.6  1870.3   386.7 1863.77   403.3 1864.95  413.451861.877
   429.8 1859.37     443 1859.55  446.631861.874   462.8 1879.66     479 1892.38
   495.9  1904.2   512.5 1912.62   621.6 1944.31     654    1950   687.4 1951.92
   726.8 1962.16   756.4 1971.96   772.8 1979.01   799.2 1993.96   832.8 2005.45
   845.2 2011.84   882.1 2035.84     934 2064.11   966.8 2084.79  1006.5 2113.86
#Mann= 6 ,-1 , 0
       0      .1       0  391.69     .12       0  413.45    .045       0
  446.63     .12       0  591.69      .1       0  986.31     .12       0
#XS Ineff= 2 , 0
          398.85 1875.66
Permanent Ineff=
       F       F
Bank Sta=413.45,446.63
XS Rating Curve= 0 ,0
Exp/Cntr(USF)=0,0
Exp/Cntr=0.3,0.1

Type RM Length L Ch R = 1 ,30398   ,307.5,303.9,284.9
XS GIS Cut Line= 4
 1966305.3020743229415.9499969431966328.37191758229085.873777792
1966365.63858748228839.203915094 1966385.1592241228459.438802738
#Sta/Elev= 30
       0 1933.78   121.8 1887.49   148.2 1876.03   177.8 1868.48   263.3  1863.7
   309.3 1863.31   332.3 1859.96   365.5    1861   385.4  1858.4   405.3 1859.69
   415.3 1857.29     425 1857.16   441.8 1854.55  470.961857.334     475    1860
   488.3  1874.1   498.2 1879.81   561.3 1902.99   587.8    1917     613  1932.8
   643.6 1958.72   666.6 1973.08   679.7 1984.42   725.7  2017.8   768.8 2042.01
   786.1 2053.82     815 2068.59   880.1 2110.89     936 2139.49   960.6  2153.7
#Mann= 6 ,-1 , 0
       0      .1       0  420.88     .12       0     425    .045       0
  470.96     .12       0  620.35      .1       0  710.35     .12       0
#XS Ineff= 2 , 0
          405.44 1872.26
Permanent Ineff=
       F       F
Bank Sta=425,470.96
XS Rating Curve= 0 ,0
Exp/Cntr(USF)=0,0
Exp/Cntr=0.3,0.1

Type RM Length L Ch R = 1 ,30094   ,227.2,220,208.4
XS GIS Cut Line= 4
1966676.19417002229399.9785669841966649.57512009229156.857910943
1966587.46400358228895.9912216141966450.81954726228454.114992752
#Sta/Elev= 30
       0 1970.34    76.5 1941.47   110.1 1934.63   182.1  1915.5   288.7 1870.24
   305.5 1860.46   317.5 1858.54  330.721851.547   339.3 1848.94  372.871851.548
   386.5 1854.58   511.3 1855.23   521.5 1855.94   529.4 1859.44   558.2 1881.28
   571.3 1886.87   590.2 1902.42   615.9 1920.24   631.4 1934.13   645.9 1945.28
   676.1 1964.35   699.8 1982.23   723.5 1995.05   751.6 2013.52   786.4 2039.74
   844.3 2074.73     889 2094.93   914.9 2110.13   930.7 2116.02   975.3 2139.84
#Mann= 4 ,-1 , 0
       0      .1       0  330.72    .045       0  372.87     .12       0
  812.73      .1       0
#XS Ineff= 2 , 0
                          388.25         1869.08
Permanent Ineff=
       F       F
Bank Sta=330.72,372.87
XS Rating Curve= 0 ,0
Exp/Cntr(USF)=0,0
Exp/Cntr=0.3,0.1

Type RM Length L Ch R = 1 ,29874   ,371.6,370.4,362.9
XS GIS Cut Line= 4
1966997.39737252 229261.55950734 1966890.9211728229073.451554491
1966715.23544325228785.9658152311966493.41002715228447.016579436
#Sta/Elev= 30
       0 2058.51    82.9 2005.24   154.5 1953.69   241.7 1894.71   253.3 1881.64
   268.5 1879.45   280.4 1869.73   304.3 1854.58  344.59 1847.28   349.6 1845.76
   373.5 1845.46  402.341847.279   411.7 1849.04   442.7 1847.58   457.1 1849.66
   482.1 1848.89   503.2 1852.41   579.3 1880.99   608.1 1893.84     663 1926.47
   719.1 1966.09   730.2 1970.24   745.3 1981.45   757.1 1987.05   764.9 1993.23
   772.8 1996.54   803.7 2016.34   843.3  2036.6   917.8 2098.18   958.2 2125.67
#Mann= 5 ,-1 , 0
       0      .1       0  296.15     .04       0  344.59    .045       0
  402.34     .12       0  536.15      .1       0
#XS Ineff= 2 , 0
                          415.47          1861.4
Permanent Ineff=
       F       F
Bank Sta=344.59,402.34
XS Rating Curve= 0 ,0
Exp/Cntr(USF)=0,0
Exp/Cntr=0.3,0.1

Type RM Length L Ch R = 1 ,29504   ,452.8,469.7,494
XS GIS Cut Line= 4
1967235.19421858229128.4642576831967153.56246546228929.708684861
  1966940.610066228551.7181758341966686.84178999228219.867353354
#Sta/Elev= 30
       0 2074.11    22.8 2064.47   132.7 1979.05   157.6 1962.14   182.4 1940.85
   241.7 1882.13     282 1848.36   300.9 1842.38   407.9 1844.93   441.7  1844.1
  449.36 1840.94   470.6 1838.35   485.4 1840.51     508 1843.23   523.6 1841.65
     538 1849.47   553.2 1863.88   562.1 1869.58   663.7 1902.55   747.1 1939.31
   803.3 1973.08   845.4 2002.57   861.6 2010.91   899.2  2037.7   915.6    2046
   940.4 2063.66   961.1 2075.28     975 2078.99  1039.7 2113.13  1066.5 2129.52
#Mann= 5 ,-1 , 0
       0      .1       0  354.87     .12       0  449.36    .045       0
   485.4     .12       0  688.72      .1       0
#XS Ineff= 2 , 0
           429.8 1853.73
Permanent Ineff=
       F       F
Bank Sta=449.36,485.4
XS Rating Curve= 0 ,0
Exp/Cntr(USF)=0,0
Exp/Cntr=0.3,0.1