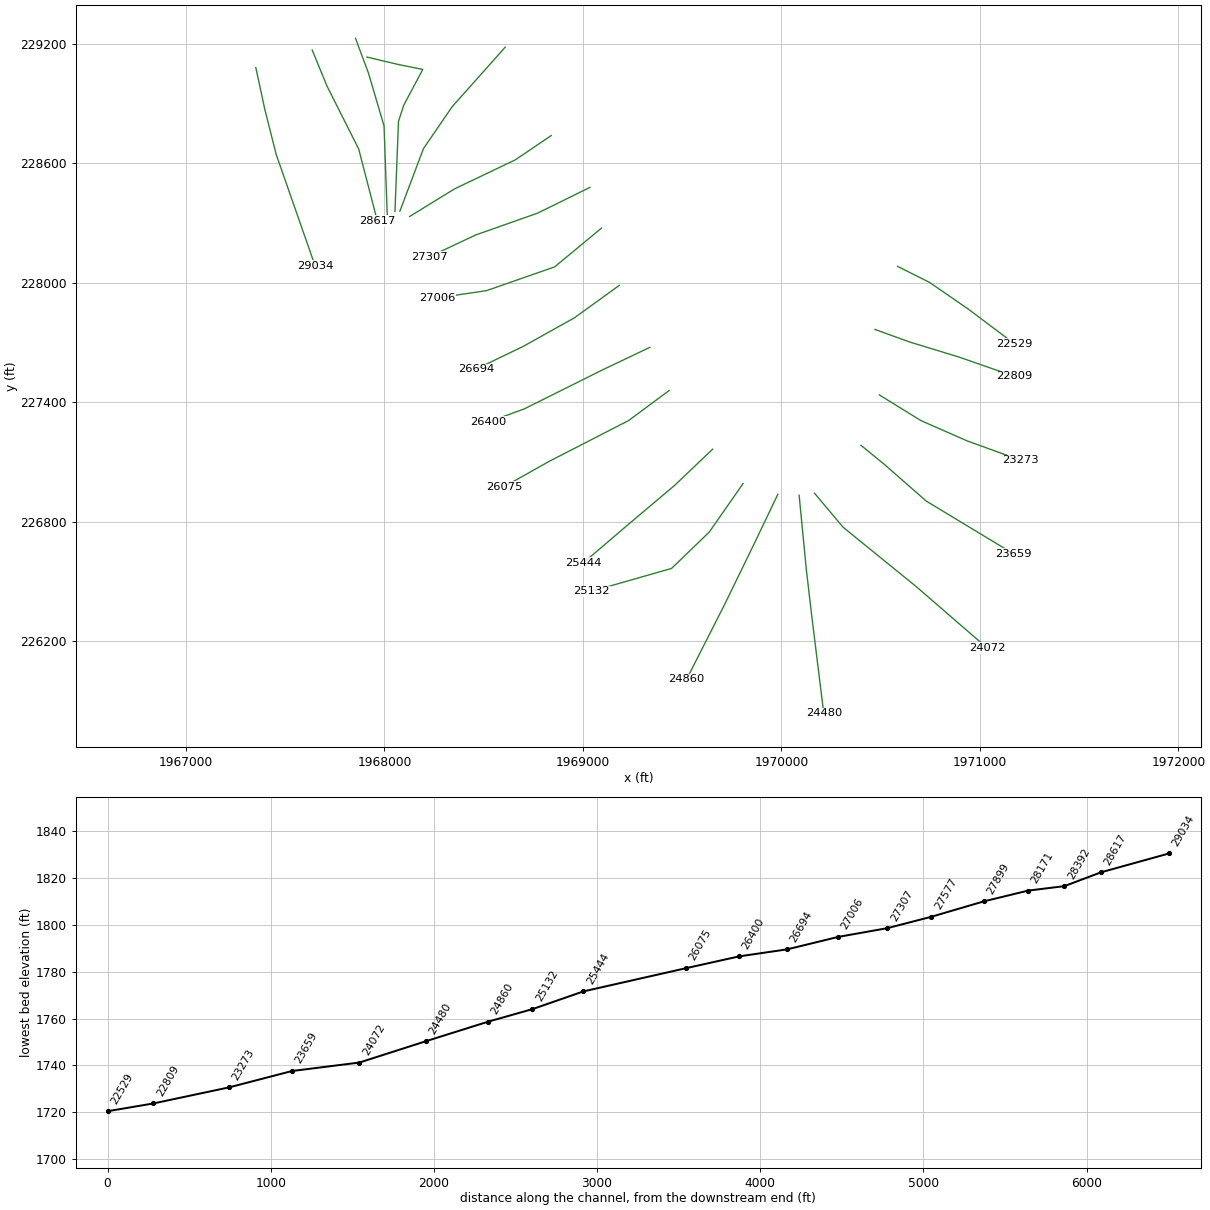
HEC-RAS study LTBLUESTRV.prj: LTBLUESTRV

--- LTBLUESTRV.g01 (geometry) --- (continued)

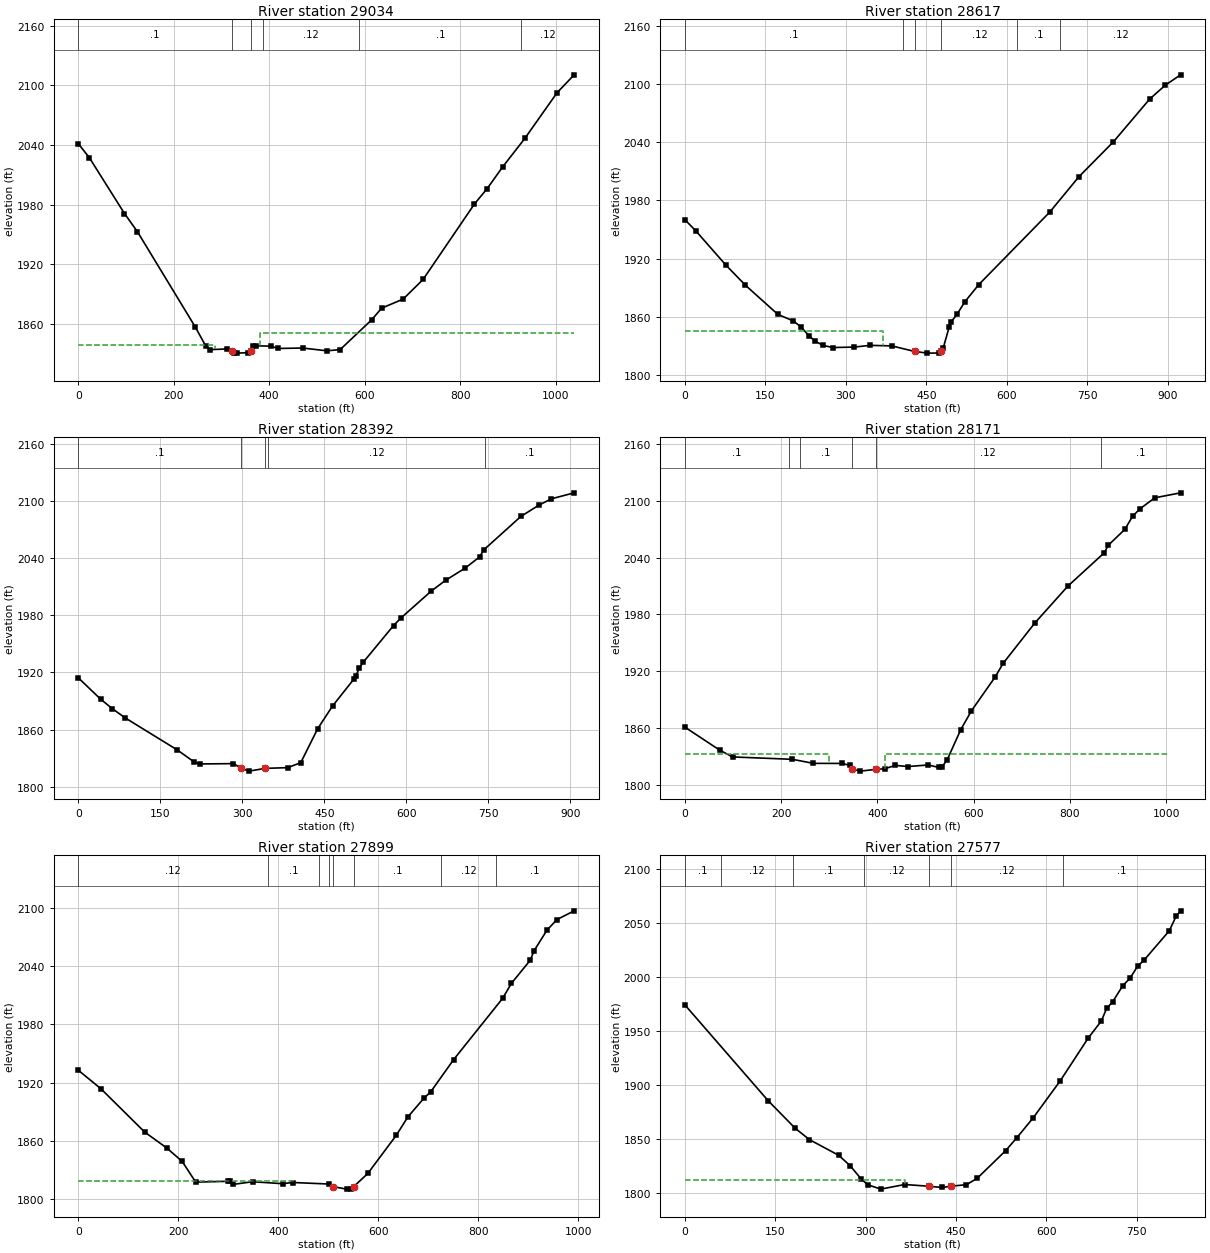
Type RM Length L Ch R = 1 ,29034   ,407.7,417.6,425
XS GIS Cut Line= 4
1967352.31803828229080.5499678061967398.45772483228867.597568354
1967455.24503135 228643.997548931967650.45139751228086.772103697
#Sta/Elev= 30
       0 2041.19    22.9 2027.29    96.7 1970.99   123.6 1952.88   244.7 1857.15
   267.2 1837.53   275.1 1834.06   312.4 1834.76  321.181833.022   325.9 1830.92
   332.7 1830.55   356.4 1831.01  361.26    1833   366.5 1837.43   373.3 1837.89
   403.8 1837.53   418.3 1835.23   470.4 1835.68   520.7 1832.88   548.6 1834.09
   614.6 1864.02   635.5 1875.76   680.7 1884.93   722.4 1904.64   830.1 1980.61
   856.6 1995.98   889.2 2017.91   935.7 2046.57  1003.3 2092.58    1039 2110.51
#Mann= 6 ,-1 , 0
       0      .1       0  321.18    .045       0  361.26      .1       0
  387.89     .12       0  588.59      .1       0  928.59     .12       0
#XS Ineff= 2 , 0
          287.06 1838.28  381.66         1850.66
Permanent Ineff=
       F       F
Bank Sta=321.18,361.26
XS Rating Curve= 0 ,0
Exp/Cntr(USF)=0,0
Exp/Cntr=0.3,0.1

Type RM Length L Ch R = 1 ,28617   ,231.3,225.1,219.5
XS GIS Cut Line= 4
1967636.25457088229169.2801342451967710.78791069 228988.27059471
1967870.50221028 228672.39120219 1967964.5561867228310.372123121
#Sta/Elev= 30
       0 1960.23    20.8 1948.47    76.4 1913.39     113 1892.51   173.4 1862.44
     202 1855.74   216.6 1849.51   231.8 1840.05   243.4 1834.63   257.1 1830.59
   275.5 1828.24   315.9 1828.73   345.3 1830.51   385.8 1829.92  427.981824.233
     452 1822.48     473 1822.58  478.231824.238   481.4 1827.63   492.4 1849.06
   496.1 1854.65     507 1862.41   521.8 1875.45   547.5 1893.05   679.9 1967.95
   734.1 2004.36   798.6 2040.52     866 2084.52   895.6  2099.1   923.8 2109.62
#Mann= 6 ,-1 , 0
       0      .1       0  405.75     .12       0  427.98    .045       0
  478.23     .12       0  619.72      .1       0  699.72     .12       0
#XS Ineff= 2 , 0
          369.63 1845.29
Permanent Ineff=
       F       F
Bank Sta=427.98,478.23
XS Rating Curve= 0 ,0
Exp/Cntr(USF)=0,0
Exp/Cntr=0.3,0.1

Type RM Length L Ch R = 1 ,28392   ,241.7,221.1,188.4
XS GIS Cut Line= 4
1967854.53078032229227.8420440941967920.19110348229052.156314546
1967998.27364995 228787.740418561968014.24507991228344.089586368
#Sta/Elev= 30
       0 1914.39      41  1891.9      62 1882.14      86 1872.28   181.1 1838.76
   212.1  1826.1   222.3 1824.09   283.9 1824.43  297.181819.865   312.1 1816.56
     342 1819.44   383.1 1820.23     407 1825.45   437.8 1860.91   465.1 1884.86
   503.8  1912.8   507.8 1916.39   514.4 1925.12   520.9 1930.49   576.7 1969.19
   589.9 1976.97   645.7 2005.35   671.9 2016.62   708.1 2029.59   734.3 2041.27
   741.4 2048.34   809.8 2083.68   842.7 2095.47   865.6 2102.11   907.2 2108.39
#Mann= 5 ,-1 , 0
       0      .1       0  297.18    .045       0     342      .1       0
  347.55     .12       0  743.26      .1       0
Bank Sta=297.18,342
XS Rating Curve= 0 ,0
Exp/Cntr(USF)=0,0
Exp/Cntr=0.3,0.1

Type RM Length L Ch R = 1 ,28171   ,262,271.9,252.3
XS GIS Cut Line= 6
1967912.23088622229133.7081836691968070.08419262229096.522799662
1968193.48001611229071.6769511621968097.65143636228892.442014957
1968071.03238643228810.8102618341968053.28635314228358.286412998
#Sta/Elev= 30
       0 1861.13    72.3 1836.86    99.2 1829.64   223.5 1827.12     267 1822.86
   325.7 1822.77   342.3 1820.91     348 1816.83   364.2 1814.66   396.4 1816.46
   415.1 1817.08   436.9 1820.72     464 1819.51   505.8 1821.17   527.5 1818.57
   534.5 1819.52   544.6  1826.1   573.4 1858.55   595.5 1878.35   644.8 1914.05
   661.3 1928.39   727.4  1971.1   795.8 2009.88   871.3 2044.97     880  2053.1
     914 2069.64   930.4 2083.67   945.4 2091.34   976.4 2103.03    1030 2108.28
#Mann= 6 ,-1 , 0
       0      .1       0 215.607     .12       0 239.354      .1       0
     348    .045       0   396.4     .12       0 863.845      .1       0
#XS Ineff= 2 ,-1
       0   300.4 1832.95  416.071003.572  1832.4
Permanent Ineff=
       F       F
Bank Sta=348,396.4
XS Rating Curve= 0 ,0
Exp/Cntr(USF)=0,0
Exp/Cntr=0.3,0.1

Type RM Length L Ch R = 1 ,27899   ,340.4,321.5,311.1
XS GIS Cut Line= 4
1968608.73719504229183.476960875 1968340.7720924228883.568998313
1968197.02922277228674.1658055191968078.13079974228360.061016327
#Sta/Elev= 30
       0 1932.73    44.8 1913.84   132.8 1868.92   176.6 1852.63   207.6 1838.76
   234.8 1817.31   299.9 1818.13   304.4 1817.94   309.5 1814.93   348.6 1817.71
     409 1815.67   429.1  1816.9   501.2 1815.33  509.041812.726   536.6 1810.06
     546 1810.44  551.171812.726   579.1 1826.19   636.1 1865.62   659.5 1884.71
   691.1 1903.74   705.1 1910.52   750.7 1943.65   848.9 2006.98   866.5 2022.44
   903.8 2046.08   912.1 2056.34   937.6 2077.37   957.7 2088.32     992  2097.3
#Mann= 8 ,-1 , 0
       0     .12       0     380      .1       0  482.18     .12       0
  502.18      .1       0  509.04    .045       0  551.17      .1       0
  726.17     .12       0  836.17      .1       0
#XS Ineff= 2 , 0
          432.39 1817.94
Permanent Ineff=
       F       F
Bank Sta=509.04,551.17
XS Rating Curve= 0 ,0
Exp/Cntr(USF)=0,0
Exp/Cntr=0.3,0.1

Type RM Length L Ch R = 1 ,27577   ,275.6,269.9,267.5
XS GIS Cut Line= 4
1968840.58948509228739.7336253541968660.45142428228618.018719403
1968353.72986129228471.9608322621968127.34013622228333.205839478
#Sta/Elev= 30
       0  1974.1   138.1 1885.44     183  1859.9   206.7 1849.32   255.5 1834.75
   274.2 1825.19   292.3 1813.16   303.2 1807.65     325 1803.48     365 1807.76
     405 1806.15   426.8 1805.01   442.5 1806.26   467.2 1807.57   484.9 1813.38
   532.2 1838.96   550.9 1851.02     578 1869.42   623.1 1903.84   669.2 1943.18
     691 1958.99     700 1970.78   709.8 1976.78   726.9 1991.91   738.5 1998.53
   751.4 2009.87   761.6 2015.16   803.8 2042.55   815.5 2056.39   822.7 2061.07
#Mann= 7 ,-1 , 0
       0      .1       0      60     .12       0     180      .1       0
   297.4     .12       0     405    .045       0   442.5     .12       0
  627.13      .1       0
#XS Ineff= 2 , 0
          365.06 1811.84
Permanent Ineff=
       F       F
Bank Sta=405,442.5
XS Rating Curve= 0 ,0
Exp/Cntr(USF)=0,0
Exp/Cntr=0.3,0.1

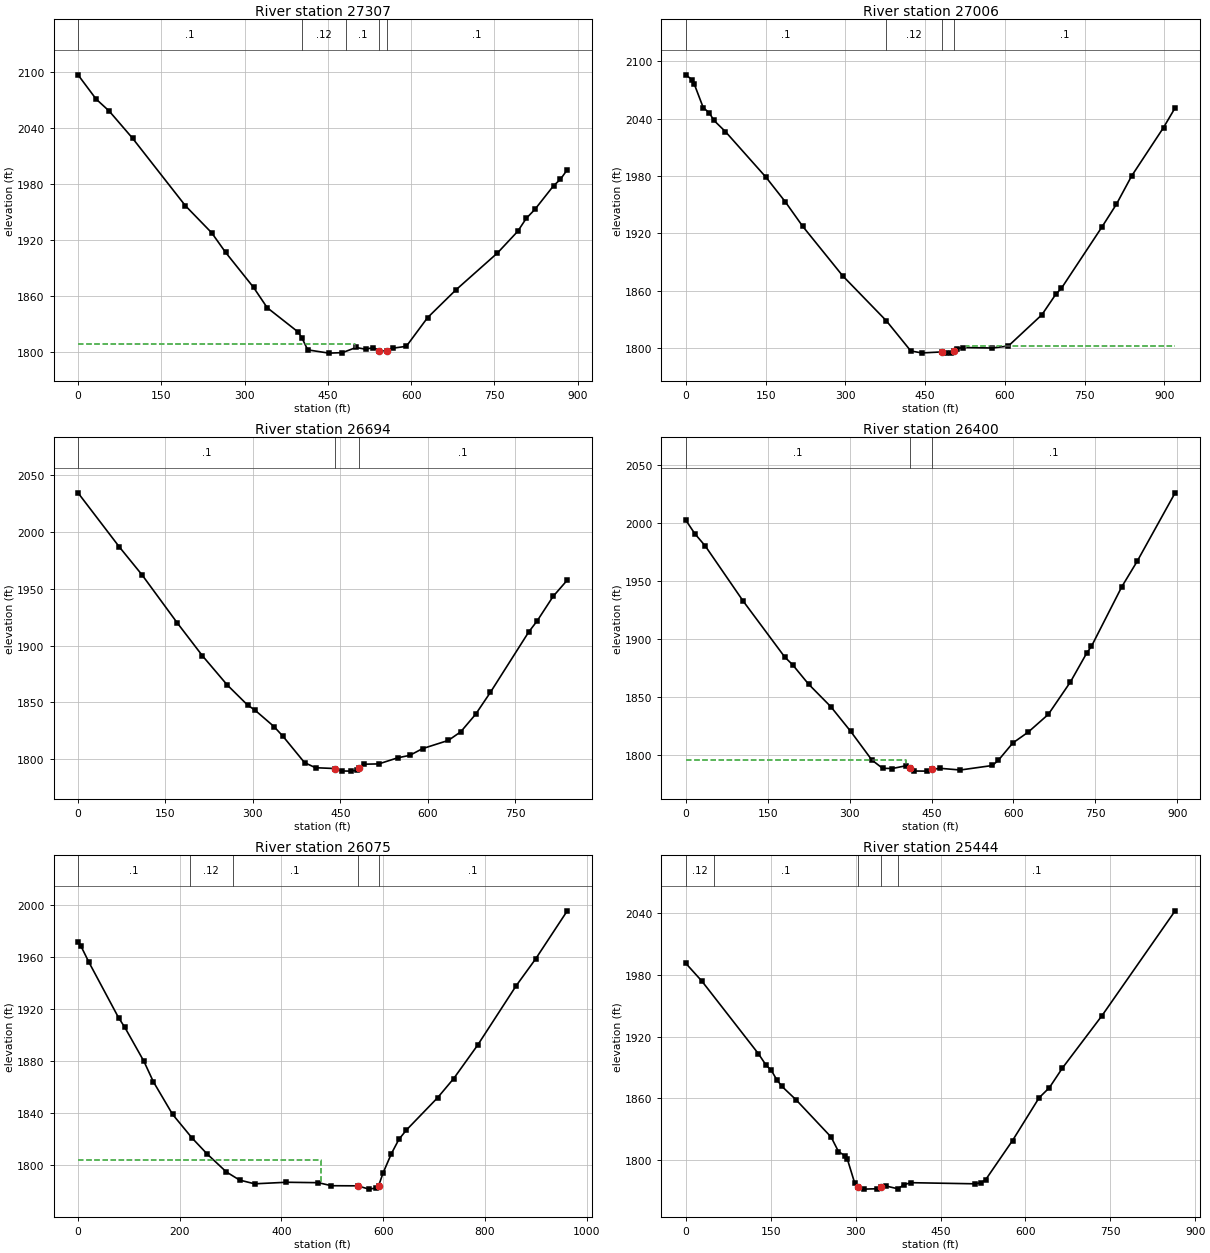
Type RM Length L Ch R = 1 ,27307   ,301.6,301.1,299.1
XS GIS Cut Line= 4
1969035.33333461228479.2637266191968772.42913776228350.245926311
1968460.83897852228240.702510955 1968227.1463591228131.159095599
#Sta/Elev= 30
       0 2096.83    32.5 2070.91    56.2 2057.98    98.3 2028.84   193.3 1956.63
   240.8 1927.51   265.8 1906.57   316.3 1868.94   340.7 1847.31   396.3 1821.31
   403.3 1814.95   413.7 1802.09     452 1798.61   476.3 1799.14   500.7 1804.66
     518 1802.78     532 1804.57   542.3 1801.06   556.3 1800.94   566.7 1803.87
   591.3  1805.9   629.6 1836.64   680.3  1866.2   755.4 1905.89   791.9 1929.11
   807.3 1943.01   822.8 1952.56   856.5 1977.99   868.7 1984.77   881.2 1995.14
#Mann= 5 ,-1 , 0
       0      .1       0  402.86     .12       0  482.86      .1       0
   542.3    .045       0   556.3      .1       0
#XS Ineff= 2 , 0
          499.04 1808.89
Permanent Ineff=
       F       F
Bank Sta=542.3,556.3
XS Rating Curve= 0 ,0
Exp/Cntr(USF)=0,0
Exp/Cntr=0.3,0.1

Type RM Length L Ch R = 1 ,27006   ,306.4,312.4,315.8
XS GIS Cut Line= 4
1969093.75648947228274.7826846211968857.62957193  228080.0388351
1968514.39353714227960.758227267  1968266.095129227924.243755482
#Sta/Elev= 30
       0 2085.87    11.4 2080.78    15.7 2076.39    32.7  2051.6    44.1 2046.09
    52.7 2038.28    74.4 2026.52   150.7 1978.82   186.8  1953.3   219.8 1927.48
     295 1875.74   377.2 1828.66   423.2 1797.12     444 1795.07   482.2 1796.14
   489.2 1794.87   499.6 1794.91  504.81 1796.72     510 1799.47   520.5 1800.74
     576 1800.23   606.6 1802.26   669.8 1835.01   696.3 1856.72   706.3 1862.49
   782.5 1926.57     810  1950.6   838.6 1980.11   898.6 2030.76   920.4 2051.37
#Mann= 4 ,-1 , 0
       0      .1       0  376.07     .12       0   482.2    .045       0
  504.81      .1       0
#XS Ineff= 2 , 0
                          526.45         1802.76
Permanent Ineff=
       F       F
Bank Sta=482.2,504.81
XS Rating Curve= 0 ,0
Exp/Cntr(USF)=0,0
Exp/Cntr=0.3,0.1

Type RM Length L Ch R = 1 ,26694   ,295.8,294.1,293.5
XS GIS Cut Line= 4
1969183.82551987227987.5355065771968957.43579481227824.437532602
1968699.40019419 227680.813943581968460.83897852227566.401931986
#Sta/Elev= 30
       0 2034.39    71.1 1986.63   109.8 1962.21   170.4  1919.8   213.4 1890.98
   255.7 1865.45   290.8 1847.65   303.4 1843.21   335.9 1828.82   351.6 1820.11
   388.4 1797.04   407.2 1792.56     441 1791.83   452.3  1789.7   467.6 1789.56
   478.6 1790.31   481.9 1791.97   489.8 1795.65   515.6 1795.91   548.5 1801.32
   568.8 1803.42   590.7 1809.35     635  1816.6   656.2 1824.14   681.7 1839.54
   707.1  1858.9   772.9 1912.08   787.2 1921.68   814.5  1943.2   838.9 1957.61
#Mann= 3 ,-1 , 0
       0      .1       0     441    .045       0   481.9      .1       0
Bank Sta=441,481.9
XS Rating Curve= 0 ,0
Exp/Cntr(USF)=0,0
Exp/Cntr=0.3,0.1

Type RM Length L Ch R = 1 ,26400   ,326.9,324.7,329.3
XS GIS Cut Line= 4
1969337.18630137227675.9453473421969101.05938383227563.967633867
1968704.26879043227366.7894862261968524.13072962227301.063437013
#Sta/Elev= 30
       0 2002.14    16.2 1990.75    35.9 1979.81   104.9 1932.74   181.2 1884.58
   195.7  1877.9   224.7 1861.35   265.5 1841.96   301.7 1820.88   340.8 1796.06
   360.4 1788.99   378.3  1788.8   403.9 1791.25   411.2 1788.83   418.6 1786.66
   441.2 1786.56   450.41788.085   465.6 1788.97   502.8 1787.53   561.5  1791.4
   572.4 1795.87   598.9 1810.74   627.2 1820.12   663.9 1835.31   704.4 1863.16
   734.7 1888.35   742.8 1893.69   798.6 1945.05   826.6  1966.8   896.2  2025.7
#Mann= 3 ,-1 , 0
       0      .1       0   411.2    .045       0   450.4      .1       0
#XS Ineff= 2 , 0
          402.64 1795.86
Permanent Ineff=
       F       F
Bank Sta=411.2,450.4
XS Rating Curve= 0 ,0
Exp/Cntr(USF)=0,0
Exp/Cntr=0.3,0.1

Type RM Length L Ch R = 1 ,26075   ,618.7,630.9,632.8
XS GIS Cut Line= 4
1969434.55822613227459.2928147491969230.07718414 227308.36633137
1968830.85229262227103.8852893721968604.46256755226977.301787183
#Sta/Elev= 30
       0 1971.84     5.2 1969.02    21.6 1956.04    79.8 1913.43      92 1906.06
   129.6 1879.89   148.3 1864.09   185.9 1839.11   224.6 1820.72   254.1 1808.52
   291.9  1794.7   317.7 1788.51   347.2 1785.62   409.7 1786.81   472.5 1786.49
   498.3 1784.16   549.9 1784.06   572.1 1781.53   586.8  1782.4   591.1 1784.13
     600  1794.1   616.3  1808.9     631 1819.85   645.8 1827.04   707.2 1851.93
   738.8 1866.66   785.6 1892.22   861.5    1938   899.9 1958.73   962.1 1995.71
#Mann= 5 ,-1 , 0
       0      .1       0     220     .12       0  304.15      .1       0
   549.9    .045       0   591.1      .1       0
#XS Ineff= 2 , 0
          477.08 1804.28
Permanent Ineff=
       F       F
Bank Sta=549.9,591.1
XS Rating Curve= 0 ,0
Exp/Cntr(USF)=0,0
Exp/Cntr=0.3,0.1

Type RM Length L Ch R = 1 ,25444   ,312.1,311.8,314.6
XS GIS Cut Line= 4
1969653.64505685227164.7427423471969461.33550544226982.170383421
1969232.51148225226789.8608320181969003.68745907226595.116982496
#Sta/Elev= 30
       0 1991.41    28.4 1974.08   128.2 1903.45   141.8 1892.28   150.9 1887.35
   160.6 1878.15   169.9 1871.55   194.8 1858.55   256.7  1822.3   269.7 1808.17
   281.2 1804.02   285.4  1800.8   298.3 1777.62  304.631773.771     314 1771.57
   337.3 1771.93   345.4 1774.07     354 1774.57   374.5 1771.92   386.1    1776
   397.8 1777.84   511.1 1776.75   521.3 1777.76   529.7 1780.68   577.3  1818.9
   624.3 1860.59   642.3  1870.3   665.5 1889.55   735.4 1940.54   864.6 2042.59
#Mann= 5 ,-1 , 0
       0     .12       0      50      .1       0  304.63    .045       0
   345.4     .04       0  375.17      .1       0
Bank Sta=304.63,345.4
XS Rating Curve= 0 ,0
Exp/Cntr(USF)=0,0
Exp/Cntr=0.3,0.1

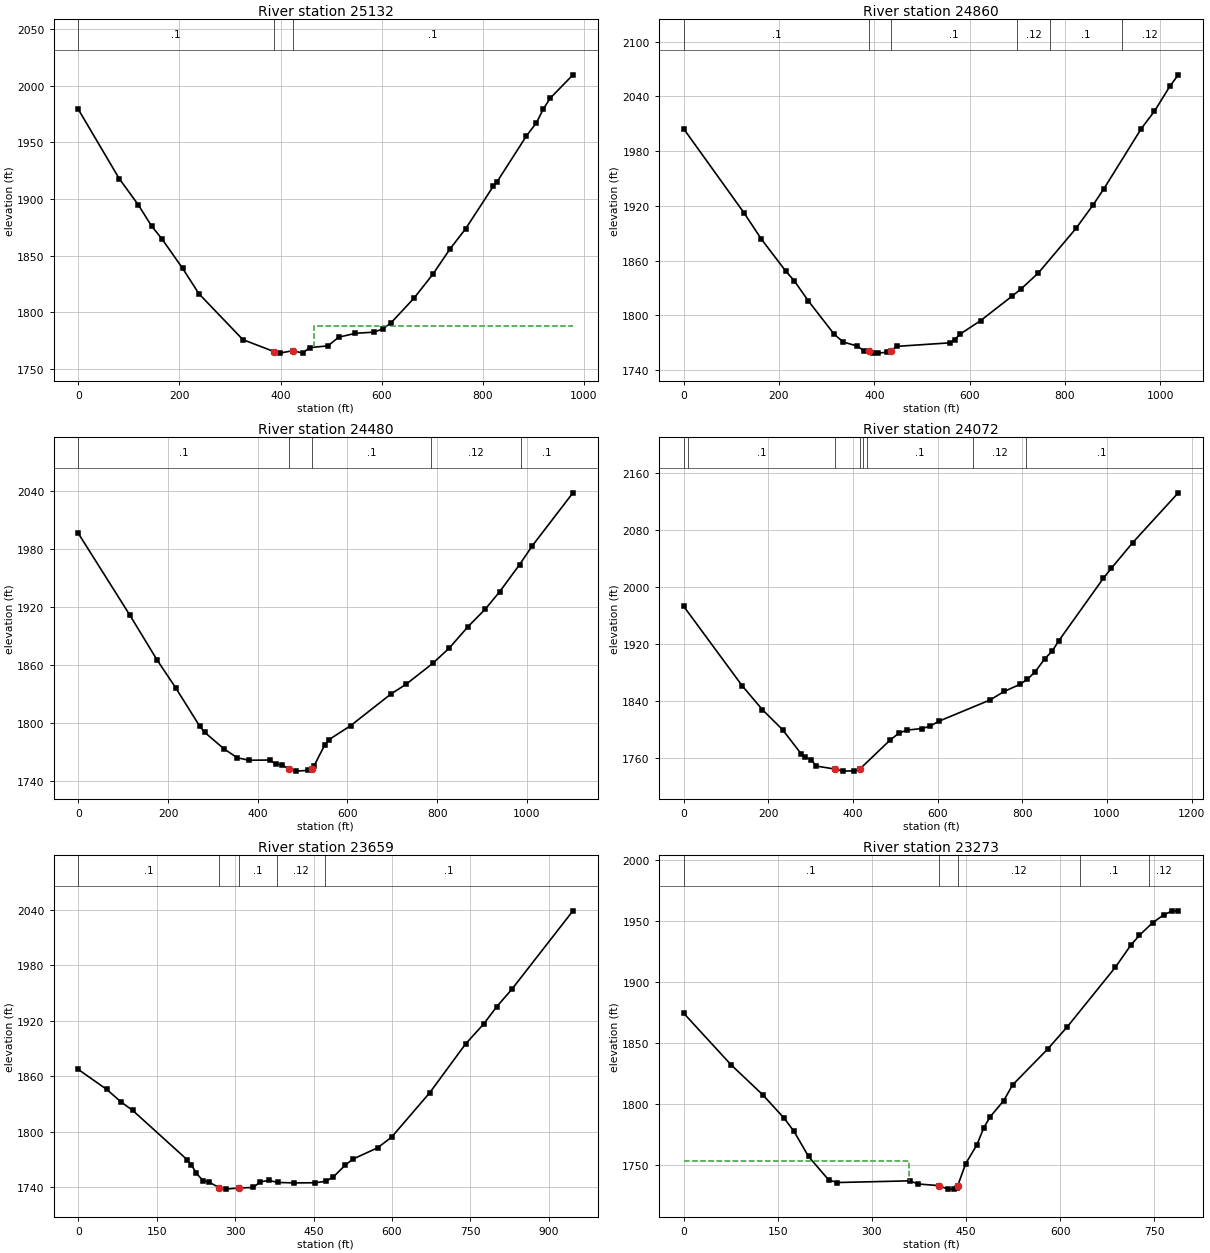
Type RM Length L Ch R = 1 ,25132   ,265.6,271.9,284.7
XS GIS Cut Line= 4
1969807.00583834226991.9075758971969636.60497001226748.477763995
1969446.72971673226565.9054050681969045.07052709226451.493393474
#Sta/Elev= 30
       0 1979.11    80.9 1917.96   118.5 1894.95     145 1876.08     165 1865.04
   206.5 1838.67   238.6 1816.37   325.5 1775.91     3871765.384     398 1764.04
   424.9 1766.18   443.7 1764.01   457.6 1768.88   493.6  1770.4   514.9 1778.03
   548.1  1781.5   585.4 1782.53   602.1 1785.39   617.5 1790.27   663.8 1812.45
   701.4 1833.72   735.5 1856.15   766.2 1873.81   820.8 1911.31   827.6 1914.76
   886.1 1955.49   906.1  1967.3   919.7 1979.45   933.3 1988.91   978.2 2009.49
#Mann= 3 ,-1 , 0
       0      .1       0     387    .045       0   424.9      .1       0
#XS Ineff= 2 , 0
                          465.62         1788.16
Permanent Ineff=
       F       F
Bank Sta=387,424.9
XS Rating Curve= 0 ,0
Exp/Cntr(USF)=0,0
Exp/Cntr=0.3,0.1

Type RM Length L Ch R = 1 ,24860   ,347.3,380.4,390
XS GIS Cut Line= 4
1969982.27530291226938.3530172781969867.86329132226699.791801614
 1969712.0682117226380.8987480221969522.19295842226008.451135812
#Sta/Elev= 30
       0 2004.73   126.9  1912.3   163.3 1883.49   214.2 1848.61   232.4 1837.75
   261.5 1816.01   316.3 1779.07   335.2 1770.75   363.8  1766.5   378.4  1761.2
   389.2 1761.34   396.4 1759.29   407.6 1758.64   426.3  1759.6  433.991761.451
   448.1 1766.09   558.5 1769.93   568.3  1773.2   579.2  1779.2     623 1794.26
   688.1 1820.77   708.2 1829.15   744.2 1846.59   822.9 1895.29     859 1921.21
     881 1938.35   960.1 2004.87   987.6 2023.85  1019.8 2051.04  1037.5 2063.72
#Mann= 6 ,-1 , 0
       0      .1       0   389.2    .045       0  433.99      .1       0
  699.49     .12       0  769.49      .1       0  919.49     .12       0
Bank Sta=389.2,433.99
XS Rating Curve= 0 ,0
Exp/Cntr(USF)=0,0
Exp/Cntr=0.3,0.1

Type RM Length L Ch R = 1 ,24480   ,367.2,407.7,426.3
XS GIS Cut Line= 4
1970089.38442015 226933.484421041970125.89889194226558.602510711
1970152.67617124226329.7784875231970213.53362422 225838.05026748
#Sta/Elev= 30
       0 1995.93   114.8  1911.5     176 1864.82     217 1836.44     271 1796.46
   281.5 1790.48   324.3 1773.47     354 1764.21   380.4 1761.54   426.4 1761.76
   439.8 1757.73   453.1 1756.81  469.151752.598   485.6 1750.31   512.5 1751.09
  520.361752.598   525.7 1755.94   548.8 1776.92   558.7 1782.82     607 1797.25
   697.6 1830.22   730.4 1839.94   790.1 1861.64   826.5 1877.24   868.6  1899.5
   906.9  1917.5   938.9 1935.44   983.4 1963.46  1011.6 1982.81  1102.5 2037.71
#Mann= 5 ,-1 , 0
       0      .1       0  469.15    .045       0  520.36      .1       0
  787.04     .12       0  987.04      .1       0
Bank Sta=469.15,520.36
XS Rating Curve= 0 ,0
Exp/Cntr(USF)=0,0
Exp/Cntr=0.3,0.1

Type RM Length L Ch R = 1 ,24072   ,404.6,413.5,406.8
XS GIS Cut Line= 4
1970167.28195996226943.2216135161970310.90554898226772.820745185
1970680.91886307226473.4020765451971036.32638845226166.680513548
#Sta/Elev= 30
       0 1973.11   138.8 1860.87     186 1827.69   233.9 1799.38   278.2  1765.1
   287.6 1760.58   301.6 1757.34   312.8  1748.4  357.621744.068   376.1 1741.19
   401.9 1741.64  416.191744.067   488.2 1785.09   509.2 1794.79   527.8 1798.88
   564.1  1801.1   582.9 1804.67     604 1811.62   722.8 1840.96   757.5 1853.24
     795 1863.33   812.1 1870.38   830.2 1880.68   852.9 1899.06   870.4 1909.77
   886.5 1924.74   991.2  2012.1  1009.8 2026.04    1061 2062.55  1168.3 2132.41
#Mann= 8 ,-1 , 0
       0     .08       0      10      .1       0  357.62    .045       0
  416.19      .1       0  422.85     .12       0  432.85      .1       0
  682.85     .12       0  808.84      .1       0
Bank Sta=357.62,416.19
XS Rating Curve= 0 ,0
Exp/Cntr(USF)=0,0
Exp/Cntr=0.3,0.1

Type RM Length L Ch R = 1 ,23659   ,373.4,385.6,387
XS GIS Cut Line= 4
1970400.97457939227184.217127299 1970517.8208891227089.279500658
1970729.60482545226904.272843612  1971170.212785226638.934348639
#Sta/Elev= 30
       0  1867.3    54.4 1845.64    82.3 1831.83   104.2 1822.83   208.3  1769.4
     216 1764.17   225.7 1754.82   238.8 1746.61   249.7 1745.23   269.4 1739.24
   282.3 1737.56   306.6 1738.77   334.5 1739.34   348.5 1745.53   364.4 1746.93
   382.5 1744.78     413  1744.3   453.7 1744.46     473 1746.06   487.2 1750.43
     511 1763.78   525.4 1770.12   572.3 1782.31   599.1 1793.81   671.9 1841.85
   740.8 1894.95   775.3 1916.49   800.3 1935.29     829 1954.02   946.1 2039.21
#Mann= 5 ,-1 , 0
       0      .1       0   269.4    .045       0   306.6      .1       0
  380.55     .12       0  471.76      .1       0
Bank Sta=269.4,306.6
XS Rating Curve= 0 ,0
Exp/Cntr(USF)=0,0
Exp/Cntr=0.3,0.1

Type RM Length L Ch R = 1 ,23273   ,458.3,464,452.5
XS GIS Cut Line= 4
1970493.47790791227437.3841316781970702.82754614 227308.36633137
1970936.52016557227206.1258103711971206.72725678 227108.75388561
#Sta/Elev= 30
       0 1874.83    75.8 1832.38   125.9 1808.01   160.6 1788.49     176 1777.86
   199.1 1757.33   231.2 1738.08   244.8 1735.98     360 1737.35   374.2 1734.76
   406.41733.484   420.9 1730.57   431.6 1730.59   435.2 1731.39  436.88 1733.48
   449.5 1751.43   467.4 1766.92   478.2 1780.71   488.6 1789.95   510.2 1803.12
   524.1  1815.9   579.9 1845.22   611.3 1863.53     688 1912.39   712.4 1930.32
   726.4 1938.62   747.3 1948.85   764.7 1955.18   778.7 1958.63   788.2 1958.35
#Mann= 5 ,-1 , 0
       0      .1       0   406.4    .045       0  436.88     .12       0
  630.99      .1       0  740.99     .12       0
#XS Ineff= 2 , 0
          359.89 1753.29
Permanent Ineff=
       F       F
Bank Sta=406.4,436.88
XS Rating Curve= 0 ,0
Exp/Cntr(USF)=0,0
Exp/Cntr=0.3,0.1

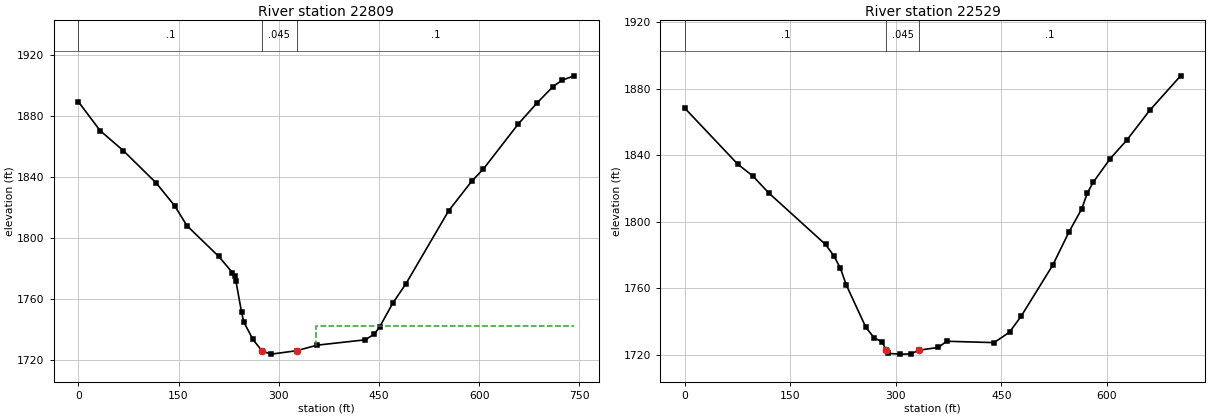
Type RM Length L Ch R = 1 ,22809   ,288.5,280.6,268.4
XS GIS Cut Line= 4
1970471.56922484227766.0143777461970646.83868941227702.722626651
1970895.13709755227627.2593849611971175.08138123227529.887460201
#Sta/Elev= 30
       0 1889.41    32.6 1870.38    67.5 1857.18   116.3 1836.15   144.2 1821.07
   162.7 1807.94   210.1 1787.86   230.7 1777.19   234.1 1774.75     236 1771.48
   244.4 1751.15   247.8 1744.66   261.5 1733.32   275.4 1725.53     289  1723.7
   326.7 1725.94   357.5 1729.58   429.6 1733.09   443.3 1736.93   451.3 1741.75
     471 1757.34   490.6 1769.99   554.4 1817.79   589.1 1837.28   606.5 1845.23
   658.6 1874.73   686.4 1888.38   710.7 1899.32   724.4 1903.52   742.3 1906.35
#Mann= 3 ,-1 , 0
       0      .1       0   275.4    .045       0   326.7      .1       0
#XS Ineff= 2 , 0
                           355.3         1742.21
Permanent Ineff=
       F       F
Bank Sta=275.4,326.7
XS Rating Curve= 0 ,0
Exp/Cntr(USF)=0,0
Exp/Cntr=0.3,0.1

Type RM Length L Ch R = 1 ,22529   ,248.1,235.7,218.5
XS GIS Cut Line= 4
1970585.98123643228082.4731332191970746.64491229228002.141295291
1970941.38876181227868.2548987451971172.64708312227695.419732294
#Sta/Elev= 30
       0 1868.27    75.1 1834.67    97.1 1827.33   119.1 1817.39     200 1786.33
   211.8 1779.53   221.2 1771.96   229.4 1762.07   257.3 1736.53   269.2 1730.13
   280.2 1727.85  286.33 1722.74   289.1 1720.83   306.1 1720.38     321 1720.47
  332.721722.742   360.4 1724.41   372.2 1728.12   439.6  1727.3   461.5 1733.59
     478 1743.15   523.1 1773.99   545.9 1793.75     564 1807.61   572.2 1817.32
   580.4 1823.69   604.5 1837.87     628 1848.94   660.8 1866.98   704.7 1887.73
#Mann= 3 ,-1 , 0
       0      .1       0  286.33    .045       0  332.72      .1       0
Bank Sta=286.33,332.72
XS Rating Curve= 0 ,0
Exp/Cntr(USF)=0,0
Exp/Cntr=0.3,0.1