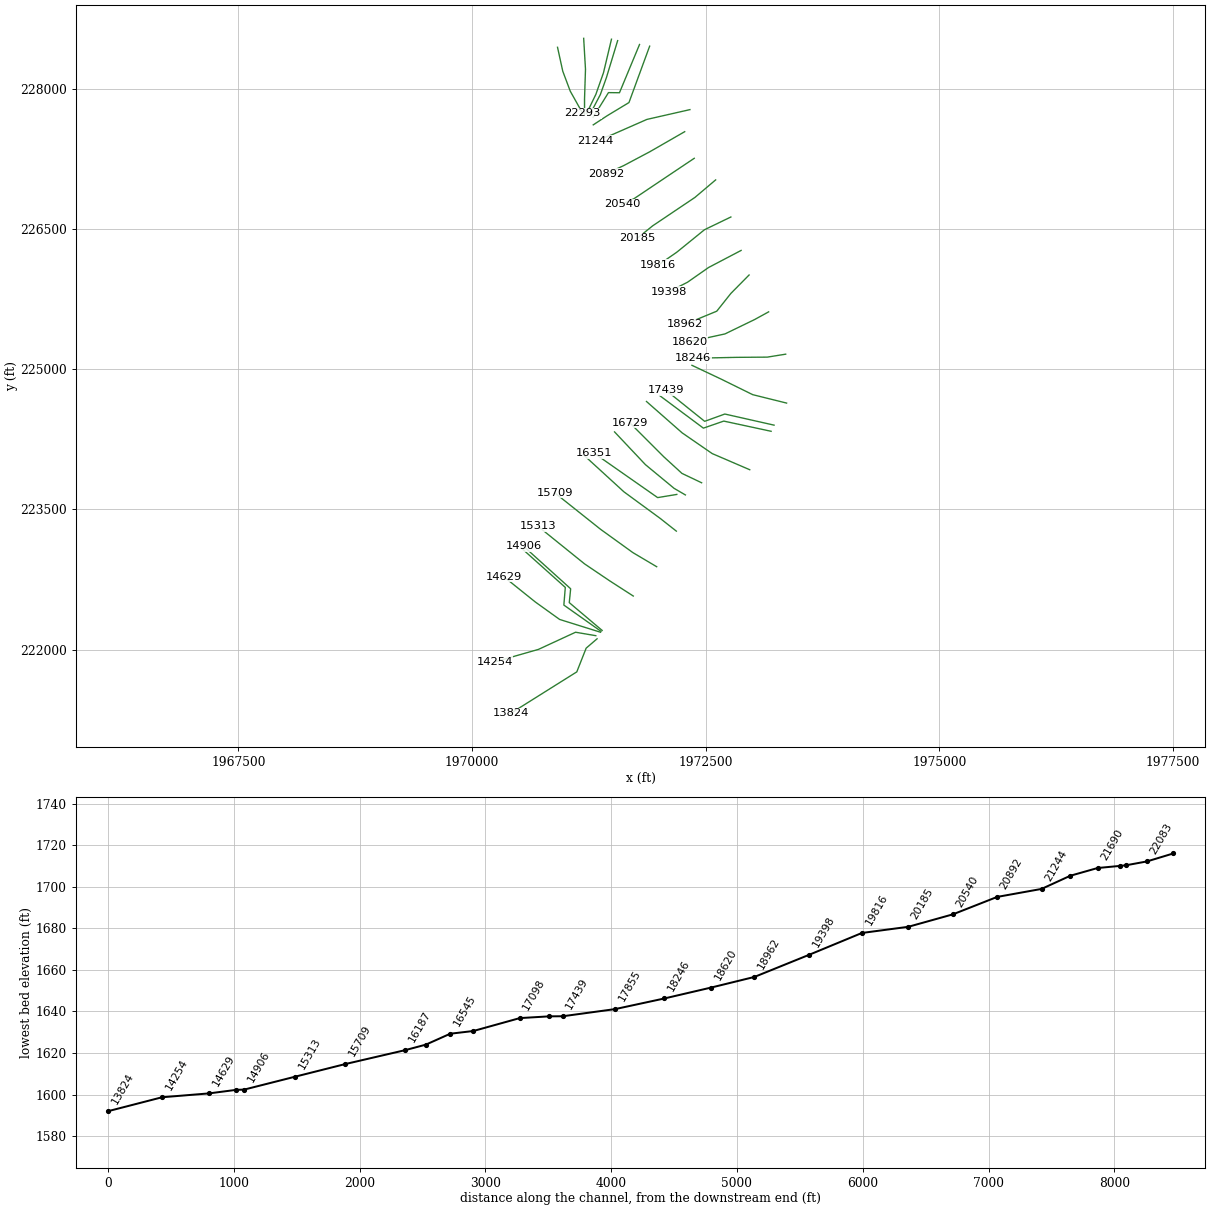
HEC-RAS study LTBLUESTRV.prj: LTBLUESTRV

--- LTBLUESTRV.g01 (geometry) --- (continued)

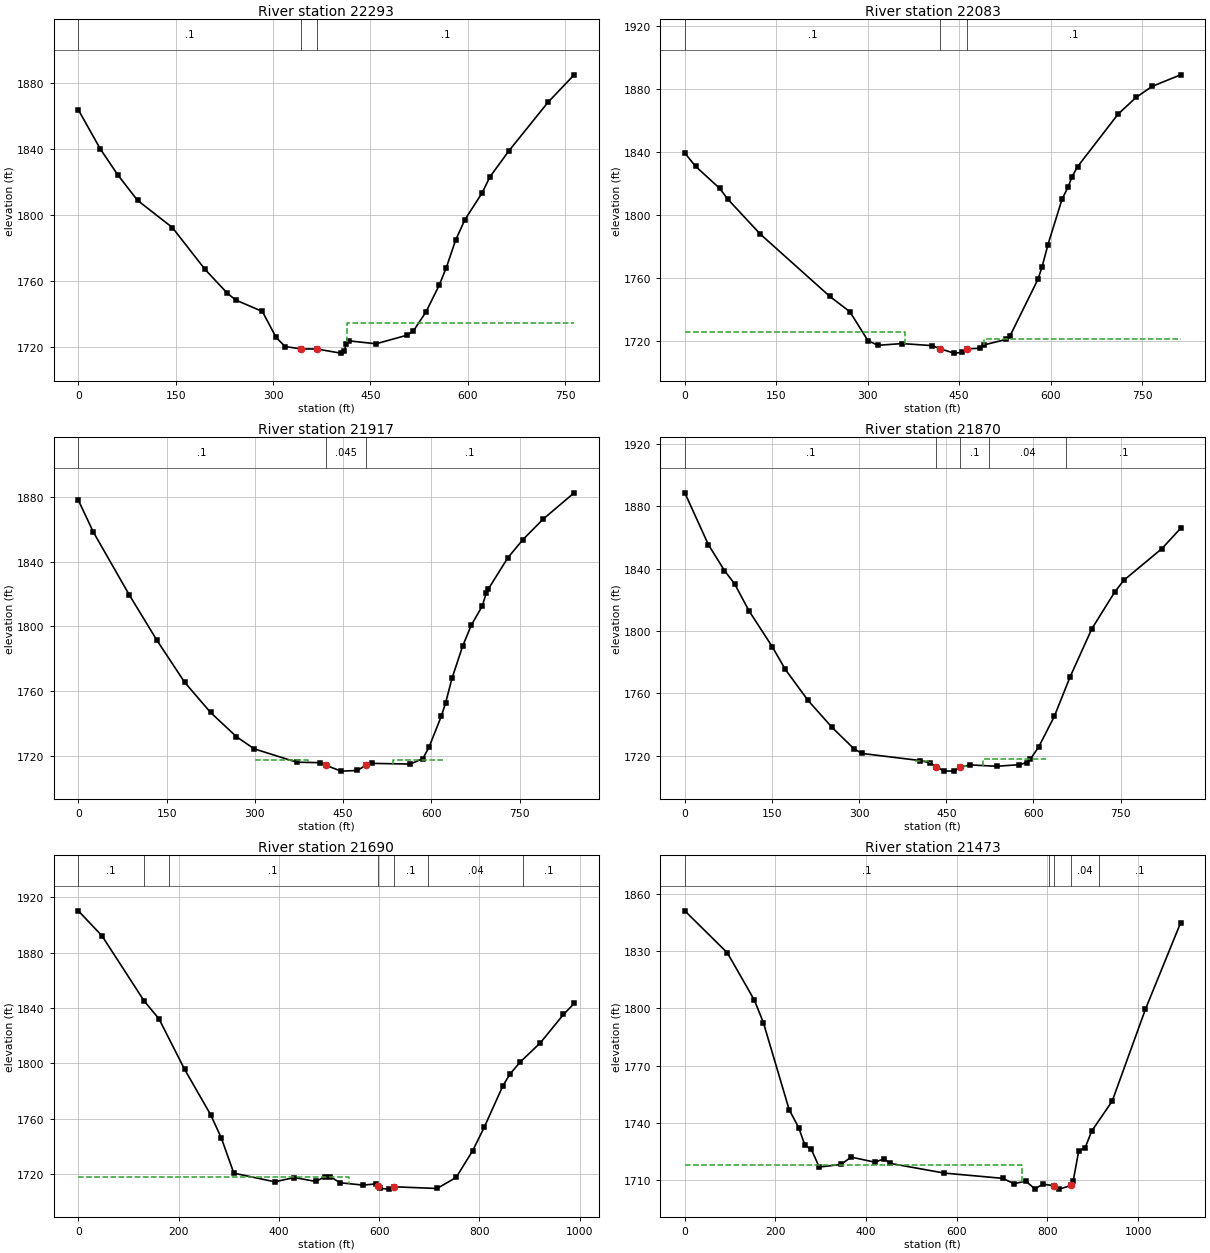
Type RM Length L Ch R = 1 ,22293   ,217.2,210.1,199.7
XS GIS Cut Line= 4
 1970914.6114825228445.1835529531970970.60033924228189.582250456
1971050.93217716227975.3640159821971184.81857371227736.802800317
#Sta/Elev= 30
       0 1863.46    33.7 1839.84      61 1823.91    91.2 1808.59   144.9 1792.12
   195.3 1766.72   228.9 1752.61   242.3 1748.24   283.6 1741.28   304.6 1725.61
   318.6 1720.02   343.1 1718.61   367.7 1718.51   404.1 1716.03   409.7 1717.46
   413.2 1721.85   416.7 1723.47   458.8  1721.7   506.6 1726.91   516.3 1729.49
   535.8 1741.06   555.9 1757.06   566.9 1767.74   581.3 1784.42   595.6 1796.86
     622    1813   634.3 1822.87   663.3 1838.51   723.6 1867.97     764 1884.65
#Mann= 3 ,-1 , 0
       0      .1       0   343.1    .045       0   367.7      .1       0
#XS Ineff= 2 , 0
                          414.61         1734.06
Permanent Ineff=
       F       F
Bank Sta=343.1,367.7
XS Rating Curve= 0 ,0
Exp/Cntr(USF)=0,0
Exp/Cntr=0.3,0.1

Type RM Length L Ch R = 1 ,22083   ,181.4,165.8,155.2
XS GIS Cut Line= 4
1971194.45162702228541.0214043991971213.85691442 228209.83783277
 1971203.5074278227891.591119408 1971203.5074278227728.586705247
#Sta/Elev= 30
       0 1839.25    17.6 1830.81    57.1 1816.84    70.2 1810.06   123.4 1787.91
   237.8 1748.21   270.7 1738.49   300.3 1720.14   316.7 1717.14   356.1 1718.24
   405.4 1716.96  418.331715.017   441.5 1712.18   454.6 1712.58   462.5 1714.86
   484.1 1715.32   490.7 1717.39   526.8 1720.87   533.4  1723.1   579.3 1759.14
   585.9 1766.92   595.7 1781.15   618.7 1809.92   628.6  1817.6   635.1 1824.21
   644.3 1830.64   710.6 1863.92   740.1 1874.53   766.4 1881.55   813.2 1888.89
#Mann= 3 ,-1 , 0
       0      .1       0  418.33    .045       0   462.5      .1       0
#XS Ineff= 2 , 0
          360.78 1725.57  490.44         1721.32
Permanent Ineff=
       F       F
Bank Sta=418.33,462.5
XS Rating Curve= 0 ,0
Exp/Cntr(USF)=0,0
Exp/Cntr=0.5,0.3

Type RM Length L Ch R = 1 ,21917   ,47.3,47.4,50.7
XS GIS Cut Line= 4
1971491.99936715228531.9656036121971406.61610259228173.614629623
1971325.11389551227942.0448666481971225.50008686227736.348820207
#Sta/Elev= 30
       0  1878.1    25.7 1858.24    86.4 1819.56   133.6 1791.29   180.5 1765.42
   224.6 1746.68   268.5 1731.69   298.8 1724.12     371 1715.86   411.4 1715.56
  420.761713.952   446.2 1710.33     474 1710.72  488.471713.952   498.4 1715.14
     564  1714.7   585.4 1718.13   595.8 1725.13   616.8 1744.43   624.1  1752.7
     635 1767.99   653.2 1787.97   667.8 1800.84   686.1 1812.44   693.3 1820.83
   696.4 1823.01   729.8 1842.48   755.3  1853.7   789.8 1866.42   842.4 1882.67
#Mann= 3 ,-1 , 0
       0      .1       0  420.76    .045       0  488.47      .1       0
#XS Ineff= 4 ,-1
  300.92  390.33 1717.16  398.18  408.37 1714.32  493.87   507.2 1714.27
  533.87  620.15 1717.16
Permanent Ineff=
       F       F       F       F
Bank Sta=420.76,488.47
XS Rating Curve= 0 ,0
Exp/Cntr(USF)=0,0
Exp/Cntr=0.5,0.3

Type RM Length L Ch R = 1 ,21870   ,217.2,179.7,148.5
XS GIS Cut Line= 4
1971557.97734431228516.4413736921971437.66456243 228120.57351073
 1971372.9802711227939.4574949951971257.84223252227720.824590287
#Sta/Elev= 30
       0 1888.67    40.7 1855.33    68.2  1838.8    85.9 1830.15   110.4 1812.96
   150.5 1789.89   172.8  1775.4   212.1 1755.39   253.3 1738.14     291  1724.4
   304.8 1721.38   404.2 1716.84   422.3 1715.38   432.6 1712.76   445.9 1710.11
   463.4 1710.03   473.4 1712.71   491.6 1714.01   536.4 1713.15   574.8 1714.14
   588.7 1715.52   594.3 1717.58   608.9 1725.48   635.8 1745.13   662.9 1770.43
   700.4 1801.39   739.6 1824.87   755.2 1832.46   820.8 1852.81   853.2 1865.87
#Mann= 5 ,-1 , 0
       0      .1       0   432.6    .045       0   473.4      .1       0
  523.75     .04       0  656.07      .1       0
#XS Ineff= 4 ,-1
  395.46  422.42 1716.29  428.16  430.46 1713.17  476.35  488.97  1713.1
  513.47  621.26  1717.8
Permanent Ineff=
       F       F       F       F
Bank Sta=432.6,473.4
XS Rating Curve= 0 ,0
Exp/Cntr(USF)=0,0
Exp/Cntr=0.5,0.3

Type RM Length L Ch R = 1 ,21690   ,199.8,216.7,232.1
XS GIS Cut Line= 4
1971792.13447894228475.0434272381971577.38263171227958.862782395
1971459.65722148227960.156468222 1971295.3591215227694.950873753
#Sta/Elev= 30
       0 1910.28    47.1 1892.21   131.5 1844.96   160.8 1832.17   211.8 1795.72
   263.9 1762.79   285.2 1745.94   310.1 1720.54   391.8  1714.3   430.9 1717.39
   473.5 1714.55   491.3 1717.86     502 1718.03   522.4 1713.59   567.9 1711.91
   594.1  1712.8  597.331711.397   600.8 1709.52   620.4    1709   630.3 1710.69
   715.3 1709.46   753.4 1717.44   786.1  1736.6   809.3  1753.6   846.3 1783.44
   860.6 1792.13   881.3 1800.96   921.2 1814.72   967.5 1835.31   988.8 1843.27
#Mann= 7 ,-1 , 0
       0      .1       0     130     .08       0     180      .1       0
  597.33    .045       0   630.3      .1       0   696.8     .04       0
   886.8      .1       0
#XS Ineff= 2 , 0
          539.84 1717.75
Permanent Ineff=
       F       F
Bank Sta=597.33,630.3
XS Rating Curve= 0 ,0
Exp/Cntr(USF)=0,0
Exp/Cntr=0.3,0.1

Type RM Length L Ch R = 1 ,21473   ,230,228.8,221
XS GIS Cut Line= 4
 1971900.5022207228457.3550435481971678.98109187227853.649110031
1971445.28847245227712.4598191271971296.79628718227615.087894366
#Sta/Elev= 30
       0 1851.15    93.9 1829.12   153.3 1804.41   173.3 1792.59   230.2 1746.94
   251.2 1737.52   265.1 1728.18   279.1 1726.09   296.6 1716.85   345.3 1718.23
   366.5 1722.09   418.9 1719.42   439.9 1721.16   452.7 1718.79   572.7 1713.68
   701.7 1710.92   726.1 1708.09   751.9 1709.51   772.1 1705.47   790.1 1707.84
   814.3  1707.1   826.1 1705.28  852.721707.266   856.5 1709.29   868.9 1725.27
   883.3 1727.09   897.6 1735.73   942.8 1751.42  1016.2 1799.65  1093.7 1844.88
#Mann= 5 ,-1 , 0
       0      .1       0  803.06     .04       0   814.3    .045       0
  852.72     .04       0  913.06      .1       0
#XS Ineff= 2 , 0
          744.41 1717.89
Permanent Ineff=
       F       F
Bank Sta=814.3,852.72
XS Rating Curve= 0 ,0
Exp/Cntr(USF)=0,0
Exp/Cntr=0.3,0.1

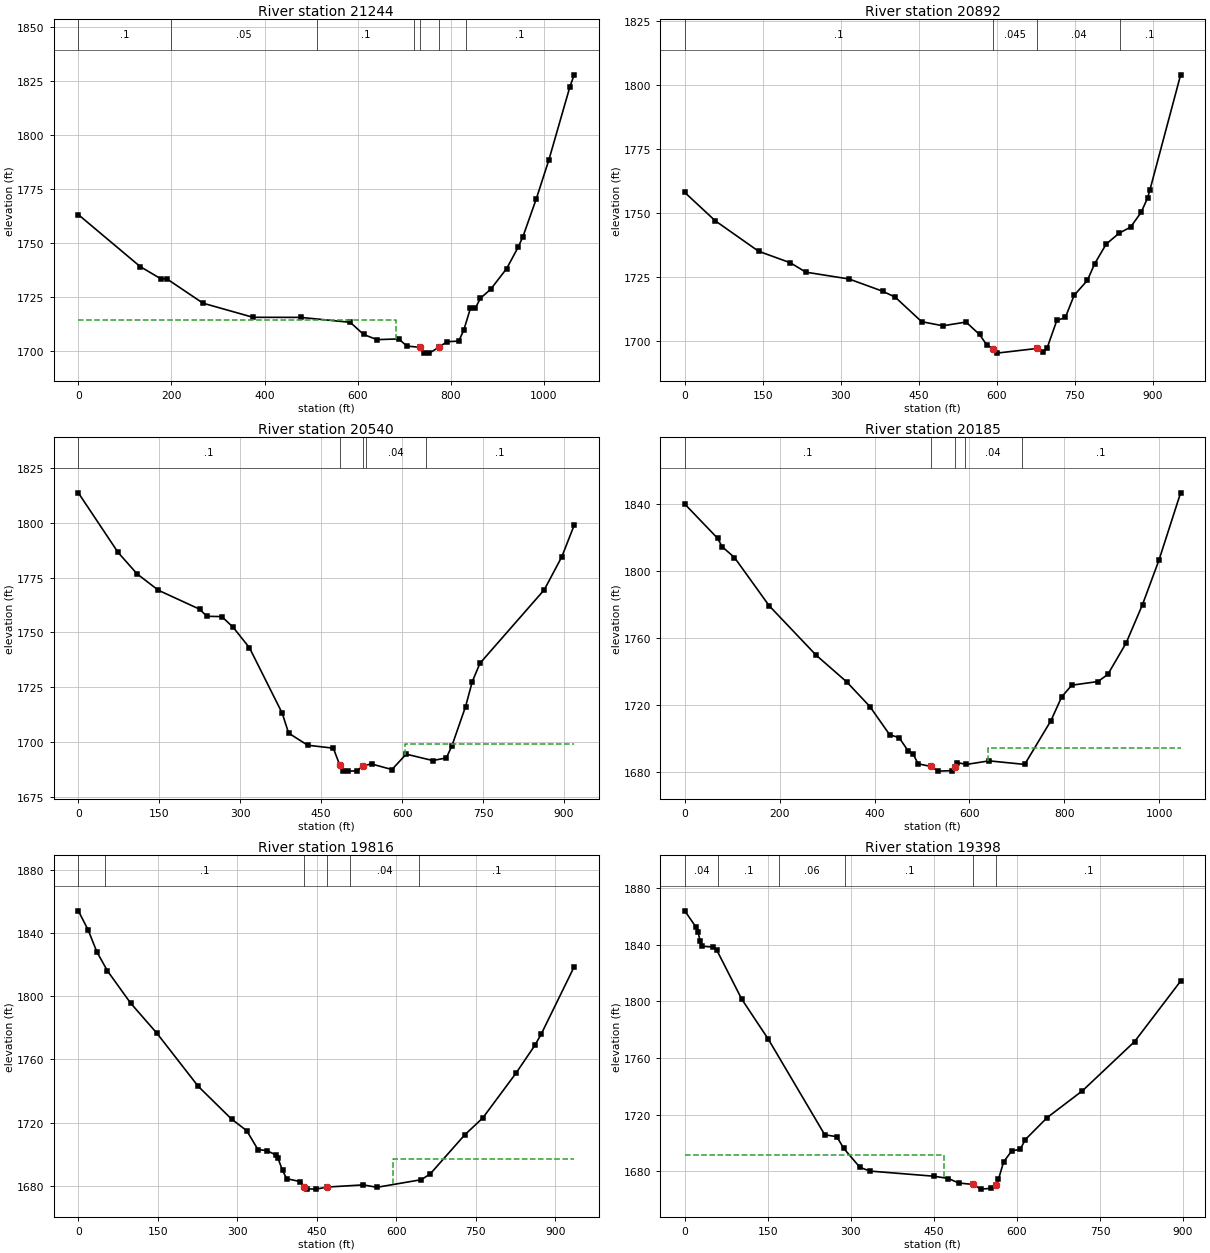
Type RM Length L Ch R = 1 ,21244   ,342.8,352.4,354.9
XS GIS Cut Line= 4
1972331.37298777227778.1858683411971871.29064327227673.511049223
1971489.10583859 227505.544479011971323.57356649227447.121324154
#Sta/Elev= 30
       0 1763.01     133 1738.95   176.7 1733.39   190.2 1733.29   267.6 1722.05
   375.2 1715.51   477.4 1715.47     584 1713.19   612.6 1707.57   641.3 1705.19
   687.9  1705.5   705.8  1702.2   733.8 1701.63   741.6 1699.14   753.8 1698.94
   773.9 1701.61   791.8 1704.23   816.9  1704.5   827.7 1709.55     842 1719.62
   852.7 1719.78   863.5 1724.34   885.7 1728.52   919.9 1738.08   944.3 1747.86
   954.7 1752.76   983.3 1770.21  1010.4 1788.25  1055.6 1822.12  1064.8 1827.68
#Mann= 7 ,-1 , 0
       0      .1       0     200     .05       0  511.84      .1       0
  721.84     .04       0   733.8    .045       0   773.9     .04       0
  831.84      .1       0
#XS Ineff= 2 , 0
          682.52 1714.04
Permanent Ineff=
       F       F
Bank Sta=733.8,773.9
XS Rating Curve= 0 ,0
Exp/Cntr(USF)=0,0
Exp/Cntr=0.3,0.1

Type RM Length L Ch R = 1 ,20892   ,340.3,352.4,357.6
XS GIS Cut Line= 4
1972275.38413103227542.0589507961971902.93651882227327.840716322
1971622.99223513227179.3485310611971435.55127997227091.713798777
#Sta/Elev= 30
       0 1757.87    58.5 1746.81   141.8 1734.91   203.2 1730.38   232.6 1726.74
   315.9 1724.06   380.2  1719.3   404.5 1716.99   455.4 1707.39   496.3 1705.78
   540.8 1707.24   566.8 1702.38   580.8 1698.28   592.8 1696.83   600.2  1695.1
   678.2 1696.95   689.4 1695.58   696.8 1697.12   715.4 1707.87   731.8 1709.02
   748.7 1717.68   774.1 1723.51   788.3 1730.06   810.3 1737.69   835.2 1741.95
   857.3 1744.35   877.7 1750.14     890 1755.77   894.5 1758.91   953.5 1803.83
#Mann= 4 ,-1 , 0
       0      .1       0   592.8    .045       0   678.2     .04       0
  836.55      .1       0
Bank Sta=592.8,678.2
XS Rating Curve= 0 ,0
Exp/Cntr(USF)=0,0
Exp/Cntr=0.3,0.1

Type RM Length L Ch R = 1 ,20540   ,354.2,354.2,353.7
XS GIS Cut Line= 4
1972377.62465203 227257.246070871972075.77168527227055.199326991
1971734.96994861226826.3753038031971603.51785018226765.517850828
#Sta/Elev= 30
       0 1813.74    73.5 1786.57     109  1776.7   148.3 1769.27   224.6 1760.63
   238.1 1757.39   265.8 1757.24   286.7  1752.4     317 1743.03   377.7 1713.16
   389.6 1704.06   424.9 1698.53   472.4 1697.19   484.61689.315   491.1 1686.84
     500 1686.71   517.2 1686.86   526.6 1689.14   543.2 1689.98     581 1687.43
   607.4 1694.46   656.6 1691.54   681.8 1692.74   692.1 1698.25   717.4 1716.15
   729.9 1727.62   744.1 1735.94   863.2 1769.48   895.7 1784.54   918.6 1798.93
#Mann= 5 ,-1 , 0
       0      .1       0   484.6    .045       0   526.6      .1       0
  533.23     .04       0  643.23      .1       0
#XS Ineff= 2 , 0
                          606.02         1699.04
Permanent Ineff=
       F       F
Bank Sta=484.6,526.6
XS Rating Curve= 0 ,0
Exp/Cntr(USF)=0,0
Exp/Cntr=0.3,0.1

Type RM Length L Ch R = 1 ,20185   ,363.4,368.9,372.7
XS GIS Cut Line= 4
1972606.44867522227025.9877495631972384.92754639226838.546794398
1971932.14809625226534.2595295211971769.05012228226402.807431093
#Sta/Elev= 30
       0 1839.97      69 1819.62      79 1814.47   104.7 1808.11   177.8 1779.36
   276.6 1749.94     341 1734.01   390.2 1719.22   431.9  1702.4   451.7 1700.71
   470.6 1692.86   481.1 1691.05   491.8 1685.09   518.8 1683.52     534 1680.72
   562.8 1681.01   569.8 1683.36   574.6 1685.82   593.5 1684.71   641.4 1686.84
   716.5 1684.73   771.8  1710.8   794.4 1724.95   815.7 1731.97   870.8 1734.13
   891.7 1738.38   930.3  1757.1   964.9 1780.08   999.4 1806.44  1045.2 1846.68
#Mann= 5 ,-1 , 0
       0      .1       0   518.8    .045       0   569.8      .1       0
  590.18     .04       0  710.18      .1       0
#XS Ineff= 2 , 0
                          639.54         1694.61
Permanent Ineff=
       F       F
Bank Sta=518.8,569.8
XS Rating Curve= 0 ,0
Exp/Cntr(USF)=0,0
Exp/Cntr=0.3,0.1

Type RM Length L Ch R = 1 ,19816   ,422.5,418.9,416.6
XS GIS Cut Line= 4
1972769.54664919226629.1971561631972487.16806739226492.876461497
1972190.18369687226251.8809477141971993.00554923226115.560253049
#Sta/Elev= 30
       0 1854.26    18.5 1842.14      35  1828.2    54.9 1816.21    98.6 1795.75
   148.2 1776.65   226.2 1742.98   289.2 1722.16   317.8 1714.81   338.9 1702.86
   355.8 1702.19   372.7 1699.44   376.8 1697.26   385.4  1689.6   393.1  1684.4
   419.2 1682.48   425.8 1679.24   431.9 1677.88   448.8 1677.75   469.9 1679.07
   537.9 1680.44   563.4  1678.9   647.3 1683.74   664.3 1687.47   729.3 1712.21
   763.2 1722.87   825.6 1751.14   861.4 1768.88   873.5 1776.05   935.7 1818.74
#Mann= 6 ,-1 , 0
       0     .04       0      50      .1       0   425.8    .045       0
   469.9      .1       0  513.56     .04       0  643.56      .1       0
#XS Ineff= 2 , 0
                          594.56          1696.6
Permanent Ineff=
       F       F
Bank Sta=425.8,469.9
XS Rating Curve= 0 ,0
Exp/Cntr(USF)=0,0
Exp/Cntr=0.3,0.1

Type RM Length L Ch R = 1 ,19398   ,421.4,435.6,439.5
XS GIS Cut Line= 4
1972879.09006455226271.3553326661972530.98543353 226088.78297374
1972304.59570846225930.5535960031972102.54896458225828.313075004
#Sta/Elev= 30
       0 1863.98    20.2 1852.46      24 1848.91    27.7 1842.48    31.4 1838.93
    51.1 1838.38    57.3 1836.57   102.9 1801.51   150.8 1773.29   252.8  1705.7
   274.7 1704.31   286.8 1696.21   316.6 1682.55   335.1    1680   450.6 1676.37
   476.2 1674.76   494.6 1671.61     521 1670.55   534.6 1667.26     554 1667.85
   562.6 1670.38   566.6 1674.14   575.9 1686.45   590.7 1694.38   605.8 1695.31
   615.2 1702.31   654.7 1717.86   718.4  1736.8   812.4 1771.51   895.7 1814.29
#Mann= 6 ,-1 , 0
       0     .04       0      60      .1       0     170     .06       0
     290      .1       0     521    .045       0   562.6      .1       0
#XS Ineff= 2 , 0
          468.48 1691.12
Permanent Ineff=
       F       F
Bank Sta=521,562.6
XS Rating Curve= 0 ,0
Exp/Cntr(USF)=0,0
Exp/Cntr=0.3,0.1

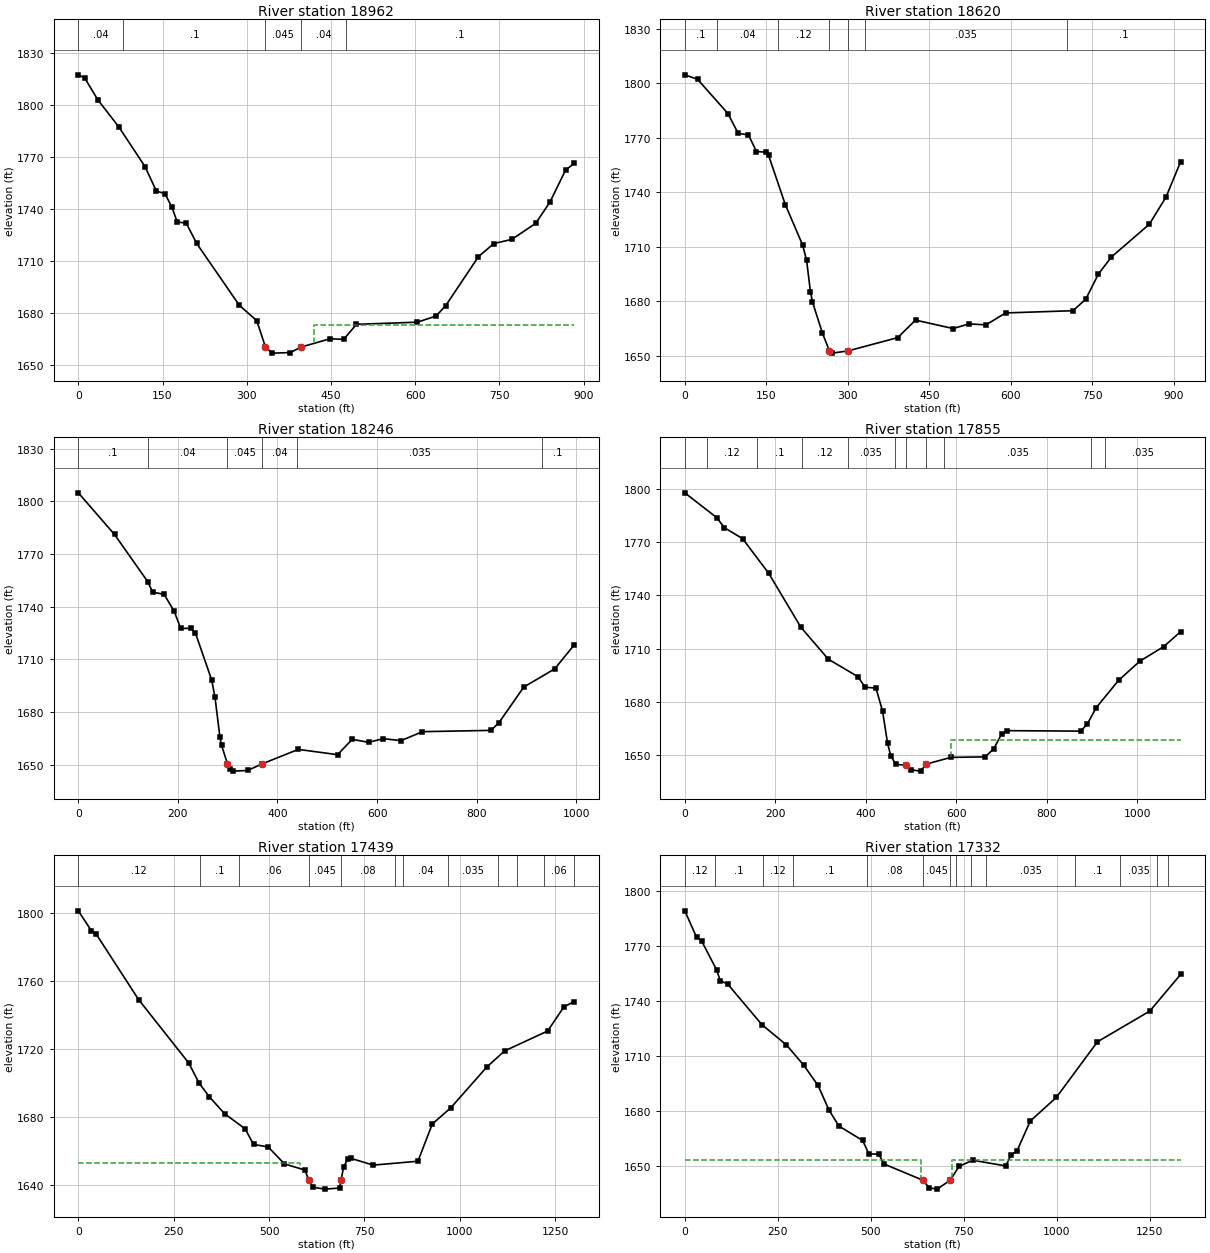
Type RM Length L Ch R = 1 ,18962   ,357.8,342.1,327.2
XS GIS Cut Line= 4
1972964.29049871226008.4511358121972769.54664919225811.272988171
1972618.62016581225621.3977348871972282.68702539225482.642742103
#Sta/Elev= 30
       0 1817.65    11.4  1815.8    34.7 1803.19    72.1 1787.53   118.8  1764.5
   138.9 1750.44   154.2 1748.85   166.7 1741.07     176 1732.56   192.3 1731.76
   210.8 1720.06   286.9 1684.21   317.8 1675.39   333.31660.094   345.6 1656.59
   377.7 1656.91  396.751660.096   448.6 1664.93   472.6 1664.53   495.3 1673.26
   603.9  1674.5   637.1 1678.05   654.2 1684.02   712.7 1712.44     740 1720.01
     772  1722.4   814.6 1731.71   840.1 1744.08   867.8 1762.52   883.1 1766.37
#Mann= 5 ,-1 , 0
       0     .04       0      80      .1       0   333.3    .045       0
  396.75     .04       0  477.14      .1       0
#XS Ineff= 2 , 0
                          419.77         1672.76
Permanent Ineff=
       F       F
Bank Sta=333.3,396.75
XS Rating Curve= 0 ,0
Exp/Cntr(USF)=0,0
Exp/Cntr=0.3,0.1

Type RM Length L Ch R = 1 ,18620   ,388.7,374.1,356
XS GIS Cut Line= 4
1973173.64013695 225614.094840531973022.71365357225531.328704484
 1972706.2548981225377.9679229851972326.50439153225295.201786939
#Sta/Elev= 30
       0 1804.66    23.4 1802.22    79.5  1783.3    98.2 1772.45   117.2 1771.58
   131.9 1762.45   148.6 1762.12   154.3 1760.28     185 1733.21   216.8 1711.02
   224.1 1702.68   231.3 1685.21     235 1679.66   253.2 1662.59   266.1 1652.79
   271.4 1651.51   300.6 1652.75   391.8 1660.04   424.6 1669.68   493.8 1665.04
     523 1667.59   554.3 1667.07   590.4 1673.63   714.5 1674.85     738 1681.25
     761 1694.91     785 1704.39   854.8  1722.4   885.7 1737.44   912.5 1756.87
#Mann= 7 ,-1 , 0
       0      .1       0      60     .04       0  172.13     .12       0
   266.1    .045       0   300.6     .04       0  332.13    .035       0
  703.79      .1       0
Bank Sta=266.1,300.6
XS Rating Curve= 0 ,0
Exp/Cntr(USF)=0,0
Exp/Cntr=0.3,0.1

Type RM Length L Ch R = 1 ,18246   ,405,390.4,364.7
XS GIS Cut Line= 4
1973356.21249588225161.3153903921973159.03434824225129.669514845
1972827.96980405225127.2352167261972363.01886332 225117.49802425
#Sta/Elev= 30
       0 1804.91    72.7 1781.15   139.2 1754.34   149.2 1748.31   172.2 1747.02
   192.4 1737.46   205.6 1727.58   225.3 1727.67   235.1 1725.03   267.9 1698.13
   274.5 1688.24   284.3 1665.78   287.6 1660.98  299.521650.392     304 1647.29
   310.6 1646.23   340.1  1646.6  369.291650.391   441.8 1658.62   520.6 1655.61
   550.1 1664.35   582.9 1662.67   612.4 1664.72   648.2 1663.62   691.2 1668.73
     829 1669.47   844.9 1673.93   894.6 1694.15     957 1704.59   995.8 1718.19
#Mann= 6 ,-1 , 0
       0      .1       0     140     .04       0  299.52    .045       0
  369.29     .04       0   439.7    .035       0  930.77      .1       0
Bank Sta=299.52,369.29
XS Rating Curve= 0 ,0
Exp/Cntr(USF)=0,0
Exp/Cntr=0.3,0.1

Type RM Length L Ch R = 1 ,17855   ,365.9,415.9,454.5
XS GIS Cut Line= 4
1973365.94968835224637.9412948031973003.23926862224728.010325206
1972667.30612819  224893.54259731972353.28167084 225042.03478256
#Sta/Elev= 30
       0 1797.67    70.5 1783.73    87.4 1778.07   127.7  1771.9   185.5 1752.37
   256.4 1722.09   317.1 1704.11   382.2  1694.3   398.6 1688.32   422.4 1687.83
     437 1674.85     448 1656.88   455.3 1649.59   466.3 1644.94   489.2 1644.43
   499.2 1641.89   521.1 1641.13  533.471645.063   587.8 1648.86   663.8 1649.15
   682.8 1653.77     700 1661.96   711.3  1663.9   874.9 1663.63   889.5 1667.66
   909.1 1676.84   958.4 1692.16  1005.2 1702.93  1058.2 1711.17  1095.6 1719.56
#Mann= 11 ,-1 , 0
       0      .1       0      50     .12       0     160      .1       0
     260     .12       0     360    .035       0  463.73     .04       0
   489.2    .045       0  533.47     .04       0  573.73    .035       0
  898.23     .05       0  928.23    .035       0
#XS Ineff= 2 , 0
                          587.97          1658.6
Permanent Ineff=
       F       F
Bank Sta=489.2,533.47
XS Rating Curve= 0 ,0
Exp/Cntr(USF)=0,0
Exp/Cntr=0.5,0.3

Type RM Length L Ch R = 1 ,17439   ,114.8,107.2,108.2
XS GIS Cut Line= 4
1973232.06329181224401.8143772581972704.97174571224520.718313732
1972489.16408221224442.6676356071972075.77168527224774.261989468
#Sta/Elev= 30
       0 1801.34    33.8 1789.76    47.3 1787.51   158.2 1749.08   289.4 1711.87
   316.3 1700.16   343.2 1692.06   383.6    1682   437.2 1673.18   459.2 1663.99
   497.9 1662.46   540.3 1652.52     594 1648.91  603.961643.095     615 1638.86
   646.3 1637.69   684.8 1638.34  688.961643.087   695.2 1650.52   705.7 1655.25
   713.8 1655.83   773.2 1651.81   890.2  1654.1     928 1676.02   976.2 1685.47
    1071 1709.54  1117.3 1718.93  1230.3 1730.67  1272.9 1744.86  1299.8 1747.99
#Mann= 12 ,-1 , 0
       0     .12       0     320      .1       0     420     .06       0
  603.96    .045       0  688.96     .08       0  829.82     .06       0
  849.82     .04       0  969.82    .035       0 1099.82      .1       0
 1149.82    .035       0 1219.82     .06       0 1299.78     .04       0
#XS Ineff= 2 , 0
             580 1653.31     710         1653.31
Permanent Ineff=
       F       F
Bank Sta=603.96,688.96
XS Rating Curve= 0 ,0
Exp/Cntr(USF)=0,0
Exp/Cntr=0.5,0.3

Type RM Length L Ch R = 1 ,17332   ,277.8,234.6,184.2
XS GIS Cut Line= 4
1973200.41741626224336.0883280441972693.29757152224445.231914294
1972475.40254911224369.7548503721972007.61133794 224718.27313273
#Sta/Elev= 30
       0 1789.09    31.6 1774.72      45 1772.78    85.3 1757.01    95.3 1751.12
   115.5 1749.18   207.4  1727.1   273.2 1716.12   320.2 1704.92   358.2 1694.04
   387.3 1680.77   414.1 1671.98   477.9 1664.12   494.7 1656.85   521.6 1656.63
   535.5 1651.31   639.31642.536     657 1638.38   678.1 1637.64  713.811642.535
   736.9 1650.01   773.8 1653.38   862.9 1650.26     877 1656.42   892.3 1658.17
   928.6 1674.72   998.9  1687.6  1109.1 1717.82  1249.8 1734.53  1332.7 1754.47
#Mann= 14 ,-1 , 0
       0     .12       0      80      .1       0     210     .12       0
     290      .1       0     490     .08       0   639.3    .045       0
  713.81     .08       0  728.73     .04       0  769.33     .08       0
  809.33    .035       0 1049.33      .1       0 1169.33    .035       0
 1269.33     .06       0 1299.33     .04       0
#XS Ineff= 2 , 0
             634 1653.31     718         1653.31
Permanent Ineff=
       F       F
Bank Sta=639.3,713.81
XS Rating Curve= 0 ,0
Exp/Cntr(USF)=0,0
Exp/Cntr=0.5,0.3

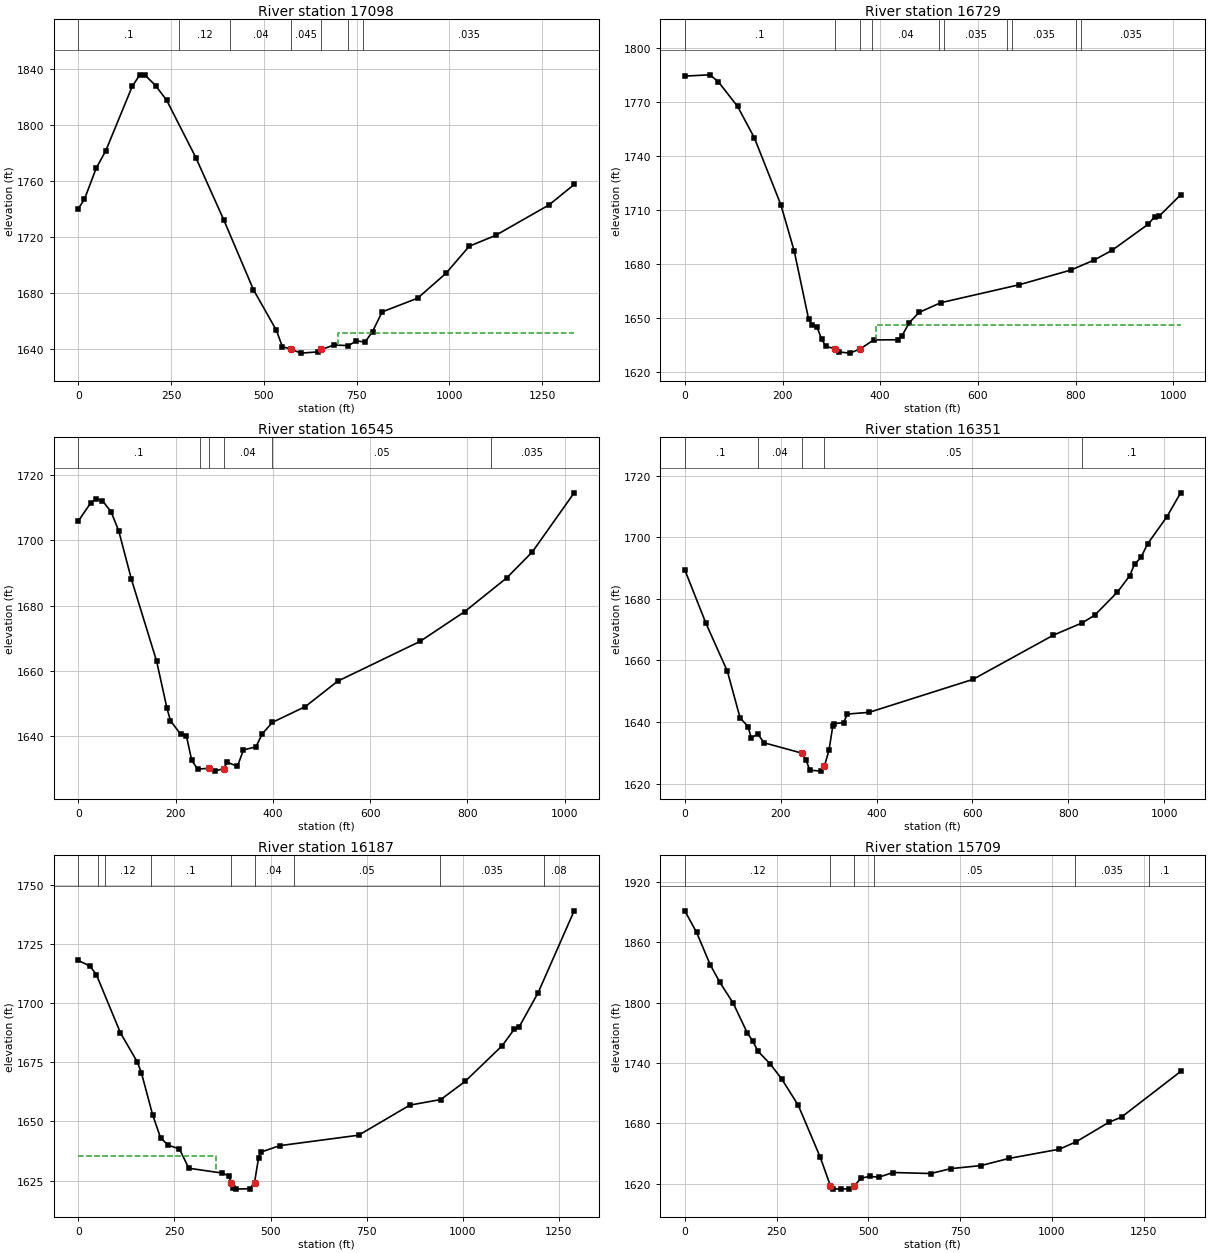
Type RM Length L Ch R = 1 ,17098   ,369.9,369.1,355.4
XS GIS Cut Line= 4
1972971.59339307223924.6919459291972569.93420343 224097.52711238
1972248.60685172224319.0482412111971866.42204704224654.981381636
#Sta/Elev= 30
       0 1739.97    16.6  1746.8    48.3 1768.95    73.8 1781.23   145.2 1827.25
   165.7 1835.56   180.7  1835.1   208.1 1827.89   238.1 1817.41   316.7 1776.44
   391.7 1732.15     472 1682.09   533.8  1653.1   549.8 1641.48  574.231639.447
   600.6  1636.8   645.4 1637.69  655.271639.447   690.2 1642.64     728 1642.12
     749 1645.53   772.8 1644.72   792.9 1652.15   818.8 1666.23   914.5 1676.04
   990.5 1693.69  1053.6 1713.15  1124.6 1720.88  1268.7 1742.65  1336.4 1757.24
#Mann= 7 ,-1 , 0
       0      .1       0     270     .12       0     410     .04       0
  574.23    .045       0  655.27     .12       0  727.27     .06       0
  767.27    .035       0
#XS Ineff= 2 , 0
                             700         1650.99
Permanent Ineff=
       F       F
Bank Sta=574.23,655.27
XS Rating Curve= 0 ,0
Exp/Cntr(USF)=0,0
Exp/Cntr=0.3,0.1

Type RM Length L Ch R = 1 ,16729   ,182.5,183.9,185.4
XS GIS Cut Line= 4
1972456.52729984223785.2490719211972246.15585746223885.425949247
1972049.14133205224065.7443284331971685.16534443224429.720316051
#Sta/Elev= 30
       0 1784.38    51.4 1785.08    68.6 1781.26     108 1767.54   142.4 1750.08
   196.6 1712.97   224.1  1687.1   253.2 1649.73   260.5 1646.14   270.6 1645.04
   279.9 1638.39   288.8  1634.3   307.8 1633.04   314.8 1631.27   337.7 1630.59
   358.9 1632.91   386.7 1637.93   435.6    1638   444.8 1640.36   459.7 1647.58
   479.6 1653.22   523.7 1658.56   684.3 1668.54   790.1  1676.7   837.4  1682.2
   874.5 1687.68   947.8 1702.02   961.7 1706.29   971.5  1706.8  1014.8 1718.45
#Mann= 10 ,-1 , 0
       0      .1       0   307.8    .045       0   358.9      .1       0
  383.01     .04       0  520.08     .05       0  530.08    .035       0
  660.08     .05       0  670.08    .035       0  800.08     .05       0
  810.08    .035       0
#XS Ineff= 2 , 0
                          391.98         1646.05
Permanent Ineff=
       F       F
Bank Sta=307.8,358.9
XS Rating Curve= 0 ,0
Exp/Cntr(USF)=0,0
Exp/Cntr=0.3,0.1

Type RM Length L Ch R = 1 ,16545   ,192,194.1,196.7
XS GIS Cut Line= 4
1972282.88737914223655.0191313971972162.67512635223725.142945525
1971855.46603589223978.9243680841971524.88234071224329.543438725
#Sta/Elev= 30
       0 1705.91    25.6 1711.49      37 1712.73    49.5 1712.17    67.4 1708.72
    83.1 1702.88   109.2 1688.04   160.9 1663.01   182.2 1648.57   189.5 1644.72
   210.5 1640.56   222.2 1640.08   233.2 1632.54   245.5  1629.9   268.8 1630.15
     280 1629.28   299.1 1630.05   306.1 1632.04     327 1630.73   339.6 1635.78
   365.1 1636.71   378.3 1640.73   399.2 1644.24   466.9 1649.07   533.3 1656.85
   702.5 1669.02   794.4 1678.15   881.1 1688.53   933.7 1696.49  1019.5 1714.56
#Mann= 6 ,-1 , 0
       0      .1       0  249.17     .04       0   268.8    .045       0
   299.1     .04       0  399.17     .05       0  847.65    .035       0
Bank Sta=268.8,299.1
XS Rating Curve= 0 ,0
Exp/Cntr(USF)=0,0
Exp/Cntr=0.3,0.1

Type RM Length L Ch R = 1 ,16351   ,163.8,163.2,162.3
XS GIS Cut Line= 3
1972190.86211649 223660.444802951971985.90268583223626.511122377
1971308.58642159224100.225303176
#Sta/Elev= 30
       0 1689.37    44.1 1672.02    88.8 1656.44   115.4 1641.28     132  1638.5
   138.7 1634.71     152 1636.13   165.3 1633.22   243.81629.884   252.7 1627.79
   260.7 1624.33   284.7 1624.02   291.11625.605   300.7 1630.73   308.6 1638.54
   310.9 1639.42   331.3 1639.79   339.2 1642.55   384.8 1643.12     601 1653.81
   769.1 1668.19   829.2 1672.18   855.2 1674.67   902.3 1682.12   928.2 1687.49
   938.1  1691.2   951.7 1693.41   965.3  1697.8  1005.4 1706.55  1034.3 1714.39
#Mann= 5 ,-1 , 0
       0      .1       0     152     .04       0   243.8    .045       0
   291.1     .05       0   829.2      .1       0
Bank Sta=243.8,291.1
XS Rating Curve= 0 ,0
Exp/Cntr(USF)=0,0
Exp/Cntr=0.3,0.1

Type RM Length L Ch R = 1 ,16187   ,475.1,477.9,475.1
XS GIS Cut Line= 4
1972186.04973106 223267.668539071972012.40981036223404.576938082
1971625.05921804223688.4114238391971190.95941629224085.779703899
#Sta/Elev= 30
       0 1717.93    30.2 1715.58    46.9 1711.97   109.6 1687.35   153.4 1675.08
   163.9 1670.61   193.1 1652.87     214    1643   233.5    1640     263 1638.34
   287.4 1630.21   372.8 1628.21   391.4 1627.04  397.271624.167   401.3 1621.99
   410.1 1621.39     446 1621.58  458.271624.169   468.8 1634.52   474.5 1636.99
   523.3 1639.73   729.1 1644.16   862.5 1656.87   942.9 1659.22    1006 1666.86
  1102.7 1681.97  1133.8 1688.88  1147.1    1690  1196.1 1704.34  1289.8  1738.9
#Mann= 9 ,-1 , 0
       0     .12       0      50      .1       0      70     .12       0
     190      .1       0  397.27    .045       0  458.27     .04       0
  561.12     .05       0  941.33    .035       0 1211.33     .08       0
#XS Ineff= 2 , 0
          359.03 1635.26
Permanent Ineff=
       F       F
Bank Sta=397.27,458.27
XS Rating Curve= 0 ,0
Exp/Cntr(USF)=0,0
Exp/Cntr=0.3,0.1

Type RM Length L Ch R = 1 ,15709   ,394.8,396.1,396.4
XS GIS Cut Line= 4
1971975.67828868222886.9964052311971721.89686612 223037.26172122
1971374.61702472223287.7039145351970883.75032582223678.393736106
#Sta/Elev= 30
       0 1891.15    32.1 1869.73      69 1837.76    95.7    1820     132 1799.27
   170.2 1769.88   184.6 1762.09   199.5  1751.6   232.5 1739.07   263.5 1724.34
   308.9 1698.06   368.9 1646.39  396.461618.072   403.1    1615   426.4 1614.67
   447.4 1615.05  462.161618.069     480  1625.6   504.3 1627.35   528.5 1626.52
   567.4 1631.18   670.1 1630.17   724.8 1635.05   806.6 1638.06     882  1645.1
  1020.4 1654.35  1066.5 1661.81  1154.5 1680.92  1189.5 1686.26  1350.5 1731.53
#Mann= 6 ,-1 , 0
       0     .12       0  396.46    .045       0  462.16     .04       0
  514.93     .05       0  1063.1    .035       0  1263.1      .1       0
Bank Sta=396.46,462.16
XS Rating Curve= 0 ,0
Exp/Cntr(USF)=0,0
Exp/Cntr=0.3,0.1

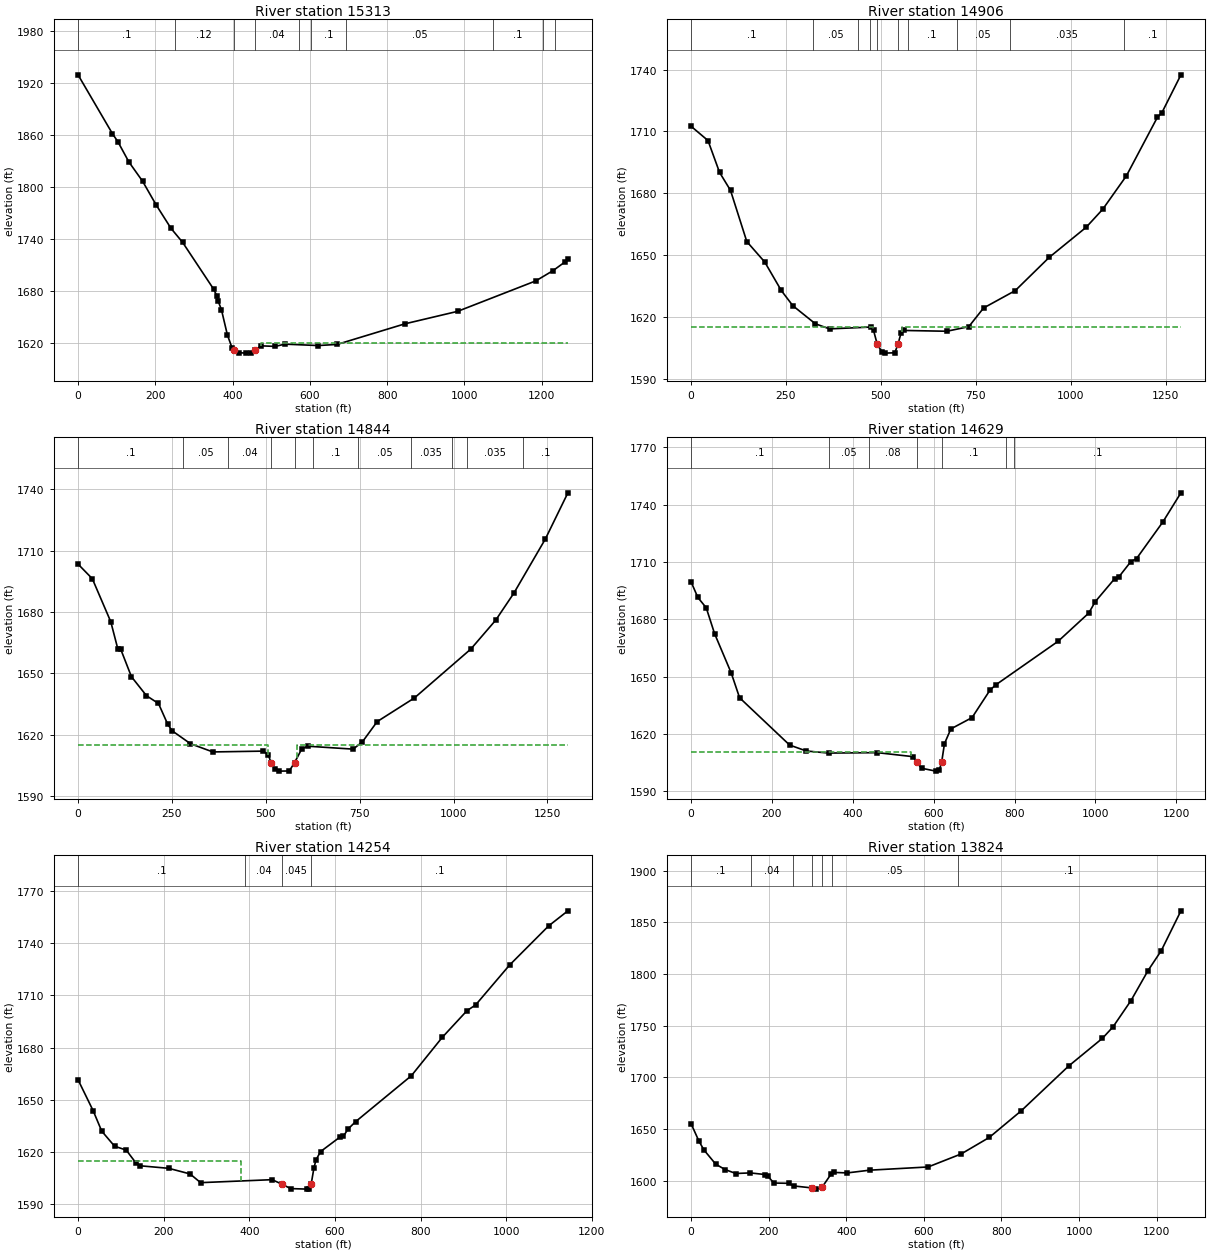
Type RM Length L Ch R = 1 ,15313   ,447.3,407.3,368.8
XS GIS Cut Line= 4
1971725.23609536222573.108856276 1971471.4546728222736.731089242
1971204.31633327222917.0494684291970703.43194664223321.096206977
#Sta/Elev= 30
       0  1929.3    88.9 1861.59   103.1 1852.27   131.5 1828.99     167 1806.74
   202.1 1779.45   240.7 1752.34   270.4 1736.42   351.1 1682.25     359 1674.75
     363 1668.14   371.1 1658.74   386.7 1629.33   398.6 1614.78  402.98 1611.88
   415.9 1609.16   434.2 1608.63   446.6 1608.88  457.211611.878   473.8 1617.02
   510.4 1616.38   535.3 1618.99   621.5 1617.37   670.6 1618.66     846  1642.4
   982.5 1656.78  1184.9  1691.9  1229.5 1703.74  1260.8 1713.87  1267.8 1717.63
#Mann= 10 ,-1 , 0
       0      .1       0     250     .12       0  402.98    .045       0
  457.21     .04       0  571.96     .05       0  601.96      .1       0
  694.26     .05       0 1074.26      .1       0 1204.26    .035       0
 1234.26      .1       0
#XS Ineff= 2 , 0
                          474.65         1619.96
Permanent Ineff=
       F       F
Bank Sta=402.98,457.21
XS Rating Curve= 0 ,0
Exp/Cntr(USF)=0,0
Exp/Cntr=0.5,0.3

Type RM Length L Ch R = 1 ,14906   ,66.9,62.1,63.6
XS GIS Cut Line= 4
1971391.90974931222205.2853208751971040.37748452222502.511586664
 1971055.0739217222651.067907692 1970549.8274014223107.385535348
#Sta/Elev= 30
       0 1712.52    44.6 1705.58      75 1690.14   103.9 1681.39   146.8 1656.55
   194.1 1646.61   237.6  1632.8   268.1 1625.41   327.3 1616.65   364.7 1614.16
   474.1 1615.05   480.7 1613.44  490.271606.788   503.8 1602.72   510.4 1602.39
   536.7 1602.56   545.21606.788   553.2 1612.21   559.8  1613.4   673.7 1613.01
   731.5 1615.23   770.6 1624.31   853.9 1632.73   943.4 1648.87  1040.7 1663.47
  1084.4 1672.22  1146.8 1688.46  1228.4 1716.87  1240.1 1719.05  1290.4 1737.49
#Mann= 10 ,-1 , 0
       0      .1       0     320     .05       0     440     .04       0
  470.35     .06       0  490.27    .045       0   545.2     .06       0
  570.35      .1       0  699.63     .05       0  839.63    .035       0
 1139.63      .1       0
#XS Ineff= 2 , 0
             480 1615.16     555         1615.16
Permanent Ineff=
       F       F
Bank Sta=490.27,545.2
XS Rating Curve= 0 ,0
Exp/Cntr(USF)=0,0
Exp/Cntr=0.5,0.3

Type RM Length L Ch R = 1 ,14844   ,165,215.5,248.2
XS GIS Cut Line= 4
 1971379.4909273222195.7438368121970982.32937851222476.473661201
1970997.85360843222665.3517918951970529.53933917223084.505999739
#Sta/Elev= 30
       0 1703.47      38 1696.34    87.2 1675.29     106 1661.97   113.1 1662.13
   142.2 1648.43   182.3 1639.14   214.2 1635.34   238.6 1625.28   250.6    1622
   299.4 1615.67   359.1 1611.66   493.3 1612.06   506.5 1610.29  513.911606.456
   523.8 1603.23   536.1 1602.28   562.4 1602.36   576.71606.455   595.5 1613.06
   611.8 1614.46   732.6 1613.03   757.2 1616.58   796.6 1626.49   895.7 1638.05
    1046 1661.96  1112.1 1676.05  1160.6 1689.29  1244.3 1715.71  1304.4 1738.31
#Mann= 11 ,-1 , 0
       0      .1       0     280     .05       0     400     .04       0
  513.91    .045       0   576.7     .06       0  626.36      .1       0
  745.88     .05       0  885.88    .035       0  995.88     .05       0
 1035.88    .035       0 1185.88      .1       0
#XS Ineff= 2 , 0
             507 1615.16     583         1615.16
Permanent Ineff=
       F       F
Bank Sta=513.91,576.7
XS Rating Curve= 0 ,0
Exp/Cntr(USF)=0,0
Exp/Cntr=0.5,0.3

Type RM Length L Ch R = 1 ,14629   ,317,374.3,407.3
XS GIS Cut Line= 4
1971374.61702472222185.7582639491970937.17799373222322.666662961
1970676.71811268222509.6635006361970339.45595902222780.141069416
#Sta/Elev= 30
       0 1699.59    16.8 1691.39    37.5 1686.02    58.1 1672.51    99.4 1651.86
     120 1638.95   243.7 1614.22     285 1611.11     340 1610.03   460.7 1610.24
     549 1608.15   557.51605.298   570.2 1602.08   605.4 1600.58   614.1 1601.42
  619.681605.304   626.6 1614.94   642.4 1622.66   694.8 1628.57   739.3 1642.98
   753.5  1645.7   907.8 1668.52   983.5 1683.26   999.2 1689.14  1047.8 1701.32
  1057.3 1702.02  1087.5 1710.16  1101.5 1711.72  1166.7 1730.91  1211.3 1746.13
#Mann= 7 ,-1 , 0
       0      .1       0     340     .05       0     440     .08       0
   557.5    .045       0  619.68      .1       0     779     .05       0
     799      .1       0
#XS Ineff= 2 , 0
          543.11 1610.49
Permanent Ineff=
       F       F
Bank Sta=557.5,619.68
XS Rating Curve= 0 ,0
Exp/Cntr(USF)=0,0
Exp/Cntr=0.3,0.1

Type RM Length L Ch R = 1 ,14254   ,397,430.4,453.3
XS GIS Cut Line= 4
1971324.52858606222149.0267422621971107.47868518222185.758263949
1970710.11040513222002.1006555181970242.61831094 221868.53148575
#Sta/Elev= 30
       0 1661.53    35.4  1643.7    55.3 1632.03    85.3 1623.37   112.6 1621.11
   135.2 1613.76   145.2 1612.11   211.7 1610.66   261.6 1607.44   286.3 1602.43
   453.2 1604.14  475.421601.655   496.5 1599.02   535.9 1598.71   539.9 1598.98
  544.571601.657   550.8 1610.66   555.7 1615.48   566.4 1620.26   612.2  1628.7
     620 1629.07   630.3 1633.16   648.3 1637.46   778.5 1663.84   850.7 1685.88
   908.2 1701.15   928.7 1704.53  1007.8 1727.38  1099.3 1749.93  1144.1 1758.55
#Mann= 4 ,-1 , 0
       0      .1       0  390.14     .04       0  475.42    .045       0
  544.57      .1       0
#XS Ineff= 2 , 0
          381.66 1615.13
Permanent Ineff=
       F       F
Bank Sta=475.42,544.57
XS Rating Curve= 0 ,0
Exp/Cntr(USF)=0,0
Exp/Cntr=0.3,0.1

Type RM Length L Ch R = 1 ,13824   ,422.6,416.3,407.5
XS GIS Cut Line= 4
1971337.88550303 222115.634449821971221.01247949222015.457572494
1971120.83560216221761.6761499351970412.91900239221317.558660457
#Sta/Elev= 30
       0 1655.29    20.3 1638.39    33.3 1629.82    63.5 1616.15    87.5 1610.94
   115.4  1607.1   152.7 1607.68   190.6 1606.09   197.6 1604.73   213.2 1597.87
   251.2 1597.62   264.6 1595.07   310.4 1593.21     321 1591.99   337.2 1593.58
   360.2 1606.19   367.5 1608.13   402.9 1607.68   459.9  1610.3   610.9 1613.42
   696.1    1626   768.5 1641.95   851.1 1667.77   973.1    1711  1060.2 1737.81
  1087.4 1748.82  1133.8  1774.3  1177.8 1803.34  1211.8 1822.53  1262.5 1861.07
#Mann= 7 ,-1 , 0
       0      .1       0  153.93     .04       0  263.93      .1       0
   310.4    .045       0   337.2      .1       0  363.93     .05       0
  686.77      .1       0
Bank Sta=310.4,337.2
XS Rating Curve= 0 ,0
Exp/Cntr(USF)=0,0
Exp/Cntr=0.3,0.1