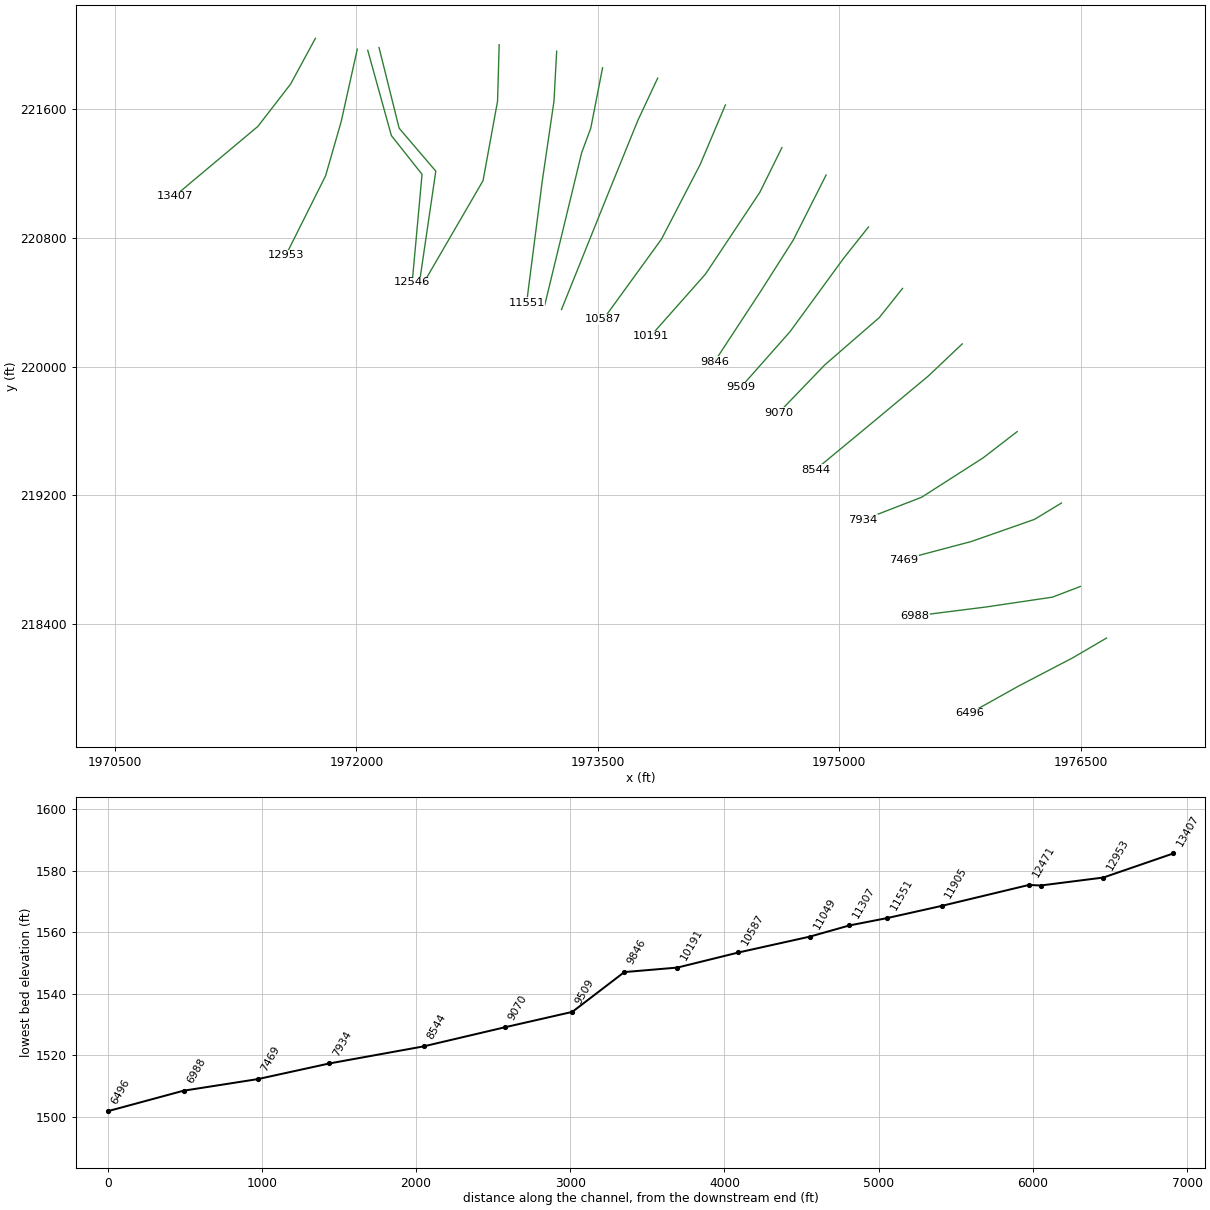
HEC-RAS study LTBLUESTRV.prj: LTBLUESTRV

--- LTBLUESTRV.g01 (geometry) --- (continued)

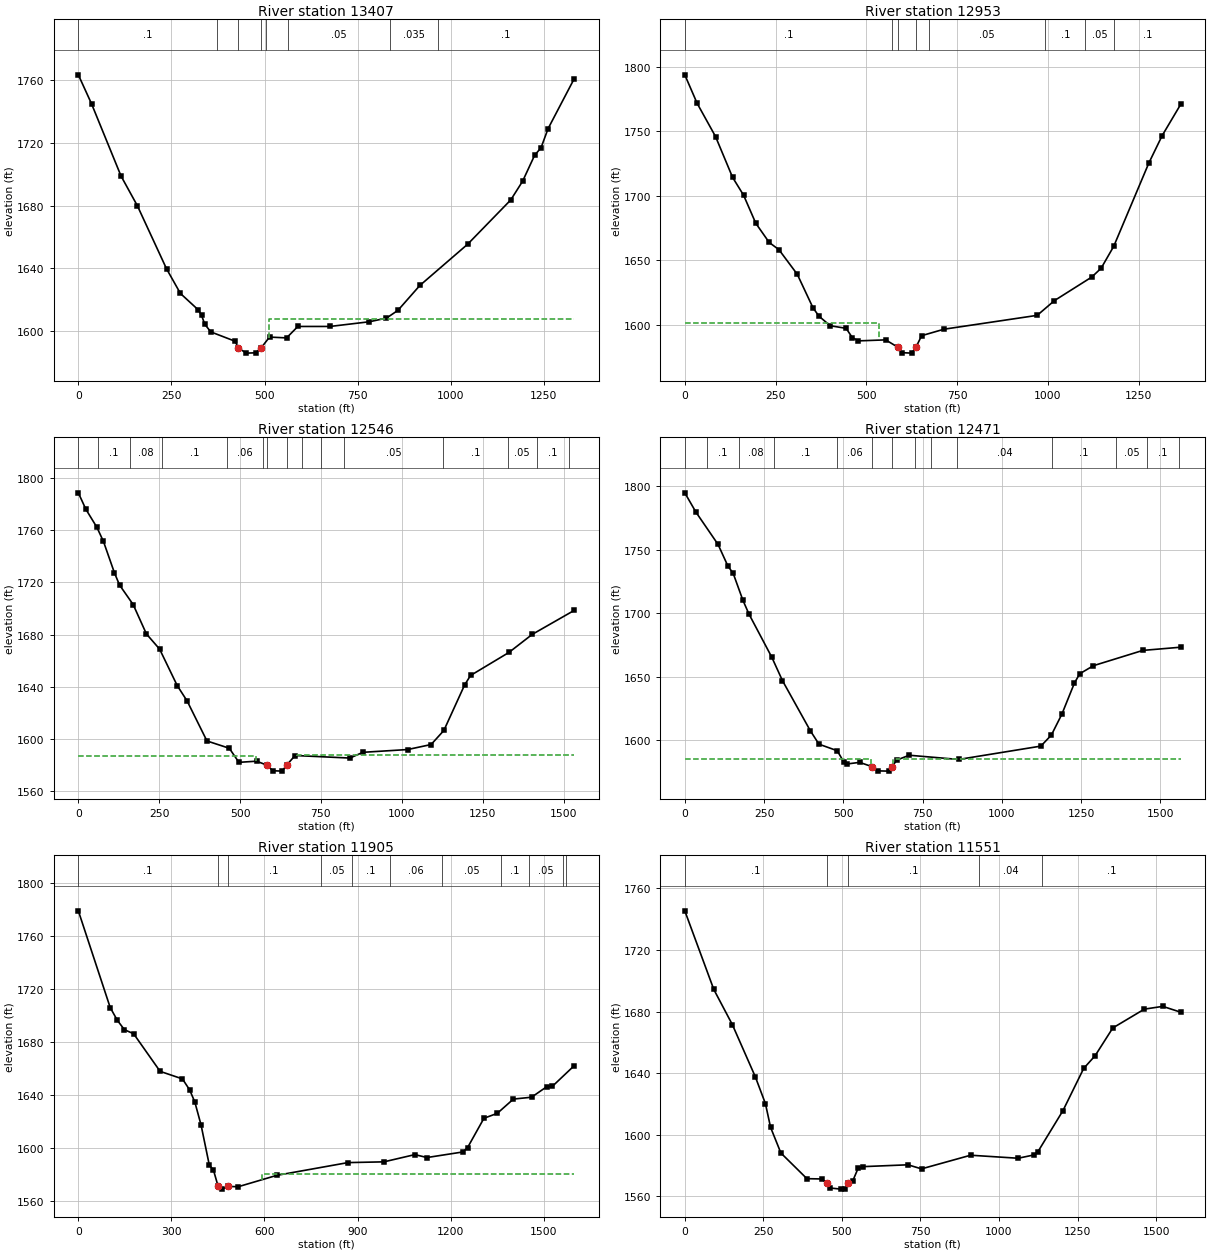
Type RM Length L Ch R = 1 ,13407   ,441.4,454.5,467.4
XS GIS Cut Line= 4
1971745.27147083222042.1714064481971591.66692559221758.336920691
 1971387.9739417221494.5378103991970870.39340885221060.438008653
#Sta/Elev= 30
       0 1763.61    35.5 1745.07   114.7 1698.88   158.6 1679.86   236.9 1639.55
   274.2 1623.79   322.3 1613.26     331 1609.78   339.3 1604.22   355.6 1599.24
   421.1 1593.24  429.99 1588.83   451.2 1585.65   476.1 1585.86  490.281588.829
   513.4 1595.91   559.2 1595.39   589.5  1602.7     676 1602.71   781.6 1605.71
   827.5 1608.04   858.2 1612.99   917.1 1628.91  1045.6 1655.32  1161.2  1683.6
    1193 1695.55  1225.4 1712.19  1242.5 1716.96  1261.5 1729.22  1331.5 1761.06
#Mann= 8 ,-1 , 0
       0      .1       0  372.73     .04       0  429.99    .045       0
  490.28     .04       0  502.73      .1       0  562.73     .05       0
  836.02    .035       0  966.02      .1       0
#XS Ineff= 2 , 0
                          511.46         1607.57
Permanent Ineff=
       F       F
Bank Sta=429.99,490.28
XS Rating Curve= 0 ,0
Exp/Cntr(USF)=0,0
Exp/Cntr=0.3,0.1

Type RM Length L Ch R = 1 ,12953   ,367.2,407.2,438.6
XS GIS Cut Line= 4
1972005.73135188221975.3868215641971905.55447455221524.590873597
1971808.71682647221187.328719933 1971561.6138624220693.122791791
#Sta/Elev= 30
       0 1793.65    34.1 1771.47    84.6  1745.8   131.6 1714.11   161.9 1700.27
   195.5  1678.5   232.4 1663.65   259.3 1658.01   309.7 1638.95   353.1 1612.88
   369.6 1606.41   400.5 1599.04   444.2 1597.05     461 1589.93     478 1587.31
   553.1 1588.09  587.361582.268   597.5 1578.17   624.7 1577.81   636.31582.262
   652.1 1591.34   713.5 1596.35   970.3 1607.11  1017.9 1618.57  1120.6 1636.83
  1146.3 1643.64  1181.1  1660.7  1277.7 1725.25  1314.4 1746.53  1365.2 1770.66
#Mann= 8 ,-1 , 0
       0      .1       0  571.79     .06       0  587.36    .045       0
   636.3     .06       0  671.79     .05       0  992.68      .1       0
 1102.68     .05       0 1182.68      .1       0
#XS Ineff= 2 , 0
          535.53 1600.99
Permanent Ineff=
       F       F
Bank Sta=587.36,636.3
XS Rating Curve= 0 ,0
Exp/Cntr(USF)=0,0
Exp/Cntr=0.5,0.3

Type RM Length L Ch R = 1 ,12546   ,77,74.9,80.3
XS GIS Cut Line= 4
 1972070.6306403221967.6655047331972217.41881688221437.475374408
 1972408.0243596221196.479860624  1972346.680047220523.883290337
#Sta/Elev= 30
       0 1788.73    23.2 1776.16    57.2 1762.34    77.6 1751.47   111.7  1727.3
   127.3 1718.03   169.5 1703.02   210.4  1680.5   251.3 1668.81   305.7 1640.84
   336.4 1629.01   397.6 1598.37   466.7 1592.76   496.4 1581.97     551 1582.84
  583.551579.769   601.2 1575.52     630 1575.22  643.921579.771     670  1587.2
   839.6 1585.25   879.6 1589.65    1018 1591.78  1090.5 1595.62    1130 1606.41
    1194 1641.25  1212.4 1648.59    1331 1666.25  1403.4 1680.16  1532.8 1698.51
#Mann= 15 ,-1 , 0
       0     .08       0      60      .1       0     160     .08       0
     260      .1       0     460     .06       0  570.13     .05       0
  583.55    .045       0  643.92     .04       0  690.13     .05       0
  750.13     .04       0  820.13     .05       0  1127.4      .1       0
  1327.4     .05       0  1417.4      .1       0  1517.4     .12       0
#XS Ineff= 2 , 0
          549.84 1587.04  675.12         1587.44
Permanent Ineff=
       F       F
Bank Sta=583.55,643.92
XS Rating Curve= 0 ,0
Exp/Cntr(USF)=0,0
Exp/Cntr=0.5,0.3

Type RM Length L Ch R = 1 ,12471   ,587.5,566.1,524.2
XS GIS Cut Line= 4
1972140.73842613 221985.192451191972265.61791964221483.483608858
1972493.46822358221216.1976753881972392.68828145220528.265026951
#Sta/Elev= 30
       0 1794.99    35.1 1779.76   104.9 1754.25   135.7 1737.33   152.6 1731.43
   183.1 1710.31   202.3 1699.35   274.4 1665.24   307.9 1646.84   396.1 1607.16
   423.1 1596.68   480.6 1591.51   500.9 1582.85     511 1581.03   551.3 1582.33
  591.431578.853   608.5 1575.61     643 1575.41  653.051578.852   668.9 1584.19
   707.7 1587.94   863.5 1584.62  1122.8 1595.15  1155.9 1603.85  1189.1 1620.38
  1228.7 1644.96  1245.4 1652.25  1288.5  1658.6  1444.4 1670.66  1563.5 1673.18
#Mann= 14 ,-1 , 0
       0     .08       0      70      .1       0     170     .08       0
     280      .1       0     480     .06       0  591.43    .045       0
  653.05     .06       0  727.02     .04       0  777.02     .05       0
  857.02     .04       0 1158.24      .1       0 1358.24     .05       0
 1458.24      .1       0 1558.24     .12       0
#XS Ineff= 2 , 0
             586 1585.08     658         1585.08
Permanent Ineff=
       F       F
Bank Sta=591.43,653.05
XS Rating Curve= 0 ,0
Exp/Cntr(USF)=0,0
Exp/Cntr=0.5,0.3

Type RM Length L Ch R = 1 ,11905   ,351.7,353.6,356.5
XS GIS Cut Line= 4
1972887.28787234222002.1006555181972877.27018461221651.481584877
1972787.11099502221157.2756567351972413.11731967220512.804412604
#Sta/Elev= 30
       0 1779.06   102.7 1705.94   125.7 1696.26   148.7 1689.14   178.2 1686.12
   263.6 1657.67   335.6 1651.95   358.9 1643.61   375.5 1634.48   395.6 1617.12
   422.2 1586.78   435.6 1582.99   450.4 1570.89   462.3  1568.6   482.3 1570.65
   515.3 1570.41   639.4    1579     869 1588.66   985.1 1589.23  1084.7  1594.7
  1123.9 1592.49  1239.3  1596.7  1254.5 1599.91  1307.5 1622.19  1350.5 1625.91
  1402.4 1636.69    1461 1638.11  1509.6 1646.01  1528.2 1646.37  1598.3 1661.92
#Mann= 11 ,-1 , 0
       0      .1       0   450.4    .045       0   482.3      .1       0
  780.76     .05       0  883.12      .1       0 1003.12     .06       0
 1173.12     .05       0 1363.12      .1       0 1453.12     .05       0
 1563.12      .1       0 1573.12     .12       0
#XS Ineff= 2 , 0
                          593.41         1580.19
Permanent Ineff=
       F       F
Bank Sta=450.4,482.3
XS Rating Curve= 0 ,0
Exp/Cntr(USF)=0,0
Exp/Cntr=0.3,0.1

Type RM Length L Ch R = 1 ,11551   ,251.7,244.6,233.2
XS GIS Cut Line= 4
1973244.58540147221962.0299045871973227.88925525221651.481584877
1973154.42621188221150.597198247 1973057.5885638220395.931389057
#Sta/Elev= 30
       0 1745.49    92.3 1694.39   151.4 1671.52   224.4 1637.67   256.6 1620.21
     273 1604.79   305.8 1588.12   388.7 1571.43   435.1 1571.25  453.041568.362
   461.6  1565.4   496.7 1564.64   511.4 1564.81  520.391568.364   534.6 1570.01
   551.6 1578.17   567.8 1579.26   710.3 1580.45   753.4 1577.81   909.7 1586.67
    1061 1584.71  1110.8 1586.84  1124.1 1589.03  1203.5 1615.62  1269.6 1643.09
    1306 1651.35  1362.2 1669.37  1462.6  1681.6  1521.3  1683.4  1578.1 1679.63
#Mann= 5 ,-1 , 0
       0      .1       0  453.04    .045       0  520.39      .1       0
  937.24     .04       0 1137.24      .1       0
Bank Sta=453.04,520.39
XS Rating Curve= 0 ,0
Exp/Cntr(USF)=0,0
Exp/Cntr=0.3,0.1

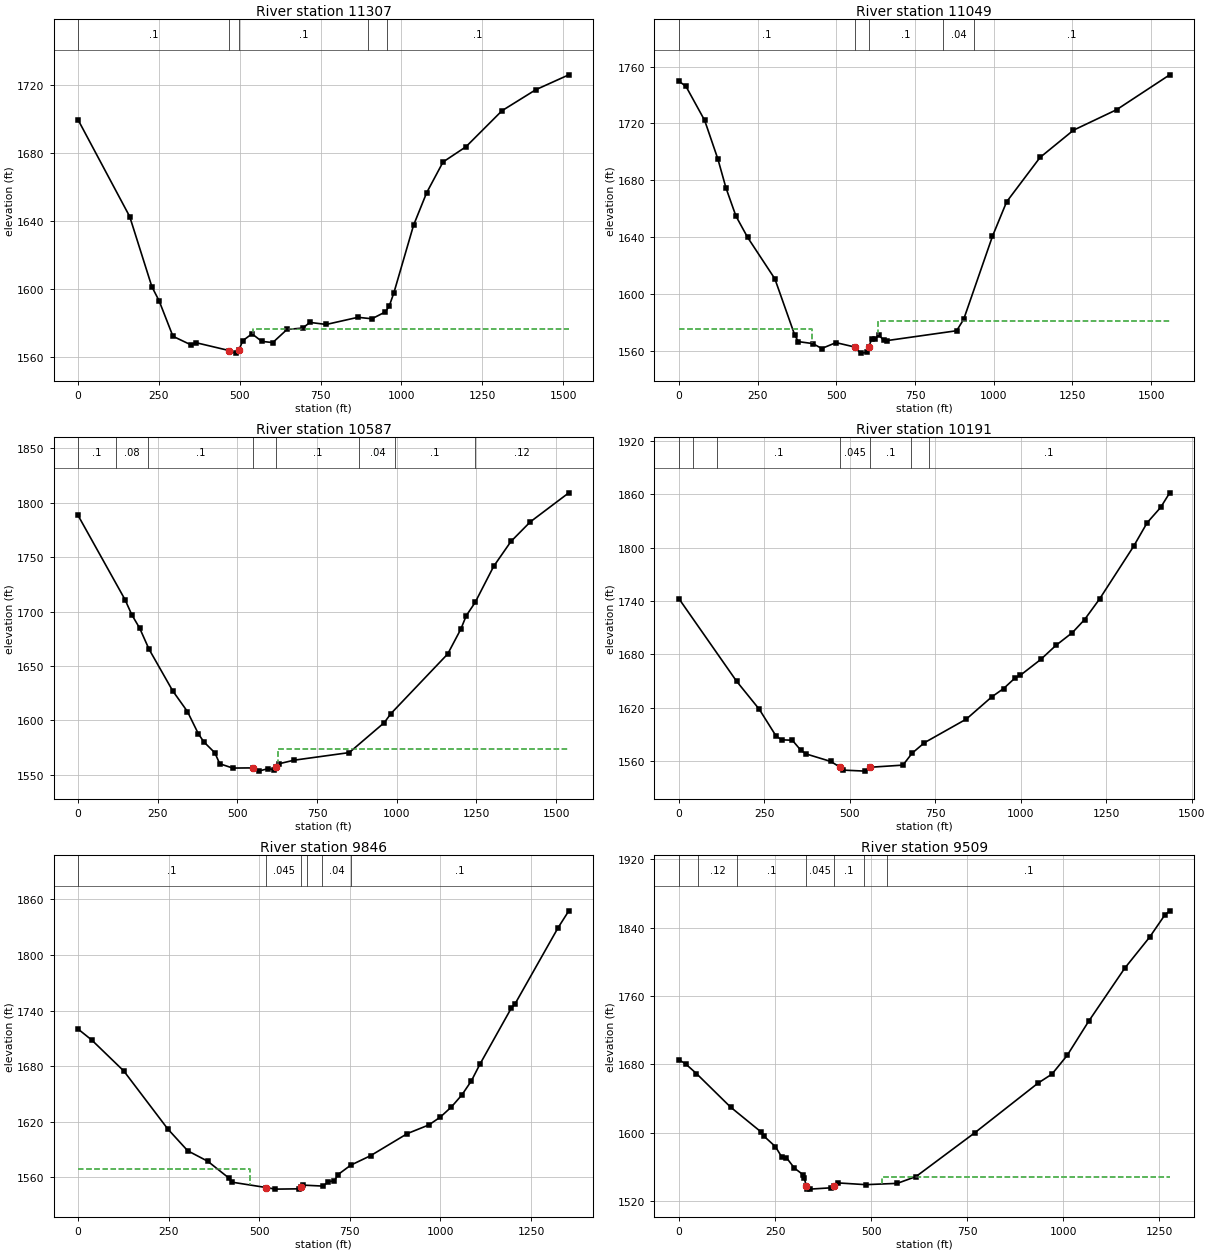
Type RM Length L Ch R = 1 ,11307   ,257.7,257.2,252.7
XS GIS Cut Line= 4
1973529.78290009221859.3142141321973456.42586399221483.359404144
1973399.83136913221330.7744766581973171.21600006220386.232030784
#Sta/Elev= 30
       0 1699.57   159.7 1642.61   228.3 1601.29   250.5 1593.09   293.4 1572.16
   350.2 1567.02   363.6 1568.44   467.7 1563.74   488.7 1562.25     497 1564.04
   509.7 1569.63   537.8  1573.6   568.3 1569.15   602.1 1568.47     646 1576.16
   694.9 1577.02   716.9 1580.33   767.5 1579.13   865.4 1583.33   908.7 1582.47
   949.8 1586.47   962.2  1589.9   976.8 1597.88  1037.5 1637.55    1078 1656.68
  1128.7 1674.76  1199.6 1683.73    1311 1704.94  1415.6 1717.31  1517.6 1726.06
#Mann= 5 ,-1 , 0
       0      .1       0   467.7    .045       0     497      .1       0
  895.79     .04       0  955.79      .1       0
#XS Ineff= 2 , 0
                          539.46         1576.52
Permanent Ineff=
       F       F
Bank Sta=467.7,497
XS Rating Curve= 0 ,0
Exp/Cntr(USF)=0,0
Exp/Cntr=0.3,0.1

Type RM Length L Ch R = 1 ,11049   ,463.3,462.6,453.9
XS GIS Cut Line= 4
1973872.36049938221795.0684423771973748.80901735221531.269332085
1973561.81217967221070.4556963861973274.63846467220355.860638127
#Sta/Elev= 30
       0 1749.73    22.5 1745.99    81.7 1722.14   123.9 1694.83   149.3 1674.75
   181.1 1654.87   218.1 1639.95   304.7 1610.81   367.7 1571.32   379.1  1566.7
   425.7 1565.29   453.4 1561.85   498.7 1565.99   557.9 1562.93   576.8 1558.61
   598.6 1559.09   602.5 1562.84   612.8 1568.79   623.4 1568.86     634 1571.58
   649.8 1567.74   662.4 1567.47   881.9 1574.34   904.4 1582.37   995.9 1640.79
  1040.8 1664.94  1146.9 1696.11    1253 1715.26  1390.3 1729.69  1558.7 1754.18
#Mann= 5 ,-1 , 0
       0      .1       0   557.9    .045       0   602.5      .1       0
  838.61     .04       0  938.61      .1       0
#XS Ineff= 2 , 0
          421.78 1575.77  632.66         1581.25
Permanent Ineff=
       F       F
Bank Sta=557.9,602.5
XS Rating Curve= 0 ,0
Exp/Cntr(USF)=0,0
Exp/Cntr=0.3,0.1

Type RM Length L Ch R = 1 ,10587   ,397.2,395.8,387.3
XS GIS Cut Line= 4
1974293.10338415221628.1069801671974136.15960967221257.452534061
1973895.73510409220793.2996691171973535.09834572220295.754511731
#Sta/Elev= 30
       0 1788.46   147.2 1711.14   168.5 1697.23   193.5 1684.71   222.6 1665.53
   296.8 1627.29   343.1 1608.23   377.4 1587.78   394.5 1580.36   429.2 1570.27
   444.4 1560.24   485.4 1556.27   550.31556.441   566.3 1553.46   597.1  1555.8
   614.3 1554.64  621.541557.166   629.1 1560.14   677.4  1563.5   850.8 1570.49
   960.7 1598.03   981.4 1606.28  1159.7 1661.14  1201.1  1684.1  1217.8 1696.25
  1245.8 1708.52  1303.9 1741.68  1358.2 1764.58    1419  1782.6  1539.7 1809.25
#Mann= 8 ,-1 , 0
       0      .1       0     120     .08       0     220      .1       0
   550.3    .045       0  621.54      .1       0  882.51     .04       0
  995.24      .1       0 1245.24     .12       0
#XS Ineff= 2 , 0
                          625.79         1573.68
Permanent Ineff=
       F       F
Bank Sta=550.3,621.54
XS Rating Curve= 0 ,0
Exp/Cntr(USF)=0,0
Exp/Cntr=0.3,0.1

Type RM Length L Ch R = 1 ,10191   ,343.7,344.5,348
XS GIS Cut Line= 4
1974644.16768536  221362.67535781974506.88826088221084.406254117
1974169.25508174220576.1013580551973827.91164789220190.234867614
#Sta/Elev= 30
       0 1742.48   168.7 1649.63   234.9 1618.19   283.8 1588.22   300.1 1583.77
   331.8 1583.29   355.7 1572.41   371.7 1567.93   444.4 1559.39  471.891552.863
   481.2 1549.69   545.2 1548.56  557.571552.862   655.3 1555.32   682.3 1568.79
   718.3 1580.56   840.9 1607.13   915.2 1632.07   949.7  1641.4   984.1 1653.63
   998.1 1656.16  1058.5 1674.18  1102.6 1689.89  1151.2 1704.42  1186.5 1718.92
  1230.5 1742.14  1330.1 1801.38  1369.9 1828.05  1409.3 1845.18  1435.7 1861.59
#Mann= 7 ,-1 , 0
       0      .1       0      40     .08       0     110      .1       0
  471.89    .045       0  557.57      .1       0  680.29     .04       0
  730.29      .1       0
Bank Sta=471.89,557.57
XS Rating Curve= 0 ,0
Exp/Cntr(USF)=0,0
Exp/Cntr=0.3,0.1

Type RM Length L Ch R = 1 ,9846    ,327,337.3,326
XS GIS Cut Line= 4
1974918.72653433221192.0036408751974714.66252496220787.585876855
1974514.30877031220472.2142260141974224.90890248220030.693914836
#Sta/Elev= 30
       0 1719.97    37.9 1708.07   126.4 1674.59   247.6 1612.06   302.7 1588.48
   357.9  1577.2   416.2 1559.07   423.8 1554.65   519.7 1548.78   544.4 1547.09
   608.9 1547.41  616.331549.393   621.9  1551.4   676.6 1550.36   690.5 1555.13
   707.5 1556.08   717.7 1562.86   752.6 1572.97   807.3 1583.19   909.2 1607.15
   967.8 1616.35   999.5 1624.76  1030.6 1635.91  1059.3 1648.79  1085.5 1663.96
    1109 1681.91  1195.3 1742.26  1205.5 1746.75  1324.8 1829.35  1354.5 1847.66
#Mann= 6 ,-1 , 0
       0      .1       0   519.7    .045       0  616.33      .1       0
  632.99     .06       0  672.99     .04       0  752.99      .1       0
#XS Ineff= 2 , 0
          473.35 1568.31
Permanent Ineff=
       F       F
Bank Sta=519.7,616.33
XS Rating Curve= 0 ,0
Exp/Cntr(USF)=0,0
Exp/Cntr=0.3,0.1

Type RM Length L Ch R = 1 ,9509    ,430.4,438.9,406.1
XS GIS Cut Line= 4
1975182.15461915220869.2114806021975026.32392108220672.567980666
1974696.11125138220219.9169053411974388.16010997219871.152962058
#Sta/Elev= 30
       0 1685.51    17.4 1680.65    45.4 1669.38   134.1 1630.19   213.5 1601.09
   221.8 1595.86   250.9 1583.86   267.4 1571.81   279.6 1570.93   300.2 1558.82
     323 1550.94     326 1547.42  330.821538.008   333.1 1534.85   340.5 1534.16
   396.5 1535.73  403.111538.016   413.6 1541.43   485.7 1539.39   567.9 1540.91
   616.6 1548.86   769.8  1600.2   934.1 1658.19   970.2 1668.68  1009.7 1690.48
  1065.4 1730.28  1159.6 1792.62  1224.1 1828.78  1263.7 1854.75  1276.5 1859.72
#Mann= 7 ,-1 , 0
       0      .1       0      50     .12       0     150      .1       0
  330.82    .045       0  403.11      .1       0   480.9     .04       0
   540.9      .1       0
#XS Ineff= 2 , 0
                          529.25         1548.08
Permanent Ineff=
       F       F
Bank Sta=330.82,403.11
XS Rating Curve= 0 ,0
Exp/Cntr(USF)=0,0
Exp/Cntr=0.3,0.1

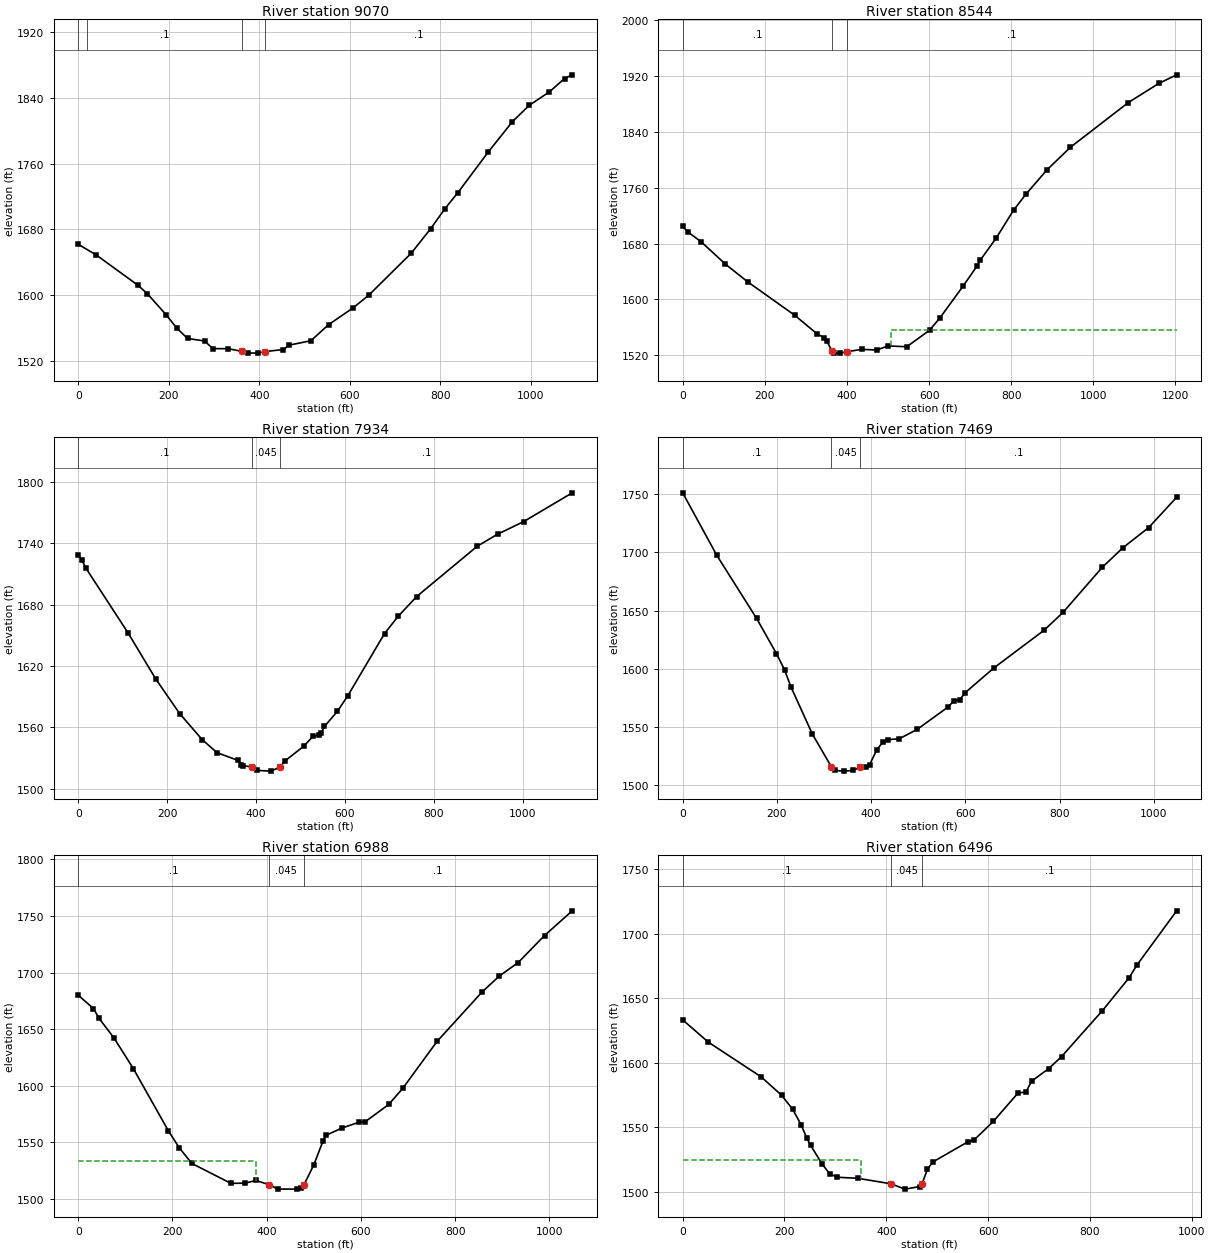
Type RM Length L Ch R = 1 ,9070    ,524.4,525.8,518.6
XS GIS Cut Line= 4
1975393.63913795220487.0552448771975248.93920403220305.252763804
1974911.30602489220012.1426412571974625.61641178219715.322263995
#Sta/Elev= 30
       0 1661.81    39.9 1648.73   131.2 1612.15   152.3 1601.79   194.8 1575.49
     218 1559.44   241.4 1547.05   279.3  1543.9   297.2 1534.65   331.4 1534.52
   362.4 1531.22   374.8 1529.32   396.6 1529.14   413.5 1531.09   453.1 1533.53
   466.1 1538.91   513.9 1544.23     553 1563.79   606.6 1584.05   641.4 1599.51
   735.7 1650.94   778.6  1680.8   810.4 1705.39   838.8 1724.79     906 1774.41
   959.4 1811.38   996.5 1831.19  1040.6 1847.44  1074.5 1863.88  1091.4 1868.36
#Mann= 4 ,-1 , 0
       0     .12       0      20      .1       0   362.4    .045       0
   413.5      .1       0
Bank Sta=362.4,413.5
XS Rating Curve= 0 ,0
Exp/Cntr(USF)=0,0
Exp/Cntr=0.3,0.1

Type RM Length L Ch R = 1 ,8544    ,610.8,610.3,606.9
XS GIS Cut Line= 4
1975764.66460952220142.0015563091975553.18009072219941.647801657
1975196.99563801219644.8274243951974851.94194944 219359.13781128
#Sta/Elev= 30
       0 1704.65    13.5 1696.26    45.1 1682.57   103.9  1650.6   158.1 1625.25
   272.3 1577.45   328.1 1550.14   344.8 1545.11   351.4 1539.75  364.06 1525.43
   369.6 1522.98     384 1522.95   400.3 1525.12   436.2 1528.29   472.1 1527.43
   500.5 1533.28   545.6  1532.1   601.1 1555.73   626.3 1573.41   682.3 1618.63
   716.4 1647.52   724.9 1656.51   763.7 1688.21   805.9 1728.08   835.7 1750.77
   887.2 1785.86   944.3 1818.21  1085.3 1882.33  1159.5 1909.76  1202.9 1922.02
#Mann= 3 ,-1 , 0
       0      .1       0  364.06    .045       0   400.3      .1       0
#XS Ineff= 2 , 0
                          507.45         1555.92
Permanent Ineff=
       F       F
Bank Sta=364.06,400.3
XS Rating Curve= 0 ,0
Exp/Cntr(USF)=0,0
Exp/Cntr=0.3,0.1

Type RM Length L Ch R = 1 ,7934    ,476.7,464.6,459.1
XS GIS Cut Line= 4
1976106.00804338 219596.594113091975894.52352458219433.342905596
1975512.36728885219188.466094354 1975148.7623267219047.476415155
#Sta/Elev= 30
       0 1728.77     8.4 1723.36    16.7 1715.93   112.6 1651.95   174.2 1607.44
   228.1 1573.58   278.8 1548.14   311.8 1535.53     359  1527.9   366.8 1523.42
   370.7 1522.71  390.511521.536     403  1518.1   433.2 1517.41  454.681521.536
   464.2 1527.13   507.1  1541.7   528.2 1551.45   542.2 1552.59     546 1554.39
   553.8 1561.08   582.8 1575.74   606.6 1591.22   688.8 1651.69   719.2 1668.37
   761.1 1687.82   897.3 1736.92     943 1748.69    1002 1761.05    1111 1789.09
#Mann= 3 ,-1 , 0
       0      .1       0  390.51    .045       0  454.68      .1       0
Bank Sta=390.51,454.68
XS Rating Curve= 0 ,0
Exp/Cntr(USF)=0,0
Exp/Cntr=0.3,0.1

Type RM Length L Ch R = 1 ,7469    ,488.9,481.6,477.5
XS GIS Cut Line= 4
1976381.16442952219152.4749686691976213.21051235219050.684715836
1975821.31803894218913.2678745111975398.88848968218801.298596394
#Sta/Elev= 30
       0 1751.07    72.5 1697.39   156.8  1643.4   198.9 1613.23   216.2 1599.26
   230.1 1584.28   275.3  1544.1   315.9 1515.89     324 1512.86   341.4 1512.32
   362.3 1512.91   376.2 1515.79   390.1 1515.69     397 1517.93   411.6 1530.37
   424.8 1537.14   435.3 1539.42   459.6 1540.04   497.8 1548.12   563.9  1567.5
   575.8 1572.75   588.2 1573.51     599 1579.36   660.6 1600.85   767.5 1633.26
   807.8 1648.68   891.1 1687.31     935 1704.11   989.3 1721.28  1048.7  1747.3
#Mann= 3 ,-1 , 0
       0      .1       0   315.9    .045       0   376.2      .1       0
Bank Sta=315.9,376.2
XS Rating Curve= 0 ,0
Exp/Cntr(USF)=0,0
Exp/Cntr=0.3,0.1

Type RM Length L Ch R = 1 ,6988    ,476.3,492.2,504.9
XS GIS Cut Line= 4
1976498.22322028218633.3446792191976325.17979046218567.181014877
1975912.92926649218506.1068631771975470.14166666218450.122224119
#Sta/Elev= 30
       0 1679.98    32.2  1668.2    44.2 1659.47    75.8 1642.24   117.1 1614.95
   191.3 1560.08   214.6    1545   241.1 1531.24     324 1513.66   353.9 1513.82
   377.1 1516.21  404.361512.571   423.5 1508.62   463.3 1508.55   473.3 1509.84
   479.21512.567   499.8 1529.86   519.7 1551.39   526.3 1556.23   559.5 1562.53
   595.9 1567.68   609.2  1568.2   658.8 1583.36   688.6 1597.59   761.3 1639.06
   857.2 1682.94   893.6 1696.92   933.5 1708.79   989.5 1732.73  1048.3 1754.56
#Mann= 3 ,-1 , 0
       0      .1       0  404.36    .045       0   479.2      .1       0
#XS Ineff= 2 , 0
          378.22 1533.55
Permanent Ineff=
       F       F
Bank Sta=404.36,479.2
XS Rating Curve= 0 ,0
Exp/Cntr(USF)=0,0
Exp/Cntr=0.3,0.1

Type RM Length L Ch R = 1 ,6496    ,432.8,431.3,428.1
XS GIS Cut Line= 4
1976661.08762481218312.7053827941976452.41760651218190.557079394
1976111.42025951218012.4241369351975811.13901366 217844.47021976
#Sta/Elev= 30
       0 1633.15    50.3 1615.89   154.4 1588.88   194.2 1574.74   215.8 1563.98
   232.6 1551.88   244.1 1541.24   251.5 1535.72   273.7 1521.49   288.5 1513.95
   303.3  1511.1     344 1510.28  409.121506.028   436.7 1501.88   465.3 1503.83
  470.281506.025     481 1517.45   492.1 1523.07   560.1 1538.54   572.8 1540.11
   610.5 1554.47   659.1 1576.55   674.2 1577.03   685.5  1585.6   719.3  1595.4
   744.5 1604.72   824.6 1640.27   877.1  1665.8   892.2 1675.53   970.6 1717.72
#Mann= 3 ,-1 , 0
       0      .1       0  409.12    .045       0  470.28      .1       0
#XS Ineff= 2 , 0
             351 1524.12
Permanent Ineff=
       F       F
Bank Sta=409.12,470.28
XS Rating Curve= 0 ,0
Exp/Cntr(USF)=0,0
Exp/Cntr=0.3,0.1