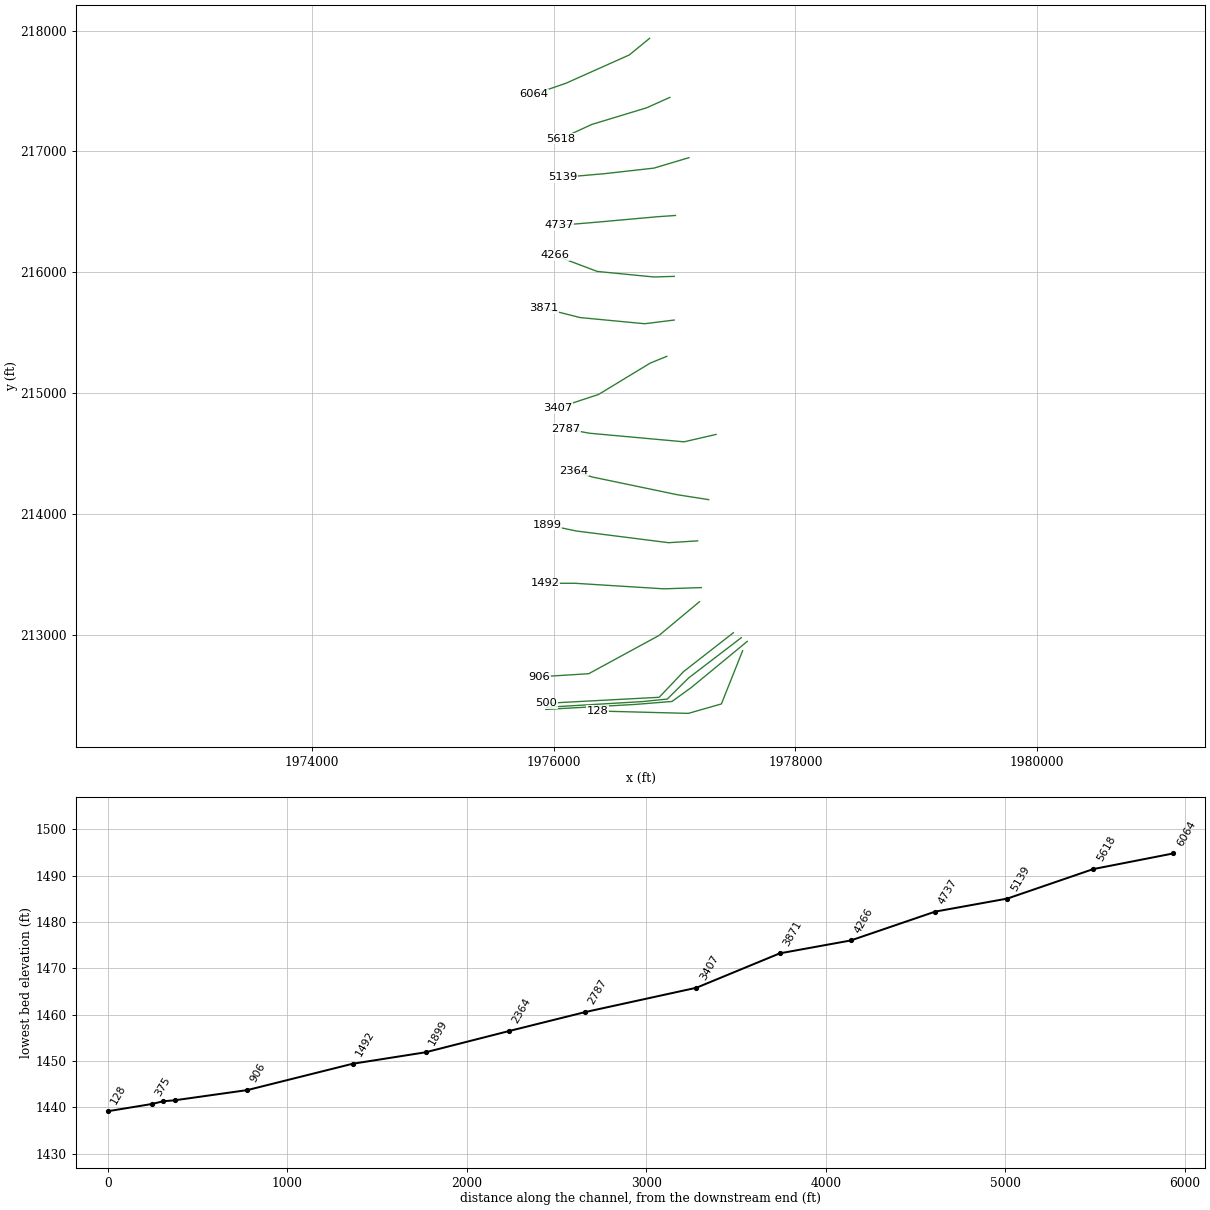
HEC-RAS study LTBLUESTRV.prj: LTBLUESTRV

--- LTBLUESTRV.g01 (geometry) --- (continued)

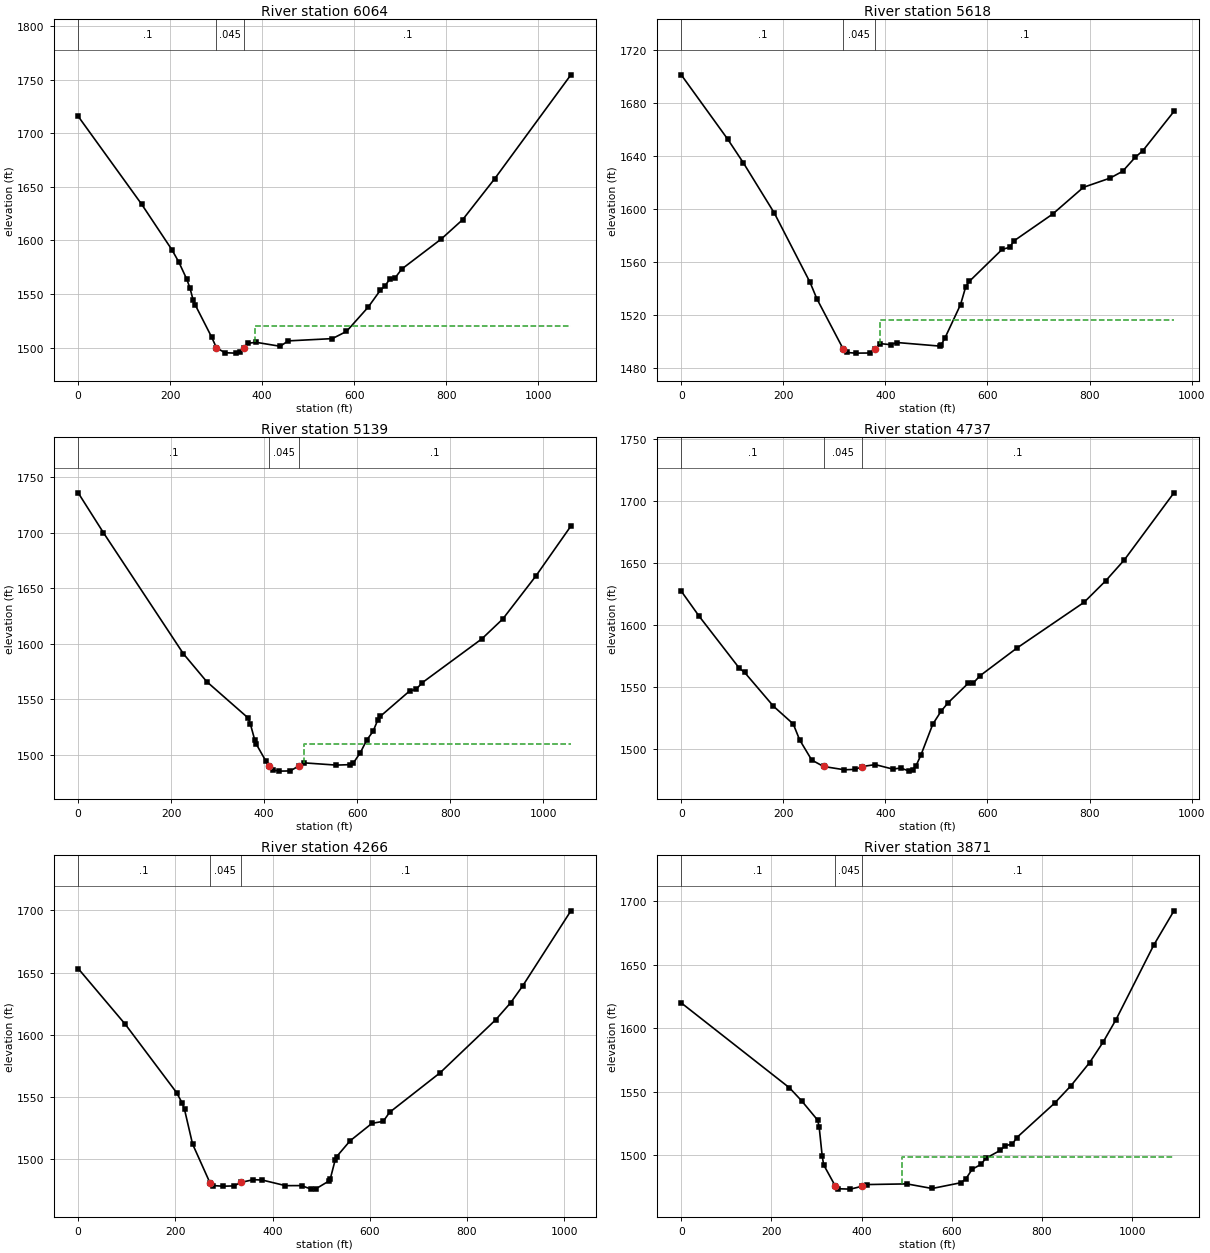
Type RM Length L Ch R = 1 ,6064    ,451.6,446.2,441.6
XS GIS Cut Line= 4
 1976793.4149535 217936.081447311976625.46103632217798.664605985
1976101.24123423217564.5470244681975836.58657686217472.935796918
#Sta/Elev= 30
       0 1715.76     138  1633.7   204.1 1591.04   218.8 1579.77   236.3 1563.57
     243 1555.54   249.9 1544.45   254.2 1540.05   290.2 1509.75  300.531499.872
   318.9 1495.18   342.3 1494.82   352.3 1495.86  361.481499.876   369.2 1504.03
     387 1504.89   439.2 1501.21   456.6 1506.24   552.5 1508.36   583.3 1515.06
   630.5 1537.73   656.7 1553.36   667.5 1557.69   677.6 1564.13     689 1565.01
   703.4 1573.22   789.4 1601.28   835.8 1619.29   905.4 1657.44  1071.2 1754.44
#Mann= 3 ,-1 , 0
       0      .1       0  300.53    .045       0  361.48      .1       0
#XS Ineff= 2 , 0
                           385.1         1519.85
Permanent Ineff=
       F       F
Bank Sta=300.53,361.48
XS Rating Curve= 0 ,0
Exp/Cntr(USF)=0,0
Exp/Cntr=0.3,0.1

Type RM Length L Ch R = 1 ,5618    ,486.2,478.9,471.1
XS GIS Cut Line= 4
1976961.36887067 217447.488233711976767.96739029217360.966518801
1976315.00076518217223.549677476 1976060.5251331217106.490886718
#Sta/Elev= 30
       0 1701.46    91.4 1652.71   121.6 1635.12   182.4 1597.13   252.3 1544.91
   265.7 1532.48  317.491494.456   324.3 1491.92   341.5 1491.44   368.9 1491.53
  380.011494.458   389.5 1498.63     410 1497.83     423 1499.44     506 1496.76
   509.5 1497.87   516.3 1502.56   547.2 1528.05   557.5 1541.67   564.3 1545.55
   628.7 1569.73   643.2 1571.26   652.4 1576.29   727.6 1596.36   787.9 1616.56
   839.9 1623.48   864.8 1628.67   889.4  1639.2   904.6 1644.31   965.3 1673.84
#Mann= 3 ,-1 , 0
       0      .1       0  317.49    .045       0  380.01      .1       0
#XS Ineff= 2 , 0
       0                   389.5       0 1516.45
Permanent Ineff=
       F       F
Bank Sta=317.49,380.01
XS Rating Curve= 0 ,0
Exp/Cntr(USF)=0,0
Exp/Cntr=0.3,0.1

Type RM Length L Ch R = 1 ,5139    ,402,402.2,401.1
XS GIS Cut Line= 4
1977119.14376256216948.7159948261976829.04154199216862.194279918
1976421.88053066216816.3886661421976075.79367102216785.851590292
#Sta/Elev= 30
       0 1736.06    54.2 1700.19   226.4 1590.88   276.5 1565.79   365.1 1533.18
   370.1 1528.02     380 1512.91   383.3 1509.29   403.1 1494.61  411.511489.855
   419.6 1485.93   432.9 1485.07     456 1485.25  475.181489.852   485.7 1492.54
     555  1490.5   584.7 1490.91   591.3 1492.01   606.9 1501.69     621 1513.28
   634.2 1520.83   644.2 1530.88   650.1 1534.55   713.5 1557.55   726.7  1558.7
   739.8 1564.72   868.3 1604.34   913.4 1622.29   984.9 1661.25  1059.9 1706.08
#Mann= 3 ,-1 , 0
       0      .1       0  411.51    .045       0  475.18      .1       0
#XS Ineff= 2 , 0
                          486.83         1509.22
Permanent Ineff=
       F       F
Bank Sta=411.51,475.18
XS Rating Curve= 0 ,0
Exp/Cntr(USF)=0,0
Exp/Cntr=0.3,0.1

Type RM Length L Ch R = 1 ,4737    ,479.1,470.6,462.6
XS GIS Cut Line= 4
1977007.17448445216470.3018065091976859.57861784216460.122781226
1976350.62735367 216414.317167451976045.25659517216388.869604242
#Sta/Elev= 30
       0 1627.54    35.2 1607.23   114.1 1565.18     124 1562.02   180.7 1534.65
   219.5 1520.31     232  1507.5   255.7  1491.2   278.8 1486.01   319.7 1483.34
   341.4 1483.67   354.6 1485.95   380.1 1487.52   414.4 1483.91   430.3 1484.74
   446.8 1482.25   453.4 1483.03     460 1486.49   469.8 1495.38   492.9 1520.16
   509.4 1530.76     523 1537.46   562.1 1553.08     572 1553.21   585.1 1559.12
   657.6 1581.55   789.3 1618.51   831.4 1635.74   868.3  1652.8   965.4 1706.88
#Mann= 3 ,-1 , 0
       0      .1       0   278.8    .045       0   354.6      .1       0
Bank Sta=278.8,354.6
XS Rating Curve= 0 ,0
Exp/Cntr(USF)=0,0
Exp/Cntr=0.3,0.1

Type RM Length L Ch R = 1 ,4266    ,395,395.1,395.1
XS GIS Cut Line= 4
1976996.99545916215966.4400549831976829.04154199215961.350542342
1976360.80637896216007.1561561171976009.63000668  216139.4834848
#Sta/Elev= 30
       0 1653.25    97.2 1608.32   202.4 1553.61   213.7 1545.43   218.8 1540.03
   235.3 1512.31   271.1 1481.14   278.2 1478.86     298 1478.37     321 1478.61
   334.2 1481.38   360.6 1483.62   379.2 1483.28   426.5 1478.82   459.5 1478.85
   479.3 1476.02   489.2 1476.31   515.5 1482.43   518.8 1484.37   528.7 1499.32
     532 1502.22   559.4  1514.8   604.5 1528.88   627.6 1530.46   640.9 1537.77
   744.6 1569.48   859.2 1612.14   889.9  1625.8   914.4 1639.17  1013.8 1699.62
#Mann= 3 ,-1 , 0
       0      .1       0   271.1    .045       0   334.2      .1       0
Bank Sta=271.1,334.2
XS Rating Curve= 0 ,0
Exp/Cntr(USF)=0,0
Exp/Cntr=0.3,0.1

Type RM Length L Ch R = 1 ,3871    ,440.8,464.6,488.9
XS GIS Cut Line= 4
1976996.99545916215605.0846574251976752.69885236215574.547581575
1976218.30002499215625.4427079911975918.01877913215701.785397617
#Sta/Elev= 30
       0  1619.8   240.1 1552.96   267.2 1542.67   302.7 1527.48     306 1521.95
   312.6 1499.47   315.9 1492.36  341.151476.031   348.4 1473.53   375.2 1473.24
   401.6 1475.53   411.5 1476.84   500.4 1477.36   556.5 1473.74   620.7 1478.31
   631.3 1481.36   645.4  1488.9   665.2 1492.78   675.1 1497.43   708.1 1503.83
     718 1507.39   734.4 1508.67   744.3 1513.81   828.2 1540.93   864.5 1554.67
   905.8 1572.84   935.7 1588.92   964.4 1606.72  1047.9  1665.2  1092.8 1692.24
#Mann= 3 ,-1 , 0
       0      .1       0  341.15    .045       0   401.6      .1       0
#XS Ineff= 2 , 0
                          489.97         1498.25
Permanent Ineff=
       F       F
Bank Sta=341.15,401.6
XS Rating Curve= 0 ,0
Exp/Cntr(USF)=0,0
Exp/Cntr=0.3,0.1

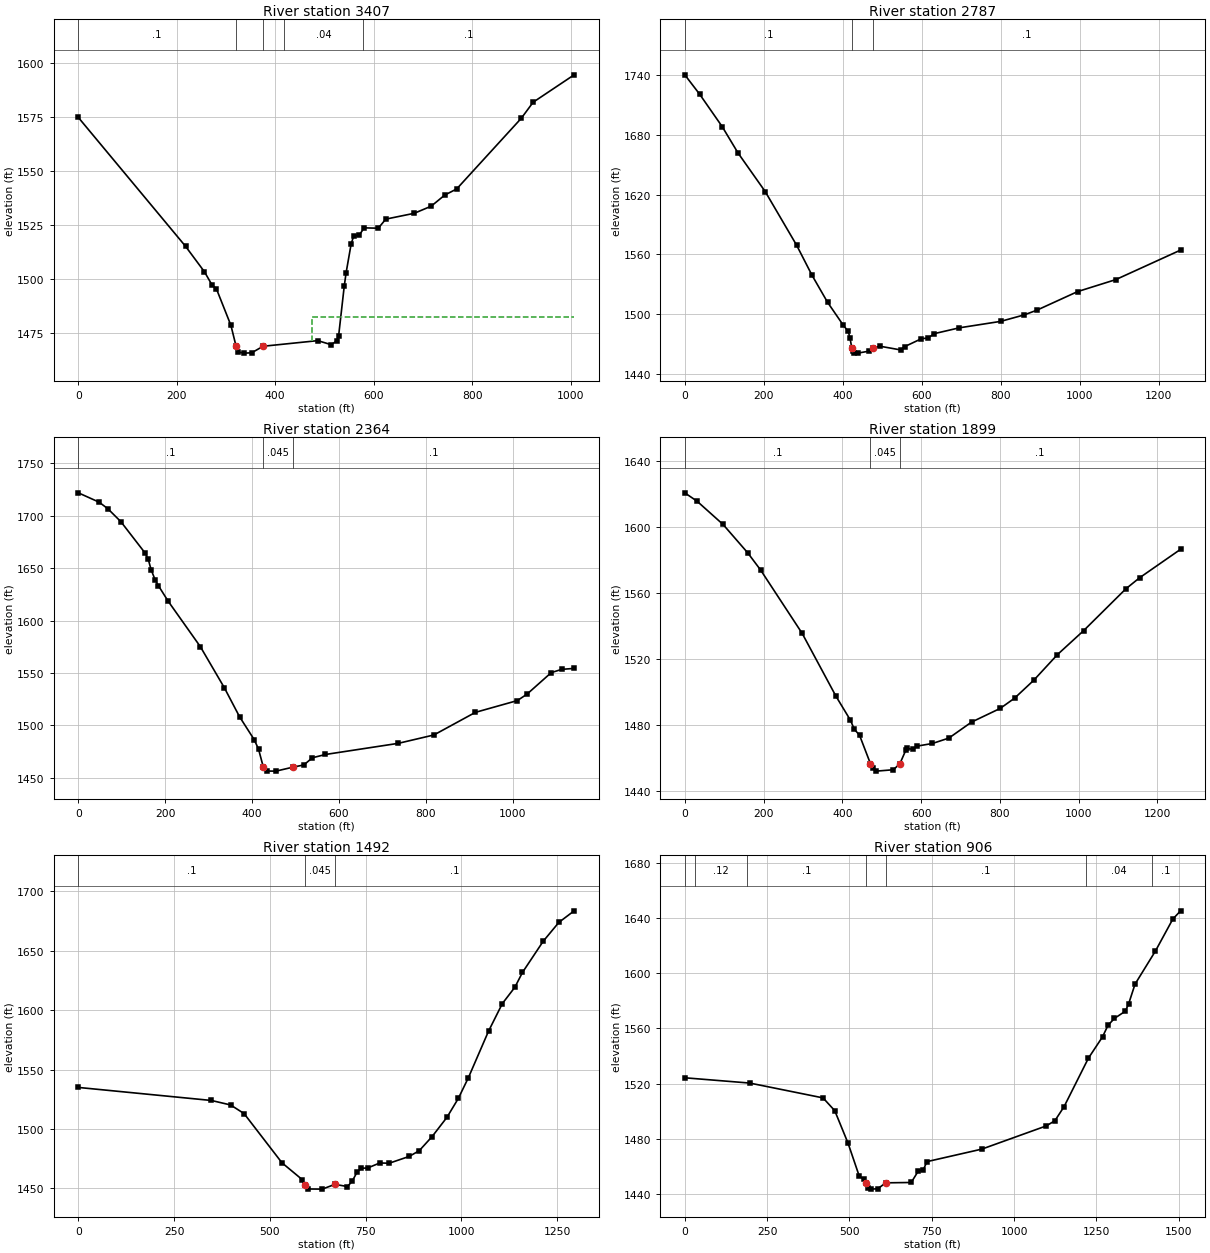
Type RM Length L Ch R = 1 ,3407    ,635.5,619.5,588
XS GIS Cut Line= 4
1976935.92130746215304.8034115661976798.50446614215248.818772508
1976370.98540424214989.2536277831976029.98805725214877.284349666
#Sta/Elev= 30
       0 1574.73   217.9 1515.16   256.3 1503.38   271.6 1497.32   280.5 1495.56
     310 1478.64   320.3 1469.19   325.3 1466.28   337.1 1465.81   352.2 1465.95
   375.3 1468.98   486.5 1471.58   513.8 1469.71   524.9 1471.46   528.8 1473.69
   540.3 1496.83   544.1 1503.02   554.4 1516.41   559.5 1519.88   571.1 1520.44
   580.7 1523.71   609.4 1523.54   624.7 1527.74   682.4 1530.43   716.9 1533.72
   744.5 1538.86   768.7 1541.68   899.9 1574.33   924.1 1581.77  1007.4 1594.43
#Mann= 5 ,-1 , 0
       0      .1       0   320.3    .045       0   375.3      .1       0
  418.38     .04       0  578.38      .1       0
#XS Ineff= 2 , 0
                           474.5         1482.41
Permanent Ineff=
       F       F
Bank Sta=320.3,375.3
XS Rating Curve= 0 ,0
Exp/Cntr(USF)=0,0
Exp/Cntr=0.3,0.1

Type RM Length L Ch R = 1 ,2787    ,426.4,423.6,417.9
XS GIS Cut Line= 4
 1977343.0823188214658.4353060741977078.42766143214597.361154374
1976294.64271461214668.6143313571976101.24123423214704.240919849
#Sta/Elev= 30
       0 1740.63    37.4 1721.21    94.6 1688.55     135 1661.84   203.5 1623.21
   282.9  1569.3   322.4 1538.69   361.3 1511.81   401.7 1488.39   413.8 1482.43
     418 1476.13  423.031465.481   424.6 1462.84   427.8 1460.72   437.7 1460.56
   467.4 1462.61     477 1465.54   493.7 1467.54   546.4 1463.78   556.3 1467.04
   599.2  1475.1   615.6 1475.74   632.1 1480.21   694.7    1486   799.8 1492.52
   859.4 1499.06     891 1503.71   994.5 1522.49    1091 1534.53  1255.3 1564.28
#Mann= 3 ,-1 , 0
       0      .1       0  423.03    .045       0     477      .1       0
Bank Sta=423.03,477
XS Rating Curve= 0 ,0
Exp/Cntr(USF)=0,0
Exp/Cntr=0.3,0.1

Type RM Length L Ch R = 1 ,2364    ,458.1,465,465.5
XS GIS Cut Line= 4
 1977282.0081671214118.9469660571977022.44302237 214159.66306719
1976315.00076518214307.2589337991976167.40489857214358.154060215
#Sta/Elev= 30
       0 1721.77    48.1 1712.81      68 1706.58    97.9 1694.29   153.6 1664.44
     161 1658.36   167.6 1648.41   177.2 1638.43   184.2 1633.36   206.6 1618.57
   280.9 1575.12   336.1    1536   371.2 1508.29   404.7  1486.6   414.8 1477.54
  425.881460.307   434.9 1456.53     455 1456.47  494.621460.311   519.1 1462.35
   538.8 1469.19   568.9 1472.34   736.5 1482.95   818.6 1490.94   914.1 1512.49
  1010.8 1523.74  1033.1  1529.9  1088.6 1550.33  1112.9  1553.5  1141.5 1554.39
#Mann= 3 ,-1 , 0
       0      .1       0  425.88    .045       0  494.62      .1       0
Bank Sta=425.88,494.62
XS Rating Curve= 0 ,0
Exp/Cntr(USF)=0,0
Exp/Cntr=0.3,0.1

Type RM Length L Ch R = 1 ,1899    ,404.2,406.8,410.6
XS GIS Cut Line= 4
1977190.39693955213777.9496190651976951.18984539 213762.68108114
1976187.76294914213859.3818213321975943.46634234213910.276947748
#Sta/Elev= 30
       0 1620.85    31.4 1615.71    97.2 1601.63   159.6 1584.46   192.5 1573.98
     298  1535.5     384 1497.26   420.4 1482.85   430.3 1477.34   443.6 1473.68
  471.391456.357   476.6 1454.04   486.5 1451.88   529.5 1452.72  545.971456.355
   561.8 1464.95   564.7 1465.66   579.1  1465.1   589.1 1467.04   628.7 1468.67
   670.4 1471.94     728 1481.65   800.7 1489.95   837.1 1496.15   885.6 1506.97
   946.2 1522.66  1012.4 1537.14  1119.6 1562.53  1154.6 1569.27  1258.8 1586.58
#Mann= 3 ,-1 , 0
       0      .1       0  471.39    .045       0  545.97      .1       0
Bank Sta=471.39,545.97
XS Rating Curve= 0 ,0
Exp/Cntr(USF)=0,0
Exp/Cntr=0.3,0.1

Type RM Length L Ch R = 1 ,1492    ,568,586,603.3
XS GIS Cut Line= 4
 1977220.9340154213391.1466582981976910.47374426213380.967633015
1976177.58392386 213426.773246791975928.19780441 213426.77324679
#Sta/Elev= 30
       0 1534.95   347.6 1523.97   397.6 1520.19   432.7 1512.94   531.6 1471.54
   584.2 1457.48  591.121453.187   600.7 1449.53   636.8  1449.4   669.7 1453.42
   702.6 1451.56   714.9 1456.07   727.2 1463.47   738.7    1467   755.1 1467.15
   786.8 1471.41   811.4 1471.19   863.7 1476.91   889.9 1481.73   923.6 1493.66
   962.3 1509.83   991.9 1525.69  1018.2 1543.14  1070.7 1582.23  1106.8 1605.48
  1139.6 1619.26  1159.3 1631.67  1213.5 1657.91  1254.4  1673.8  1294.3 1683.52
#Mann= 3 ,-1 , 0
       0      .1       0  591.12    .045       0   669.7      .1       0
Bank Sta=591.12,669.7
XS Rating Curve= 0 ,0
Exp/Cntr(USF)=0,0
Exp/Cntr=0.3,0.1

Type RM Length L Ch R = 1 ,906     ,390.1,405.4,418.4
XS GIS Cut Line= 4
1977205.66547747213274.0878675391976869.75764312212994.164672248
1976289.55320197212678.6148884641975882.39219064212653.167325256
#Sta/Elev= 30
       0 1524.27   197.3 1520.45   419.8 1509.72   455.3  1500.5   495.8 1476.92
     530 1452.95   544.9 1450.81   549.7 1448.39   556.1 1444.57   566.7 1443.72
     586    1444   610.2 1448.27   687.6 1448.53   709.2 1456.87   724.2 1457.68
   735.4 1463.61     902 1472.67  1097.6 1489.45  1123.9 1493.22  1151.8 1503.41
  1225.8 1538.52  1268.6 1553.92    1285 1562.18  1304.7 1567.25  1337.6 1572.42
  1347.5 1577.54  1367.2 1592.01    1429  1615.9  1482.2 1639.191505.671 1645.06
#Mann= 7 ,-1 , 0
       0      .1       0      30     .12       0     190      .1       0
   549.7    .045       0   610.2      .1       0 1217.72     .04       0
 1417.72      .1       0
Bank Sta=549.7,610.2
XS Rating Curve= 0 ,0
Exp/Cntr(USF)=0,0
Exp/Cntr=0.5,0.3

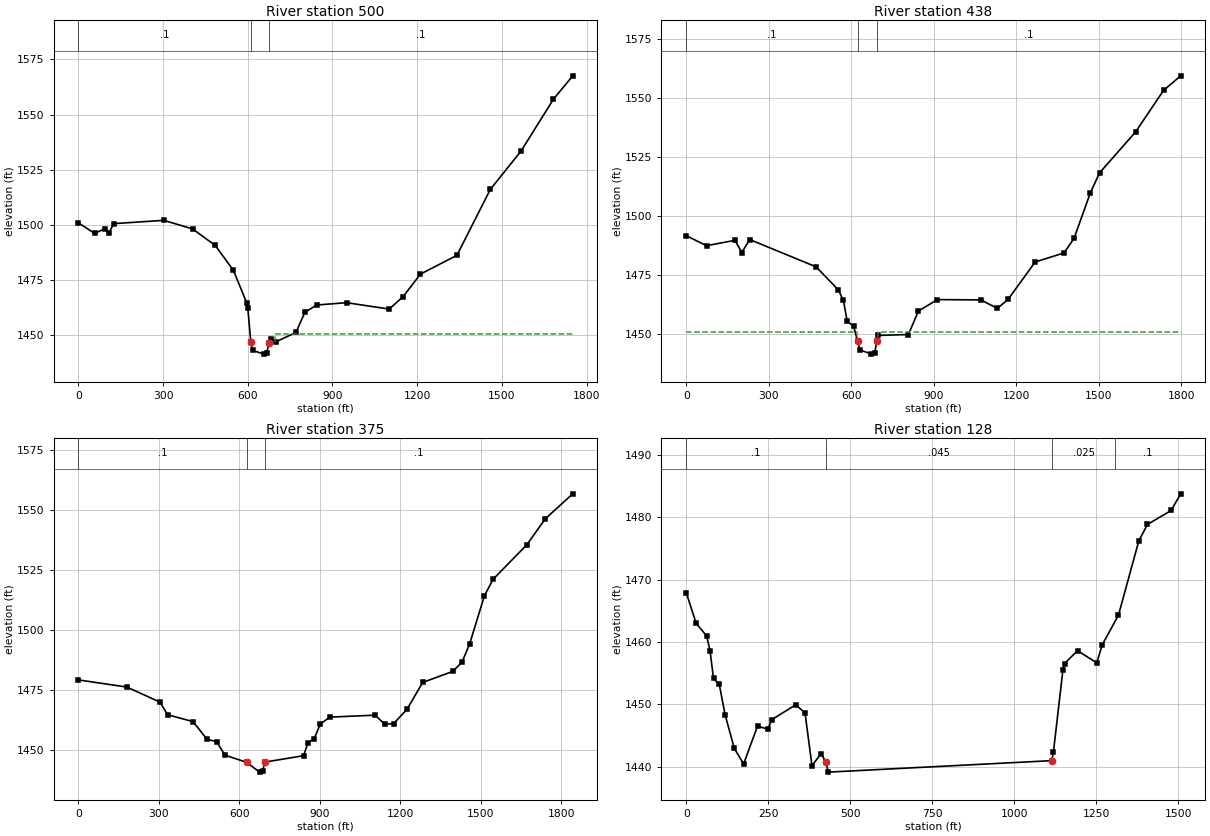
Type RM Length L Ch R = 1 ,500     ,64.7,62.7,61.6
XS GIS Cut Line= 4
1977486.72759574213017.6970080221977075.01962347212696.493805514
1976872.71484399212483.5414060611975939.27349305212433.852512855
#Sta/Elev= 30
       0 1501.04    57.9 1496.22    95.2 1498.38   107.7 1496.16   125.6 1500.63
   303.2 1502.12   404.6 1498.23   484.6  1490.8   549.1 1479.51   597.2 1464.52
   600.2 1462.41  610.861447.103     617 1443.19   657.7 1441.51   666.8 1441.97
   676.1 1446.73   680.8 1448.37   698.4 1446.99   770.8 1451.36   802.5 1460.51
   844.6 1463.76   949.7 1464.82  1100.8 1461.92  1150.1 1467.54  1211.3 1477.74
  1340.7 1486.28    1459 1516.16  1567.4 1533.45  1682.3 1556.991750.673 1567.59
#Mann= 3 ,-1 , 0
       0      .1       0  610.86    .045       0   676.1      .1       0
#XS Ineff= 2 , 0
             590 1450.59     697         1450.59
Permanent Ineff=
       F       F
Bank Sta=610.86,676.1
XS Rating Curve= 0 ,0
Exp/Cntr(USF)=0,0
Exp/Cntr=0.5,0.3

Type RM Length L Ch R = 1 ,438     ,80.9,63.2,171.6
XS GIS Cut Line= 5
1977552.38791891 212976.881131461977116.71719395212643.816231858
1976939.62454114212468.8193500841976733.19109377212447.861639692
1975942.03917685212400.995235334
#Sta/Elev= 30
       0 1491.62    73.9 1487.37   177.1 1489.65   201.9 1484.47   230.8 1489.99
   472.2 1478.38   552.6 1468.66   571.2 1464.17   585.2 1455.22   608.6 1453.11
  622.821446.908   631.9 1443.12   673.4 1441.31   685.2 1441.86  692.781446.904
   697.2 1449.26   807.7 1449.62   843.9 1459.62   913.2 1464.47  1071.1 1464.34
  1130.8 1460.73  1169.8 1464.54  1268.4 1480.44  1373.6 1484.31  1409.8 1490.49
  1468.9 1509.79  1502.4  1518.3  1633.3 1535.67  1735.1 1553.341797.401 1559.52
#Mann= 3 ,-1 , 0
       0      .1       0  622.82    .045       0  692.78      .1       0
#XS Ineff= 2 , 0
             619 1450.59     696         1450.59
Permanent Ineff=
       F       F
Bank Sta=622.82,692.78
XS Rating Curve= 0 ,0
Exp/Cntr(USF)=0,0
Exp/Cntr=0.5,0.3

Type RM Length L Ch R = 1 ,375     ,282.2,246.6,187.4
XS GIS Cut Line= 5
1977601.29328925212945.7984572681977138.12182044212564.258741581
1976978.40752085212448.9095252111976669.62654165212424.065078608
1975934.94076353212383.249202047
#Sta/Elev= 30
       0 1479.16   181.2 1476.17   305.2 1469.85   332.7 1464.63   427.9 1461.77
   479.5  1454.4   515.7 1453.42   546.6 1447.78  627.06 1444.82   675.9 1440.72
   687.6 1441.24   694.7 1444.89   839.7 1447.57     856 1452.94   879.2 1454.67
   902.2 1460.81   938.3 1463.65  1106.3 1464.46  1142.4 1460.67  1175.3 1460.94
  1224.9 1466.88  1283.5  1478.1  1395.5 1482.69  1429.8 1486.53    1458 1493.97
  1513.7 1514.28  1546.6 1521.18  1671.5 1535.45  1740.5  1546.31842.694  1556.7
#Mann= 3 , 0 , 0
       0      .1       0  627.06    .045       0   694.7      .1       0
Bank Sta=627.06,694.7
XS Rating Curve= 0 ,0
Exp/Cntr(USF)=0,0
Exp/Cntr=0.3,0.1

Type RM Length L Ch R = 1 ,128     ,,,
XS GIS Cut Line= 4
1977563.25724256212869.0486681461977387.47599256212428.510473713
1977114.03849253212350.385473698 1976365.3405759212369.916723698
#Sta/Elev= 30
       0 1467.92    30.2    1463      62 1460.98    72.6 1458.62    83.2 1454.15
   100.8  1453.2   118.5 1448.35   146.7 1442.94     175 1440.46   217.4 1446.52
   249.2 1446.03   260.6 1447.55     334 1449.94   362.2 1448.64   383.4 1440.19
   411.7 1442.13   426.1  1440.7   432.9 1439.15  1114.1 1440.99  1119.6 1442.37
  1148.4 1455.45  1153.4 1456.55  1193.1  1458.6  1251.9 1456.66  1268.3 1459.52
  1317.9  1464.3  1379.9 1476.18  1406.2 1478.82  1478.4 1481.061507.645 1483.73
#Mann= 4 ,-1 , 0
       0      .1       0   426.1    .045       0  1114.1    .025       0
 1308.69      .1       0
Bank Sta=426.1,1114.1
XS Rating Curve= 0 ,0
Exp/Cntr(USF)=0,0
Exp/Cntr=0.3,0.1
LCMann Table=0

Chan Stop Cuts=-1
Use User Specified Reach Order=0
Composite Channel Slope=5